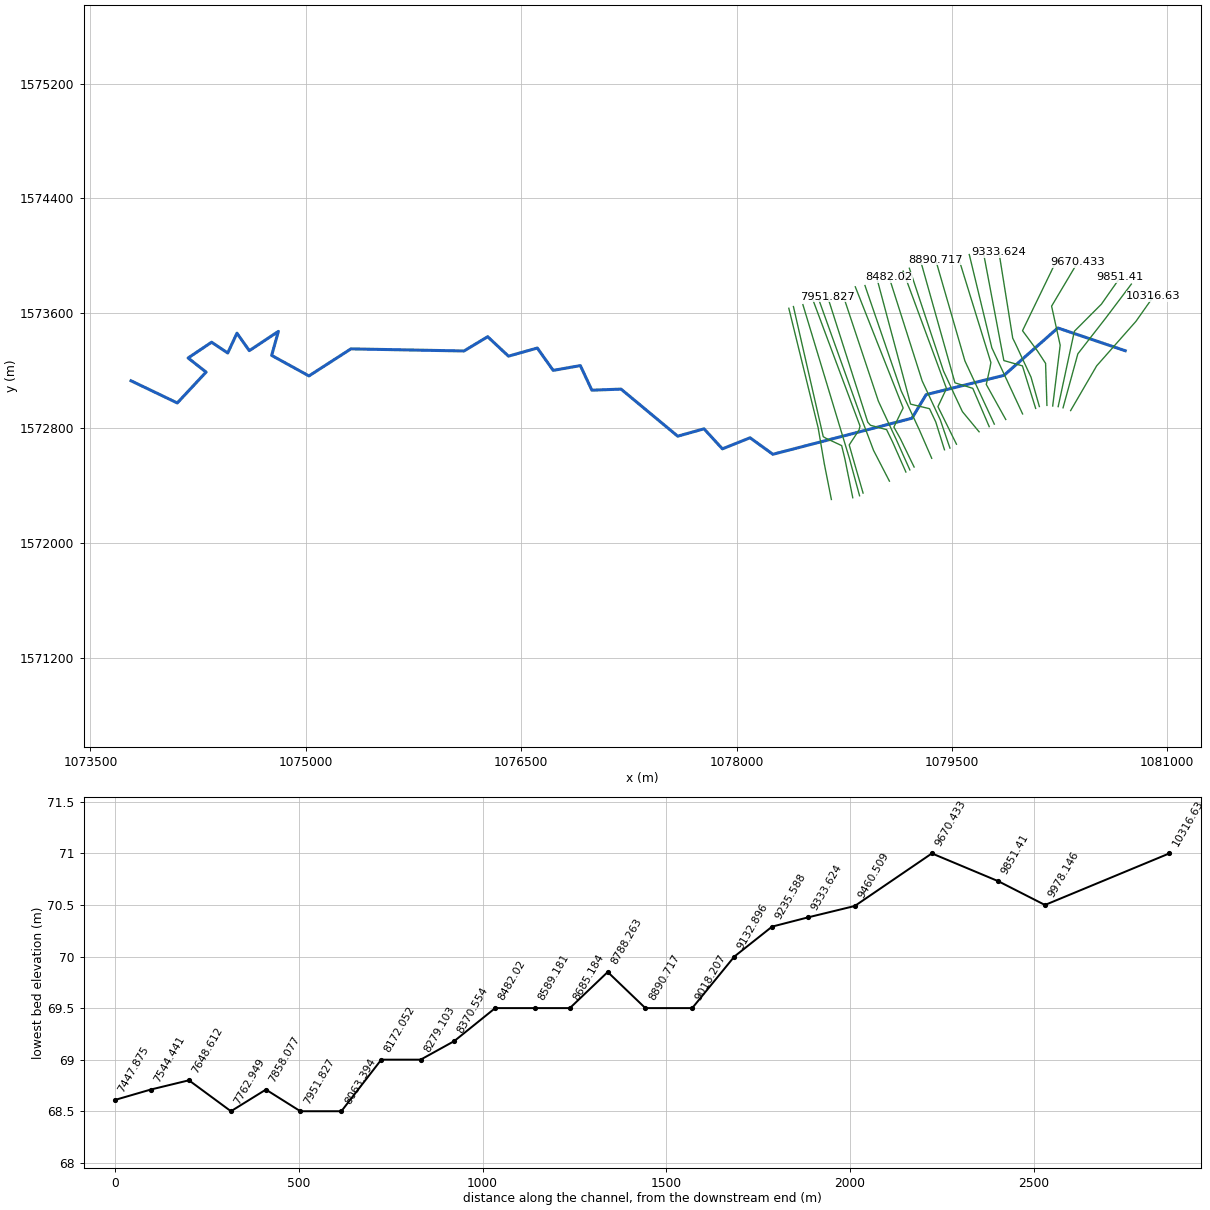
--- HECRAS_v1.prj (project) ---

Proj Title=HECRAS_v1
Current Plan=p01
Default Exp/Contr=0.3,0.1
SI Units
Geom File=g01
Geom File=g02
Flow File=f01
Unsteady File=u01
Unsteady File=u02
Plan File=p01
Plan File=p02
Plan File=p03
Y Axis Title=Elevation
X Axis Title(PF)=Main Channel Distance
X Axis Title(XS)=Station
BEGIN DESCRIPTION:
END DESCRIPTION:
DSS File=dss
DSS Export Rating Curves= 0
DSS Export Rating Curve Sorted= 0
DSS Export Volume Flow Curves= 0
DXF OffsetX= 0
DXF OffsetY= 0
DXF ScaleX= 1
DXF ScaleY= 10

--- HECRAS_v1.p01 (plan) ---

Plan Title=Np2_33
Program Version=6.50
Short Identifier=Np2_33
Simulation Date=05mar2016,00:15,08mar2016,00:15
Geom File=g02
Flow File=u01
Subcritical Flow
K Sum by GR= 0
Std Step Tol= 0.003
Critical Tol= 0.003
Num of Std Step Trials= 20
Max Error Tol= 0.1
Flow Tol Ratio= 0.001
Split Flow NTrial= 30
Split Flow Tol= 0.006
Split Flow Ratio= 0.02
Log Output Level= 0
Friction Slope Method= 1
Unsteady Friction Slope Method= 2
Unsteady Bridges Friction Slope Method= 1
Parabolic Critical Depth
Global Vel Dist= 0 , 0 , 0
Global Log Level= 0
CheckData=True
Encroach Param=-1 ,0,0, 0
Flow Ratio Tolerance=0.1
Flow Ratio Min Ratio=0.5
Flow Ratio Max Ratio=4
Flow Ratio Max Iterations= 10
Computation Interval=1MIN
Output Interval=15MIN
Instantaneous Interval=1HOUR
Mapping Interval=1HOUR
Computation Time Step Use Courant=        0
Computation Time Step Use Time Series=    0
Computation Time Step Count To Double=0
Computation Time Step Max Doubling=0
Computation Time Step Max Halving=0
Computation Time Step Residence Courant=0
Run HTab=-1
Run UNet=-1
Run Sediment= 0
Run PostProcess=-1
Run WQNet= 0
Run RASMapper= 0
UNET Theta= 1
UNET Theta Warmup= 1
UNET ZTol= 0.006
UNET ZSATol= 0.006
UNET MxIter= 20
UNET Max Iter WO Improvement= 0
UNET MaxInSteps= 0
UNET DtIC= 0
UNET DtMin= 0
UNET MaxCRTS= 20
UNET WFStab= 2
UNET SFStab= 1
UNET WFX= 1
UNET SFX= 1
UNET Gravity=9.80665
UNET 1D Methodology=Finite Difference
UNET DSS MLevel= 4
UNET Pardiso=0
UNET DZMax Abort= 30
UNET Use Existing IB Tables=-1
UNET Froude Reduction=False
UNET Froude Limit= 0.8
UNET Froude Power= 4
UNET D1 Cores= 0
UNET WindReference=Eulerian
UNET WindDragFormulation=Hsu (1988)
UNET D2 Coriolis=0
UNET D2 Cores= 0
UNET D2 Theta= 1
UNET D2 Theta Warmup= 1
UNET D2 Z Tol= 0.003
UNET D2 Volume Tol= 0.003
UNET D2 Max Iterations= 20
UNET D2 Equation= 0
UNET D2 RampUpFraction=0.1
UNET D2 TimeSlices= 1
UNET D2 Turbulence Formulation=None
UNET D2 Eddy Viscosity=0.3
UNET D2 Transverse Eddy Viscosity=0.1
UNET D2 Smagorinsky Mixing=0.05
UNET D2 BCVolumeCheck=0
UNET D2 Cores=0
UNET D2 SolverType=PARDISO (Direct)
UNET D2 Minimum Iterations= 3
UNET D2 Maximum Iterations= 30
UNET D2 Restart Number= 10
UNET D2 Relaxation Coeff=1.3
UNET D2 SOR Precondition Iterations= 10
UNET D2 ILUT Maximum Fill= 8
UNET D2 ILUT Tolerance=1E-08
UNET D2 Convergence Tolerance=0.00001
PS Theta= 1
PS WS Tol= 0.003
PS Volume Tol= 0.003
PS Max Iterations= 20
PS Time Slices= 1
PS Cores=0
UNET D1D2 MaxIter= 0
UNET D1D2 ZTol=0.003
UNET D1D2 QTol=0.1
UNET D1D2 MinQTol=0.03
DSS File=dss
Write IC File= 0
Write IC File at Fixed DateTime=0
Write IC File at Sim End=0
Echo Input=False
Echo Parameters=False
Echo Output=False
Write Detailed= 0
HDF Write Warmup=0
HDF Write Time Slices=0
HDF Flush=0
HDF Compression= 1
HDF Chunk Size= 1
HDF Spatial Parts= 1
HDF Use Max Rows=0
HDF Fixed Rows= 1
Calibration Method= 0
Calibration Iterations= 20
Calibration Max Change=0.05
Calibration Tolerance=0.2
Calibration Maximum=1.5
Calibration Minimum=0.5
Calibration Optimization Method= 1
WQ AD Non Conservative
WQ ULTIMATE=-1
WQ Max Comp Step=1HOUR
WQ Output Interval=15MIN
WQ Output Selected Increments= 0
WQ Create Restart=0
WQ Fixed Restart=0
WQ System Summary=0
WQ Write To DSS=0
Sorting and Armoring Iterations= 10
XS Update Threshold= 0.02
Bed Roughness Predictor= 0
Hydraulics Update Threshold= 0.02
Energy Slope Method= 1
Volume Change Method= 1
Sediment Retention Method= 0
Sediment TS Multiplier= 1
Warm Up Method= 0
XS Weighting Method= 0
Number of US Weighted Cross Sections= 1
Number of DS Weighted Cross Sections= 1
Upstream XS Weight=0
Main XS Weight=1
Downstream XS Weight=0
Number of DS XS's Weighted with US Boundary= 1
Upstream Boundary Weight= 1
Weight of XSs Associated with US Boundary= 0
Number of US XS's Weighted with DS Boundary= 1
Downstream Boundary Weight= 0.5
Weight of XSs Associated with DS Boundary= 0.5
Percentile Method= 0
Sediment Output Level= 3
Mass or Volume Output= 0
Output Increment Type= 1
Profile and TS Output Increment= 1
Transport Output Increment 1
XS Output Flag= 0
XS Output Increment= 10
Read HDF5 Sediment Hotstart= 0
Sediment Hotstart Type= 0
Write Gradation File= 0
Read Gradation Hotstart= 0
Write HDF5 File= 1
Write Binary Output= 1
Write DSS Sediment File= 0
DSS Sediment Output Type= 1
SV Curve= 0
Specific Gage Flag= 0
Subcell Erosion Methods= 0
Subcell Deposition Methods= 0
Advection Scheme= 1
Matrix Solver= 0
Implicit Weighting Factor= 1
Maximum Outer Loop Convergence Iterations= 5
Convergence Maximum Absolute= 0.001
Convergence RMSE= 0.0001
Grain Fractions Max Abs Error= 0.001
Max Subgrid Regions= 1
Max Subgrid Length Scale= 3.402823E+38
Initial Layer Thickness= 3
Min Layer Thickness= 0.1
Max Layer Thickness= 6
Number of Layers= 5

--- HECRAS_v1.p02 (plan) ---

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Plan Title=Np100
Short Identifier=Np100
Geom File=g02
Flow File=u02
Mixed Flow

--- HECRAS_v1.p03 (plan) ---

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Plan Title=Permanente
Short Identifier=Permanente
Geom File=g01
Flow File=f01
Output Interval=1HOUR
Run HTab= 0
Run UNet= 0
Run PostProcess= 0

--- HECRAS_v1.f01 (steady flow) ---

Flow Title=Permanente
Program Version=6.50
Number of Profiles= 2
Profile Names=Tr2_33,Tr100
River Rch & RM=ARROYOELZORRO,ABAJOLAT1       ,8685.184
   129.6   519.7
River Rch & RM=ARROYOELZORRO,ARRIBALAT1      ,10316.63
     130   522.1
River Rch & RM=LATERAL1,LATERAL1        ,4571.366
    19.4    65.6
Boundary for River Rch & Prof#=ARROYOELZORRO,ABAJOLAT1       , 1
Up Type= 0
Dn Type= 3
Dn Slope=0.0008969
Boundary for River Rch & Prof#=ARROYOELZORRO,ABAJOLAT1       , 2
Up Type= 0
Dn Type= 3
Dn Slope=0.0008969
Boundary for River Rch & Prof#=ARROYOELZORRO,ARRIBALAT1      , 1
Up Type= 2
Dn Type= 0
Boundary for River Rch & Prof#=ARROYOELZORRO,ARRIBALAT1      , 2
Up Type= 2
Dn Type= 0
Boundary for River Rch & Prof#=LATERAL1,LATERAL1        , 1
Up Type= 2
Dn Type= 0
Boundary for River Rch & Prof#=LATERAL1,LATERAL1        , 2
Up Type= 2
Dn Type= 0
DSS Import GetInterval= 0
DSS Import GetPeak= 0
DSS Import FillOption= 0

--- HECRAS_v1.u01 (unsteady flow) ---

Flow Title=Np2_33
Program Version=6.50
Use Restart= 0
Initial Flow Loc=ARROYOELZORRO   ,ABAJOLAT1       ,8685.184,0.001
Initial Flow Loc=ARROYOELZORRO   ,ARRIBALAT1      ,10316.63,0.001
Initial Flow Loc=LATERAL1        ,LATERAL1        ,4571.366,0.001
Boundary Location=ARROYOELZORRO   ,ABAJOLAT1       ,0       ,        ,                ,                ,                ,                                ,
Friction Slope=0.0008969,0
Boundary Location=ARROYOELZORRO   ,ARRIBALAT1      ,10316.63,        ,                ,                ,                ,                                ,
Interval=1MIN
Flow Hydrograph= 4321
       0       0       0       0       0       0       0       0       0       0
       0       0       0       0       0       0       0       0       0       0
       0       0       0       0       0       0       0       0       0       0
       0       0       0       0       0       0       0       0       0       0
       0       0       0       0       0       0      .1      .1      .1      .1
      .1      .1      .1      .1      .1      .1      .2      .2      .2      .2
      .2      .2      .3      .3      .3      .3      .4      .4      .4      .4
      .5      .5      .5      .6      .6      .6      .7      .7      .7      .8
      .8      .9      .9       1       1     1.1     1.1     1.2     1.2     1.3
     1.4     1.4     1.5     1.6     1.6     1.7     1.8     1.8     1.9       2
     2.1     2.1     2.2     2.3     2.4     2.5     2.6     2.7     2.7     2.8
     2.9       3     3.1     3.2     3.3     3.4     3.5     3.6     3.8     3.9
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Stage Hydrograph TW Check=0
Use DSS=False
Use Fixed Start Time=True
Fixed Start Date/Time=05mar2016,00:15
Is Critical Boundary=False
Boundary Location=LATERAL1        ,LATERAL1        ,4571.366,        ,                ,                ,                ,                                ,
Interval=1MIN
Flow Hydrograph= 4321
       0       0       0       0       0       0       0       0       0       0
       0       0       0       0       0       0       0       0       0       0
       0       0       0       0       0       0       0       0       0       0
       0       0       0       0       0       0       0       0       0       0
       0       0       0       0       0       0      .1      .1      .1      .1
      .1      .1      .1      .1      .1      .1      .1      .1      .2      .2
      .2      .2      .2      .2      .2      .3      .3      .3      .3      .3
      .4      .4      .4      .4      .4      .5      .5      .5      .5      .6
      .6      .6      .6      .7      .7      .7      .8      .8      .8      .9
      .9      .9       1       1     1.1     1.1     1.1     1.2     1.2     1.3
     1.3     1.4     1.4     1.5     1.5     1.6     1.6     1.7     1.7     1.8
     1.8     1.9     1.9       2     2.1     2.1     2.2     2.2     2.3     2.4
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Stage Hydrograph TW Check=0
Use DSS=False
Use Fixed Start Time=True
Fixed Start Date/Time=05mar2016,00:15
Is Critical Boundary=False
Boundary Location=ARROYOELZORRO   ,ARRIBALAT1      ,0       ,        ,                ,                ,                ,                                ,
Friction Slope=0.0008969,0
Precipitation Mode=Disable
Wind Mode=No Wind Forces
Air Density Mode=Specified
Met BC=Precipitation|Expanded View=0
Met BC=Precipitation|Point Interpolation=Nearest
Met BC=Precipitation|Gridded Source=DSS
Met BC=Evapotranspiration|Expanded View=0
Met BC=Evapotranspiration|Point Interpolation=Nearest
Met BC=Evapotranspiration|Gridded Source=DSS
Met BC=Wind Speed|Expanded View=0
Met BC=Wind Speed|Point Interpolation=Nearest
Met BC=Wind Speed|Gridded Source=DSS
Met BC=Wind Direction|Expanded View=0
Met BC=Wind Direction|Point Interpolation=Nearest
Met BC=Wind Direction|Gridded Source=DSS
Met BC=Wind Velocity X|Expanded View=0
Met BC=Wind Velocity X|Point Interpolation=Nearest
Met BC=Wind Velocity X|Gridded Source=DSS
Met BC=Wind Velocity Y|Expanded View=0
Met BC=Wind Velocity Y|Point Interpolation=Nearest
Met BC=Wind Velocity Y|Gridded Source=DSS
Met BC=Air Density|Mode=Constant
Met BC=Air Density|Expanded View=0
Met BC=Air Density|Constant Value=1.225
Met BC=Air Density|Constant Units=kg/m3
Met BC=Air Density|Point Interpolation=Nearest
Met BC=Air Density|Gridded Source=DSS
Met BC=Air Temperature|Expanded View=0
Met BC=Air Temperature|Point Interpolation=Nearest
Met BC=Air Temperature|Gridded Source=DSS
Met BC=Humidity|Expanded View=0
Met BC=Humidity|Point Interpolation=Nearest
Met BC=Humidity|Gridded Source=DSS
Met BC=Air Pressure|Mode=Constant
Met BC=Air Pressure|Expanded View=0
Met BC=Air Pressure|Constant Value=1013.2
Met BC=Air Pressure|Constant Units=mb
Met BC=Air Pressure|Point Interpolation=
Met BC=Air Pressure|Gridded Source=DSS
Non-Newtonian Method= 0 ,
Non-Newtonian Constant Vol Conc=0
Non-Newtonian Yield Method= 0 ,
Non-Newtonian Yield Coef=0, 0
User Yeild=   0
Non-Newtonian Sed Visc= 0 ,
Non-Newtonian Obrian B=0
User Viscosity=0
User Viscosity Ratio=0
Herschel-Bulkley Coef=0, 0
Clastic Method= 0 ,
Coulomb Phi=0
Voellmy X=0
Non-Newtonian Hindered FV= 0
Non-Newtonian FV K=0
Non-Newtonian ds=0
Non-Newtonian Max Cv=0
Non-Newtonian Bulking Method= 0 ,
Non-Newtonian High C Transport= 0 ,
Lava Activation= 0
Temperature=1300,15,,15,14,980
Heat Ballance=1,1200,0.5,1,70,0.95
Viscosity=1000,,,
Profile Coefficient=4,1.3,
Lava Param=,2500,

--- HECRAS_v1.u02 (unsteady flow) ---

Flow Title=Np100
Program Version=6.50
Use Restart= 0
Initial Flow Loc=ARROYOELZORRO   ,ABAJOLAT1       ,8685.184,0.001
Initial Flow Loc=ARROYOELZORRO   ,ARRIBALAT1      ,10316.63,0.001
Initial Flow Loc=LATERAL1        ,LATERAL1        ,4571.366,0.001
Boundary Location=ARROYOELZORRO   ,ABAJOLAT1       ,0       ,        ,                ,                ,                ,                                ,
Friction Slope=0.0008969,0
Boundary Location=ARROYOELZORRO   ,ARRIBALAT1      ,10316.63,        ,                ,                ,                ,                                ,
Interval=1MIN
Flow Hydrograph= 4321
       0       0       0       0       0       0       0       0       0       0
       0       0       0       0       0       0       0       0       0       0
       0       0       0       0      .1      .1      .1      .1      .1      .1
      .1      .2      .2      .2      .3      .3      .3      .4      .4      .5
      .5      .6      .6      .7      .7      .8      .9       1     1.1     1.1
     1.2     1.3     1.4     1.5     1.7     1.8     1.9       2     2.2     2.3
     2.5     2.6     2.8     2.9     3.1     3.3     3.5     3.7     3.9     4.1
     4.3     4.5     4.7       5     5.2     5.4     5.7       6     6.2     6.5
     6.8     7.1     7.4     7.7       8     8.3     8.6     8.9     9.2     9.6
     9.9    10.3    10.6      11    11.4    11.7    12.1    12.5    12.9    13.3
    13.7    14.1    14.5    14.9    15.3    15.8    16.2    16.7    17.1    17.6
      18    18.5    18.9    19.4    19.9    20.4    20.9    21.4    21.8    22.4
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Stage Hydrograph TW Check=0
Use DSS=False
Use Fixed Start Time=True
Fixed Start Date/Time=05mar2016,00:15
Is Critical Boundary=False
Boundary Location=LATERAL1        ,LATERAL1        ,4571.366,        ,                ,                ,                ,                                ,
Interval=1MIN
Flow Hydrograph= 4321
       0       0       0       0       0       0       0       0       0       0
       0       0       0       0       0       0       0       0       0       0
       0       0       0       0       0      .1      .1      .1      .1      .1
      .1      .1      .1      .2      .2      .2      .2      .2      .3      .3
      .3      .4      .4      .4      .5      .5      .5      .6      .6      .7
      .7      .8      .8      .9       1       1     1.1     1.2     1.2     1.3
     1.4     1.5     1.5     1.6     1.7     1.8     1.9       2     2.1     2.2
     2.3     2.4     2.5     2.6     2.7     2.8       3     3.1     3.2     3.3
     3.5     3.6     3.7     3.9       4     4.2     4.3     4.5     4.6     4.8
       5     5.1     5.3     5.5     5.7     5.9       6     6.2     6.4     6.6
     6.8       7     7.3     7.5     7.7     7.9     8.1     8.4     8.6     8.9
     9.1     9.4     9.6     9.9    10.1    10.4    10.7    10.9    11.2    11.5
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Stage Hydrograph TW Check=0
Use DSS=False
Use Fixed Start Time=True
Fixed Start Date/Time=05mar2016,00:15
Is Critical Boundary=False
Boundary Location=ARROYOELZORRO   ,ARRIBALAT1      ,0       ,        ,                ,                ,                ,                                ,
Friction Slope=0.0008969,0
Precipitation Mode=Disable
Wind Mode=No Wind Forces
Air Density Mode=Specified
Met BC=Precipitation|Expanded View=0
Met BC=Precipitation|Point Interpolation=Nearest
Met BC=Precipitation|Gridded Source=DSS
Met BC=Evapotranspiration|Expanded View=0
Met BC=Evapotranspiration|Point Interpolation=Nearest
Met BC=Evapotranspiration|Gridded Source=DSS
Met BC=Wind Speed|Expanded View=0
Met BC=Wind Speed|Point Interpolation=Nearest
Met BC=Wind Speed|Gridded Source=DSS
Met BC=Wind Direction|Expanded View=0
Met BC=Wind Direction|Point Interpolation=Nearest
Met BC=Wind Direction|Gridded Source=DSS
Met BC=Wind Velocity X|Expanded View=0
Met BC=Wind Velocity X|Point Interpolation=Nearest
Met BC=Wind Velocity X|Gridded Source=DSS
Met BC=Wind Velocity Y|Expanded View=0
Met BC=Wind Velocity Y|Point Interpolation=Nearest
Met BC=Wind Velocity Y|Gridded Source=DSS
Met BC=Air Density|Mode=Constant
Met BC=Air Density|Expanded View=0
Met BC=Air Density|Constant Value=1.225
Met BC=Air Density|Constant Units=kg/m3
Met BC=Air Density|Point Interpolation=Nearest
Met BC=Air Density|Gridded Source=DSS
Met BC=Air Temperature|Expanded View=0
Met BC=Air Temperature|Point Interpolation=Nearest
Met BC=Air Temperature|Gridded Source=DSS
Met BC=Humidity|Expanded View=0
Met BC=Humidity|Point Interpolation=Nearest
Met BC=Humidity|Gridded Source=DSS
Met BC=Air Pressure|Mode=Constant
Met BC=Air Pressure|Expanded View=0
Met BC=Air Pressure|Constant Value=1013.2
Met BC=Air Pressure|Constant Units=mb
Met BC=Air Pressure|Point Interpolation=
Met BC=Air Pressure|Gridded Source=DSS
Non-Newtonian Method= 0 ,
Non-Newtonian Constant Vol Conc=0
Non-Newtonian Yield Method= 0 ,
Non-Newtonian Yield Coef=0, 0
User Yeild=   0
Non-Newtonian Sed Visc= 0 ,
Non-Newtonian Obrian B=0
User Viscosity=0
User Viscosity Ratio=0
Herschel-Bulkley Coef=0, 0
Clastic Method= 0 ,
Coulomb Phi=0
Voellmy X=0
Non-Newtonian Hindered FV= 0
Non-Newtonian FV K=0
Non-Newtonian ds=0
Non-Newtonian Max Cv=0
Non-Newtonian Bulking Method= 0 ,
Non-Newtonian High C Transport= 0 ,
Lava Activation= 0
Temperature=1300,15,,15,14,980
Heat Ballance=1,1200,0.5,1,70,0.95
Viscosity=1000,,,
Profile Coefficient=4,1.3,
Lava Param=,2500,

--- HECRAS_v1.g02 (geometry) ---

Geom Title=HECRAS_V2a
Program Version=6.50

River Reach=ARROYOELZORRO   ,ARRIBALAT1
Reach XY= 30
    1080707.4374    1573339.5833    1080237.7982    1573498.1347
    1079862.9313    1573168.1895    1079320.6178    1573033.8194
    1079221.6866    1572869.4247    1078253.1058    1572618.3051
    1078094.2524    1572733.3828     1077901.525    1572656.1992
    1077773.5463    1572795.8368    1077590.4555    1572744.3908
    1077195.6486    1573072.3463    1076992.2968    1573064.6889
    1076912.2578    1573236.1591    1076722.9953    1573202.6476
    1076612.4146    1573358.3916    1076411.5354    1573301.7432
     1076266.837    1573437.2883    1076101.9001    1573337.8544
    1075314.2113    1573352.5123    1075021.8357    1573164.1616
    1074762.1036    1573307.0204    1074809.0672    1573474.3696
     1074606.396     1573339.961    1074520.4062    1573461.8019
    1074456.1675    1573323.7608    1074343.8516    1573398.9026
    1074180.2065    1573289.1003     1074305.487    1573190.8074
    1074104.9324     1572975.833    1073782.6483    1573130.3062

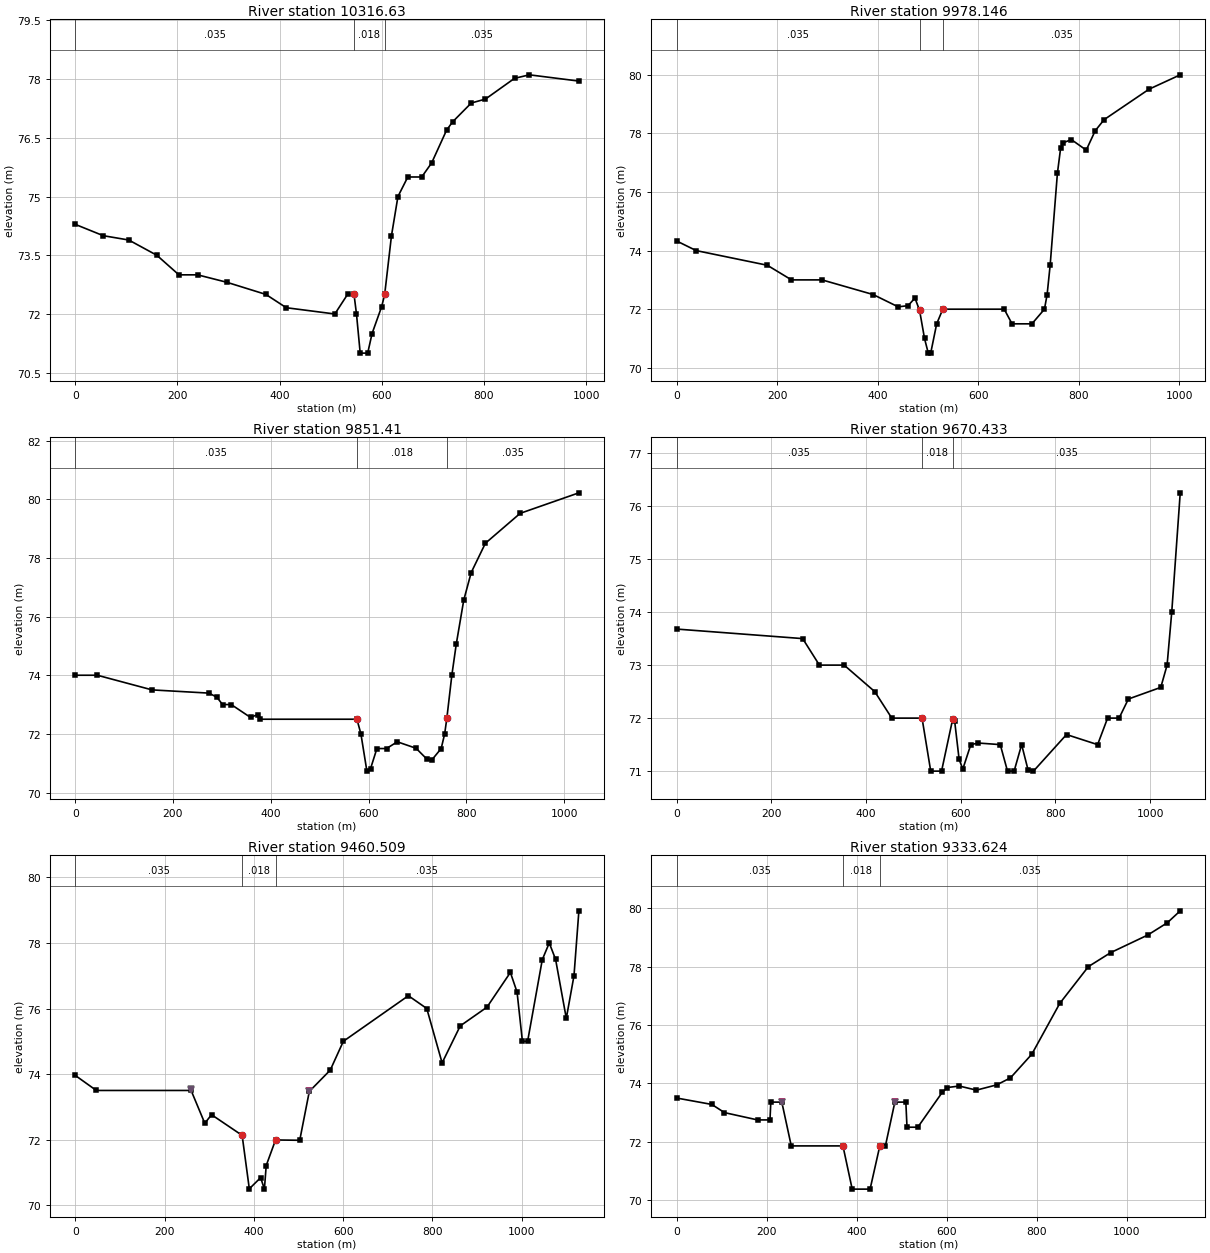
Type RM Length L Ch R = 1 ,10316.63,326.71,338.48,272.19
XS GIS Cut Line= 4
    1080327.0311    1572922.9204    1080508.3292    1573234.2431
    1080782.3396     1573544.788    1080904.0514    1573717.6348
#Sta/Elev= 30
       0   74.29   54.96      74   104.8   73.89  159.75    73.5  202.95      73
  239.59      73  296.77   72.81  373.18    72.5  413.09   72.16  508.12      72
  533.01    72.5  545.68    72.5   550.5      72  557.78      71  572.44      71
  580.98    71.5  599.85   72.19  605.68    72.5  618.98      74  631.62      75
  650.95    75.5  678.17    75.5  697.65   75.86  726.96    76.7  738.77   76.91
  775.18   77.39  802.87   77.49   859.8   78.02  888.92   78.11  985.81   77.95
#Mann= 3 ,0,0
       0    .035       0  545.68    .018       0  605.68    .035       0
Bank Sta=545.68,605.68
XS Rating Curve= 0 ,0
Exp/Cntr=0.3,0.1

Type RM Length L Ch R = 1 ,9978.146,130.71,126.74,122.71
XS GIS Cut Line= 4
    1080274.1143    1572941.9705    1080377.2263    1573318.1105
    1080566.5631    1573560.6676    1080749.9587    1573803.7037
#Sta/Elev= 30
       0   74.33   39.05      74  180.51    73.5  228.69      73  289.46      73
  391.12    72.5  440.96   72.08  460.63   72.12  474.33   72.38  483.53   71.96
  493.37      71  500.83    70.5  505.67    70.5  517.56    71.5  529.76      72
  651.94      72  667.53    71.5  707.05    71.5  732.02      72  737.33    72.5
  743.35    73.5  757.79   76.64  764.21    77.5  769.34   77.68  785.48   77.79
  815.14   77.43  832.97   78.09  850.74   78.47  940.18   79.51 1002.19      80
#Mann= 3 ,0,0
       0    .035       0  483.53    .018       0  529.76    .035       0
Bank Sta=483.53,529.76
XS Rating Curve= 0 ,0
Exp/Cntr=0.3,0.1

Type RM Length L Ch R = 1 ,9851.41 ,150.51,180.98,211.46
XS GIS Cut Line= 4
    1080240.2476    1572950.4372    1080352.9475    1573475.0008
     1080541.224    1573663.8071    1080671.8044    1573849.7252
#Sta/Elev= 30
       0      74   45.17      74  157.19    73.5  273.69   73.39  289.76   73.25
  301.48      73  319.19      73  358.67   72.56  373.11   72.66  378.61    72.5
  576.26    72.5  584.43      72  596.67   70.73  604.06   70.81  617.13    71.5
  636.79    71.5  658.87   71.73  697.24   71.51  719.35   71.14  728.91    71.1
  748.62    71.5  755.78      72  760.27   72.54  770.45      74  779.39   75.05
   794.8   76.56     810    77.5  839.05    78.5  910.19   79.52 1030.36   80.22
#Mann= 3 ,0,0
       0    .035       0  576.26    .018       0  760.27    .035       0
Bank Sta=576.26,760.27
XS Rating Curve= 0 ,0
Exp/Cntr=0.3,0.1

Type RM Length L Ch R = 1 ,9670.433,205.56,209.92,222.26
XS GIS Cut Line= 4
    1080202.1475    1572954.6705    1080254.1813     1573378.091
    1080194.4311    1573650.0588     1080377.746    1573958.0837
#Sta/Elev= 30
       0   73.68  266.27    73.5  301.61      73  353.82      73  418.46    72.5
  454.44      72  518.34      72  536.65      71  559.54      71  583.23   71.99
  587.25   71.94  596.64   71.22  604.48   71.04  621.28    71.5  637.17   71.53
   683.5    71.5  698.79      71  712.74      71  728.62    71.5  741.99   71.03
  753.58      71  823.39   71.69  889.07    71.5  910.13      72   934.4      72
  953.99   72.36 1022.46   72.58 1035.75      73 1045.59      74 1063.51   76.25
#Mann= 3 ,0,0
       0    .035       0  518.34    .018       0  583.23    .035       0
Bank Sta=518.34,583.23
XS Rating Curve= 0 ,0
Exp/Cntr=0.3,0.1

Type RM Length L Ch R = 1 ,9460.509,133.24,126.88,116.59
XS GIS Cut Line= 5
    1080161.9306    1572958.9446    1080152.5873    1573251.4818
    1080095.9811    1573338.1023    1079991.8435    1573479.1967
    1080234.5059    1573980.1218
#Sta/Elev= 30
       0   73.96   47.29    73.5  259.57    73.5  290.18    72.5  305.36   72.76
  373.85   72.13  389.93    70.5  415.31   70.84   423.7   70.49  427.79   71.21
  448.67   71.99  502.86   71.98  524.29   73.47  571.18   74.12  600.56      75
  746.21   76.39  787.41      76  821.77   74.34  862.37   75.47  922.19   76.04
  974.68    77.1  989.65    76.5 1001.61      75 1013.29      75 1046.14   77.49
 1061.74      78 1075.93    77.5 1099.93    75.7 1117.14      77 1128.13   78.98
#Mann= 3 ,0,0
       0    .035       0  373.85    .018       0  448.67    .035       0
Levee=-1,258.25,73.53,-1,524.29,73.47035,,	340
Bank Sta=373.85,448.67
XS Rating Curve= 0 ,0
Exp/Cntr=0.3,0.1

Type RM Length L Ch R = 1 ,9333.624,62.94,98.04,133.14
XS GIS Cut Line= 5
    1080109.3166     1572950.726    1080050.9978    1573155.8972
     1079943.577     1573386.726    1079923.5675    1573427.4895
    1079827.7994    1574025.7831
#Sta/Elev= 30
       0    73.5   78.34   73.28   106.5      73  179.98   72.75  207.56   72.75
  209.43   73.36  233.88   73.36  254.88   71.86  369.71   71.86  390.29   70.38
  430.04   70.38  451.65   71.86  464.08   71.86  485.08   73.36  509.48   73.36
  512.06    72.5  536.06    72.5  590.18   73.69  601.89   73.86  628.31   73.91
   666.3   73.77  711.47   73.95  741.98   74.19  789.41      75  851.53   76.74
  915.15      78  964.85   78.48 1046.93   79.08 1090.41    79.5 1119.22   79.91
#Mann= 3 ,0,0
       0    .035       0  369.71    .018       0  451.65    .035       0
Levee=-1,233.88,73.36314,-1,485.08,73.36273,	341,	340
Bank Sta=369.71,451.65
XS Rating Curve= 0 ,0
Exp/Cntr=0.3,0.1

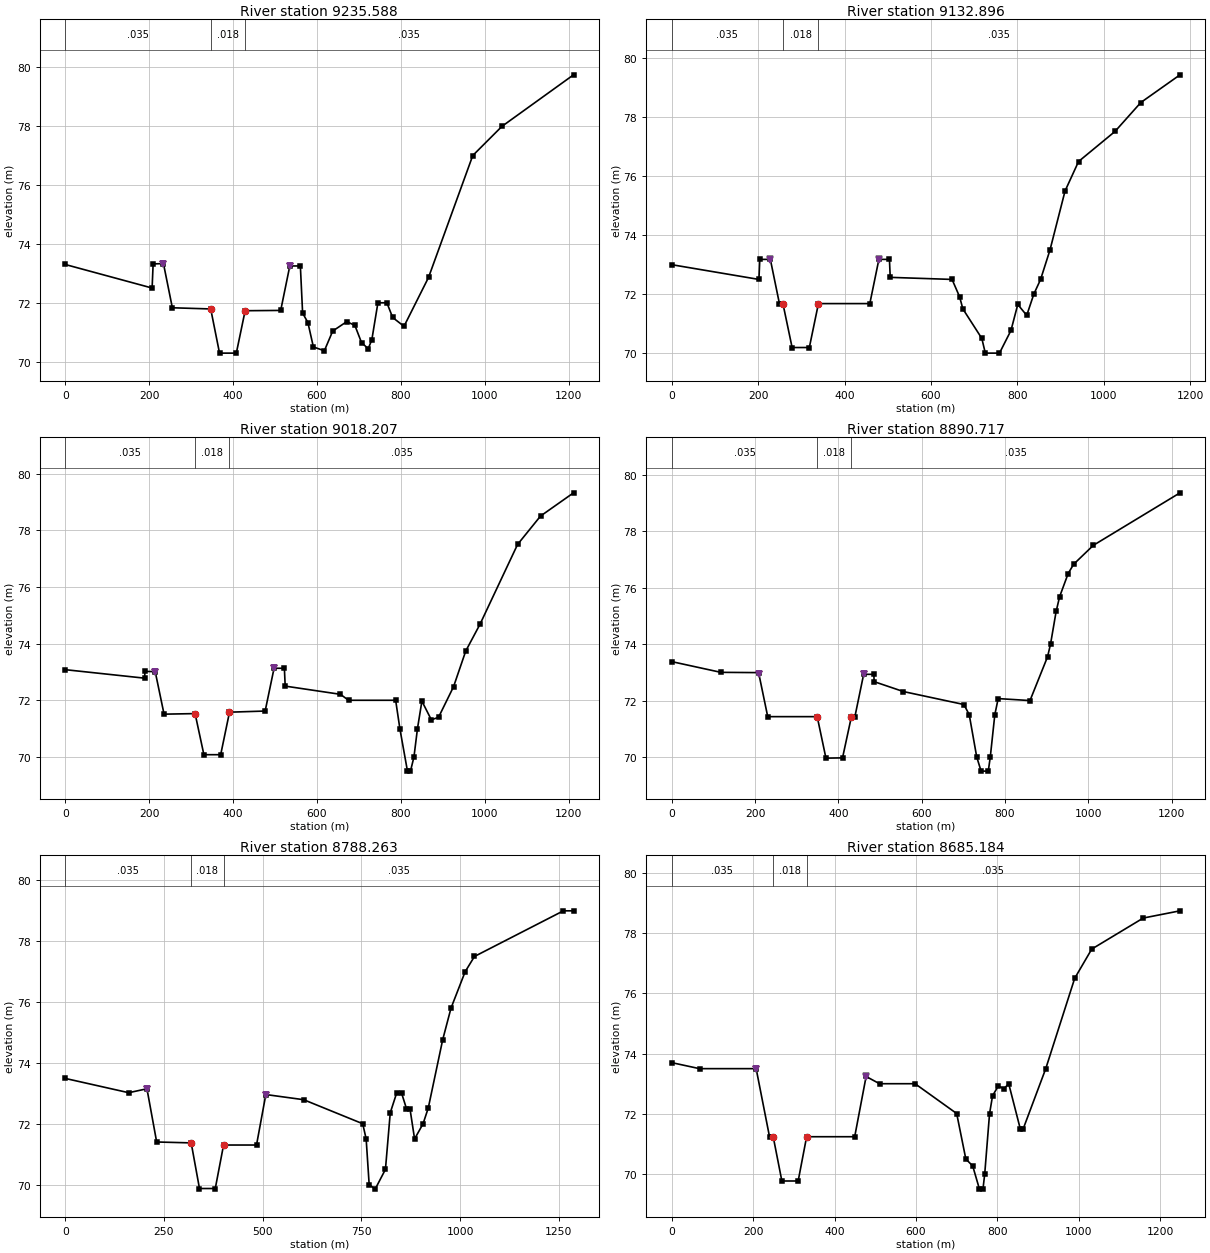
Type RM Length L Ch R = 1 ,9235.588,137.8,102.69,67.58
XS GIS Cut Line= 4
    1080083.4932    1572937.8142    1079991.2064    1573234.1482
     1079861.851     1573271.218    1079719.4258    1574024.0897
#Sta/Elev= 30
       0    73.3  207.07    72.5  209.48   73.32   234.1   73.33  255.29   71.83
   346.7   71.79   367.7   70.29   407.7   70.29   428.7   71.73  513.46   71.74
  535.12   73.25   560.3   73.25  565.65   71.65  578.22   71.33   591.3    70.5
  617.46   70.37  637.36   71.04  670.92   71.36  690.23   71.23  705.96   70.65
  721.87   70.44  730.54   70.74  745.07      72   766.4      72  780.24    71.5
  807.22    71.2  865.68   72.86  971.08      77 1040.58   77.99 1211.16   79.74
#Mann= 3 ,0,0
       0    .035       0   346.7    .018       0   428.7    .035       0
Levee=-1,234.1,73.32671,-1,535.13,73.2461,	341,	340
Bank Sta=346.7,428.7
XS Rating Curve= 0 ,0
Exp/Cntr=0.3,0.1

Type RM Length L Ch R = 1 ,9132.896,141.46,114.69,87.92
XS GIS Cut Line= 3
    1079992.4764    1572899.5025    1079778.3077     1573359.714
    1079621.0007    1574009.6964
#Sta/Elev= 30
       0      73  201.91    72.5  203.94   73.18  228.34   73.18  249.34   71.68
  257.43   71.68  278.72   70.19  318.56   70.19  339.62   71.68  458.54   71.68
  479.54   73.18  503.94   73.18  505.77   72.57  648.86    72.5  666.35   71.91
  673.85    71.5  717.72    70.5  725.81      70  758.58      70   785.2   70.77
  800.92   71.65  821.67   71.28  838.01      72  853.74    72.5  875.49    73.5
  910.34    75.5   941.6    76.5 1025.96   77.52 1085.63    78.5 1176.35   79.44
#Mann= 3 ,0,0
       0    .035       0  257.43    .018       0  339.62    .035       0
Levee=-1,228.34,73.17561,-1,479.54,73.17561,	341,	340
Bank Sta=257.43,339.62
XS Rating Curve= 0 ,0
Exp/Cntr=0.3,0.1

Type RM Length L Ch R = 1 ,9018.207,100.72,127.49,154.26
XS GIS Cut Line= 5
    1079875.0012    1572860.7674    1079739.5342    1573104.6079
    1079763.8079    1573214.4359    1079771.7076    1573257.0082
    1079542.2605    1573998.6897
#Sta/Elev= 30
       0   73.08  189.26   72.78  189.98   73.02  214.44   73.01   235.5   71.51
  309.42   71.53  330.42   70.08  370.42   70.08  391.42   71.58  476.37   71.62
  497.57   73.13  522.19   73.13  524.11    72.5  655.81   72.21  674.96      72
  787.28      72  797.42   70.99  815.42    69.5   822.6    69.5  830.88      70
  839.26      71  849.81   71.97  872.36   71.31  889.48    71.4  925.24   72.48
  954.33   73.74  988.14   74.68 1077.82    77.5 1132.44    78.5 1211.08   79.32
#Mann= 3 ,0,0
       0    .035       0  309.42    .018       0  391.42    .035       0
Levee=-1,214.44,73.01493,-1,497.56,73.12814,	341,	340
Bank Sta=309.42,391.42
XS Rating Curve= 0 ,0
Exp/Cntr=0.3,0.1

Type RM Length L Ch R = 1 ,8890.717,68.21,102.45,136.69
XS GIS Cut Line= 3
    1079795.4143     1572828.594    1079590.7473    1573268.3881
    1079386.4735    1573974.1363
#Sta/Elev= 30
       0   73.38  117.92      73  208.61   72.99  230.48   71.43  349.22   71.43
  370.18   69.96  410.01   69.97  431.31   71.43  439.68   71.43  460.68   72.93
  485.09   72.93   485.9   72.67  555.83   72.32  701.25   71.86  714.03    71.5
  732.03      70  742.52    69.5  759.73    69.5  764.57      70  775.42    71.5
  783.49   72.07  859.84      72  901.93   73.55  909.14      74  922.59   75.16
  930.92   75.68   951.4    76.5  964.59   76.83 1011.85    77.5  1219.8   79.36
#Mann= 3 ,0,0
       0    .035       0  349.22    .018       0  431.31    .035       0
Levee=-1,209.48,72.93305,-1,460.68,72.93301,	341,	340
Bank Sta=349.22,431.31
XS Rating Curve= 0 ,0
Exp/Cntr=0.3,0.1

Type RM Length L Ch R = 1 ,8788.263,137.11,103.08,68.73
XS GIS Cut Line= 4
    1079759.8543     1572810.814     1079645.554    1573077.6204
    1079521.3471    1573116.0751    1079286.2491    1573950.7471
#Sta/Elev= 30
       0   73.49  160.87   73.02  207.05   73.15  231.64    71.4  319.07   71.37
  340.07   69.87  380.07   69.87  401.07    71.3  484.52    71.3  508.09   72.96
  603.95   72.79   753.5      72  762.21    71.5  769.83      70  785.04   69.85
  811.06    70.5  823.24   72.36   839.2      73   852.1      73  864.25    72.5
   873.1    72.5  884.88    71.5  906.36      72  919.57   72.52     956   74.76
  977.07    75.8 1012.99      77 1036.56    77.5 1261.77      79 1287.43      79
#Mann= 3 ,0,0
       0    .035       0  319.07    .018       0  401.07    .035       0
Levee=-1,206.94,73.15,-1,508.41,72.96,	341,	340
Bank Sta=319.07,401.07
XS Rating Curve= 0 ,0
Exp/Cntr=0.3,0.1

Type RM Length L Ch R = 1 ,8685.184,132.08,96,60.24
XS GIS Cut Line= 5
    1079689.4749    1572775.0158    1079573.3755    1572915.1394
    1079527.1627    1573013.1873     1079441.341    1573198.8588
    1079203.8048    1573913.9964
#Sta/Elev= 30
       0    73.7   68.38    73.5  207.45    73.5  240.31   71.24  249.34   71.24
  270.65   69.77  310.66   69.77  331.47   71.24  449.51   71.24  477.54   73.24
   510.5      73  597.78      73  699.99   72.01  722.46    70.5  739.33   70.27
  755.91    69.5  764.56    69.5  768.83      70  780.68      72  788.11    72.6
  802.42   72.93  815.94   72.83  827.78      73  856.22    71.5  863.31    71.5
  918.75    73.5  989.86    76.5 1031.74   77.47 1158.17    78.5 1248.47   78.74
#Mann= 3 ,0,0
       0    .035       0  249.34    .018       0  331.47    .035       0
Levee=-1,207.6,73.5,-1,477.97,73.24,	341,	340
Bank Sta=249.34,331.47
XS Rating Curve= 0 ,0
Exp/Cntr=0.3,0.1

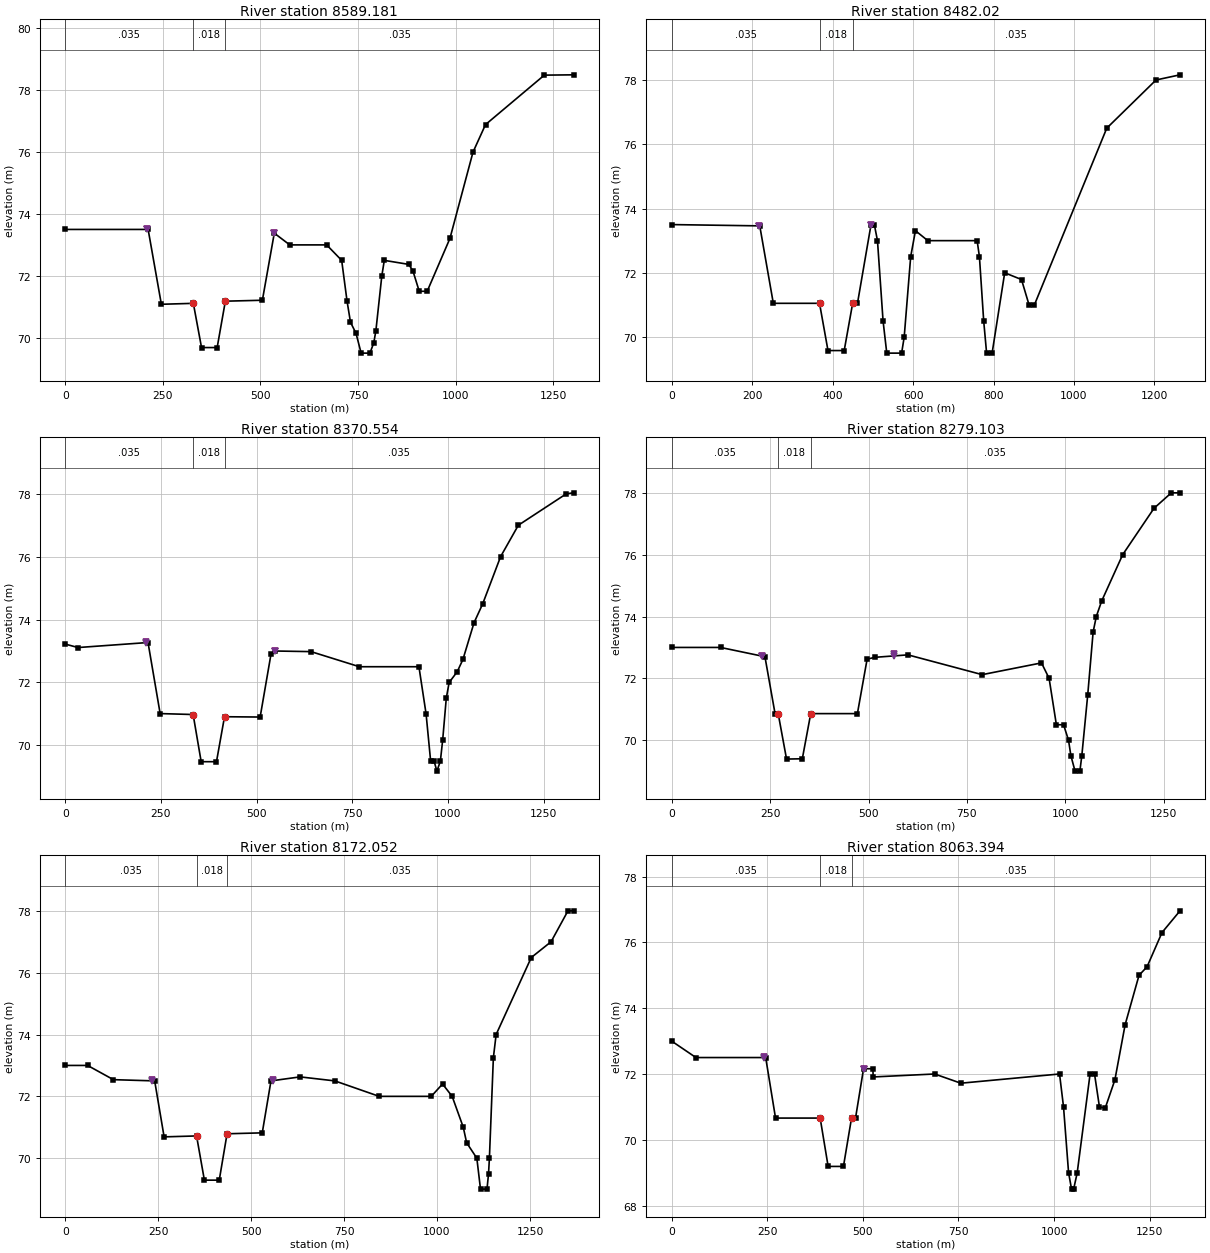
Type RM Length L Ch R = 1 ,8589.181,71.26,107.16,143.04
XS GIS Cut Line= 5
    1079531.8761    1572688.6196    1079402.7592    1572950.0285
    1079453.2203    1573057.3448    1079460.9676    1573080.2037
    1079160.4004    1573894.0637
#Sta/Elev= 30
       0    73.5  212.39    73.5  246.26   71.08  328.15   71.11  349.15   69.68
  389.15   69.68  410.15   71.18  504.98   71.21  535.47   73.38  575.11      73
  669.62      73  708.06    72.5  721.73   71.19  730.62    70.5  744.79   70.14
  757.94    69.5  780.38    69.5  790.23   69.83  795.63   70.22  810.78   71.99
  817.23    72.5  879.82   72.37   890.5   72.16  906.69    71.5  927.06    71.5
  985.34   73.21 1044.39      76 1076.42   76.89 1227.07   78.49 1301.87    78.5
#Mann= 3 ,0,0
       0    .035       0  328.15    .018       0  410.15    .035       0
Levee=-1,208.23,73.53,-1,535.71,73.38,	341,	340
Bank Sta=328.15,410.15
XS Rating Curve= 0 ,0
Exp/Cntr=0.3,0.1

Type RM Length L Ch R = 1 ,8482.02 ,74.63,111.47,148.33
XS GIS Cut Line= 4
    1079486.3677    1572661.6321    1079419.3723    1572857.7406
    1079292.7963    1573129.7306    1079063.1393    1573850.2486
#Sta/Elev= 30
       0    73.5  218.95   73.46  252.64   71.05  367.49   71.05  388.54   69.58
  428.82   69.58  449.82   71.05  461.84   71.05  495.23   73.48  503.71    73.5
  511.53      73  525.43    70.5  534.64    69.5  571.54    69.5  577.94      70
  594.06    72.5   605.9   73.31  636.65      73  759.24      73  764.93    72.5
  775.55    70.5  782.78    69.5  796.46    69.5  827.74      72  869.52   71.79
  888.29      71  901.54      71 1081.42    76.5 1203.96      78 1263.47   78.16
#Mann= 3 ,0,0
       0    .035       0  367.49    .018       0  449.82    .035       0
Levee=-1,216.11,73.47,-1,495.44,73.49,	341,	340
Bank Sta=367.49,449.82
XS Rating Curve= 0 ,0
Exp/Cntr=0.3,0.1

Type RM Length L Ch R = 1 ,8370.554,128.33,91.45,54.52
XS GIS Cut Line= 6
    1079448.3734    1572649.6729    1079387.8709    1572843.0808
    1079344.2332    1572935.8468    1079236.2393    1572961.8225
     1079212.153    1572968.0202    1078982.7058    1573824.8486
#Sta/Elev= 30
       0   73.22   33.56   73.11  216.39   73.27  248.05   71.01  334.24   70.98
  355.24   69.48  395.24   69.48  416.24   70.91  509.33    70.9  537.96   72.92
  548.92      73  642.28   72.98  768.63    72.5  924.21    72.5  942.88      71
  954.78    69.5  963.72    69.5   971.2   69.18  980.22    69.5  986.24   70.17
  995.65    71.5 1003.15      72 1024.17   72.34 1039.11   72.73 1068.18    73.9
 1090.81    74.5 1137.54      76 1183.97      77 1309.43      78 1328.13   78.03
#Mann= 3 ,0,0
       0    .035       0  334.24    .018       0  416.24    .035       0
Levee=-1,212.17,73.3,-1,549.07,73.01,	341,	340
Bank Sta=334.24,416.24
XS Rating Curve= 0 ,0
Exp/Cntr=0.3,0.1

Type RM Length L Ch R = 1 ,8279.103,143.28,107.05,70.86
XS GIS Cut Line= 4
    1079359.4733    1572590.4061    1079272.7216    1572789.4938
    1079146.1456    1573061.4837    1078894.6523    1573793.5218
#Sta/Elev= 30
       0      73  124.03      73  236.91    72.7  262.57   70.86  270.55   70.86
  291.77   69.39  331.85    69.4  353.22   70.86  471.77   70.86  496.41   72.62
  515.77   72.68  600.11   72.76  788.72   72.12  939.38    72.5  958.72      72
  977.18    70.5  995.44    70.5 1008.04      70 1014.04    69.5  1024.6      69
 1036.88      69 1041.74   69.49 1056.77   71.46 1070.54    73.5 1078.59      74
 1092.19    74.5  1145.6      76 1225.16    77.5 1269.15      78  1291.2      78
#Mann= 3 ,0,0
       0    .035       0  270.55    .018       0  353.22    .035       0
Levee=-1,229.52,72.72,-1,564.73,72.8,	341,	340
Bank Sta=270.55,353.22
XS Rating Curve= 0 ,0
Exp/Cntr=0.3,0.1

Type RM Length L Ch R = 1 ,8172.052,72.42,108.66,144.91
XS GIS Cut Line= 6
    1079236.8122    1572529.6153    1079140.6199    1572728.0176
    1079096.0536    1572807.9575    1079149.5197     1572919.071
     1079160.612    1572940.2495    1078827.2364    1573784.8012
#Sta/Elev= 30
       0      73   60.19      73  129.66   72.54  240.63    72.5  266.01   70.69
  353.32   70.72  374.32   69.29  414.32   69.29  435.32   70.79  529.97   70.82
  553.46    72.5   631.7   72.63  725.27    72.5  844.52      72  984.55      72
 1014.89    72.4 1040.75      72 1070.66      71 1079.68    70.5 1107.13      70
 1116.99      69 1134.46      69  1138.6    69.5 1140.93      70  1151.6   73.25
 1159.01      74 1253.53   76.49 1306.77      77 1352.23      78  1367.2      78
#Mann= 3 ,0,0
       0    .035       0  353.32    .018       0  435.32    .035       0
Levee=-1,234.25,72.52,-1,559.21,72.52,	341,	340
Bank Sta=353.32,435.32
XS Rating Curve= 0 ,0
Exp/Cntr=0.3,0.1

Type RM Length L Ch R = 1 ,8063.394,75.89,111.57,147.24
XS GIS Cut Line= 4
    1079207.1788    1572509.5069    1079114.7195    1572715.9643
    1078988.1435    1572987.9543    1078734.1028    1573749.8761
#Sta/Elev= 30
       0      73   63.41    72.5  245.85    72.5  271.62   70.66  388.31   70.66
  409.19   69.19  449.23   69.19  470.35   70.66  480.82   70.66  501.82   72.16
  526.22   72.16  526.96   71.91  687.74      72  756.24   71.72 1014.35      72
 1024.78      71 1037.96      69 1045.76    68.5 1051.26    68.5 1060.57      69
 1094.21      72 1105.86      72 1118.71      71  1133.7   70.96 1159.07   71.82
  1185.9    73.5  1222.2      75 1243.25   75.26 1282.31    76.3 1329.37   76.96
#Mann= 3 ,0,0
       0    .035       0  388.31    .018       0  470.35    .035       0
Levee=-1,240.56,72.51,-1,501.81,72.15994,	341,	340
Bank Sta=388.31,470.35
XS Rating Curve= 0 ,0
Exp/Cntr=0.3,0.1

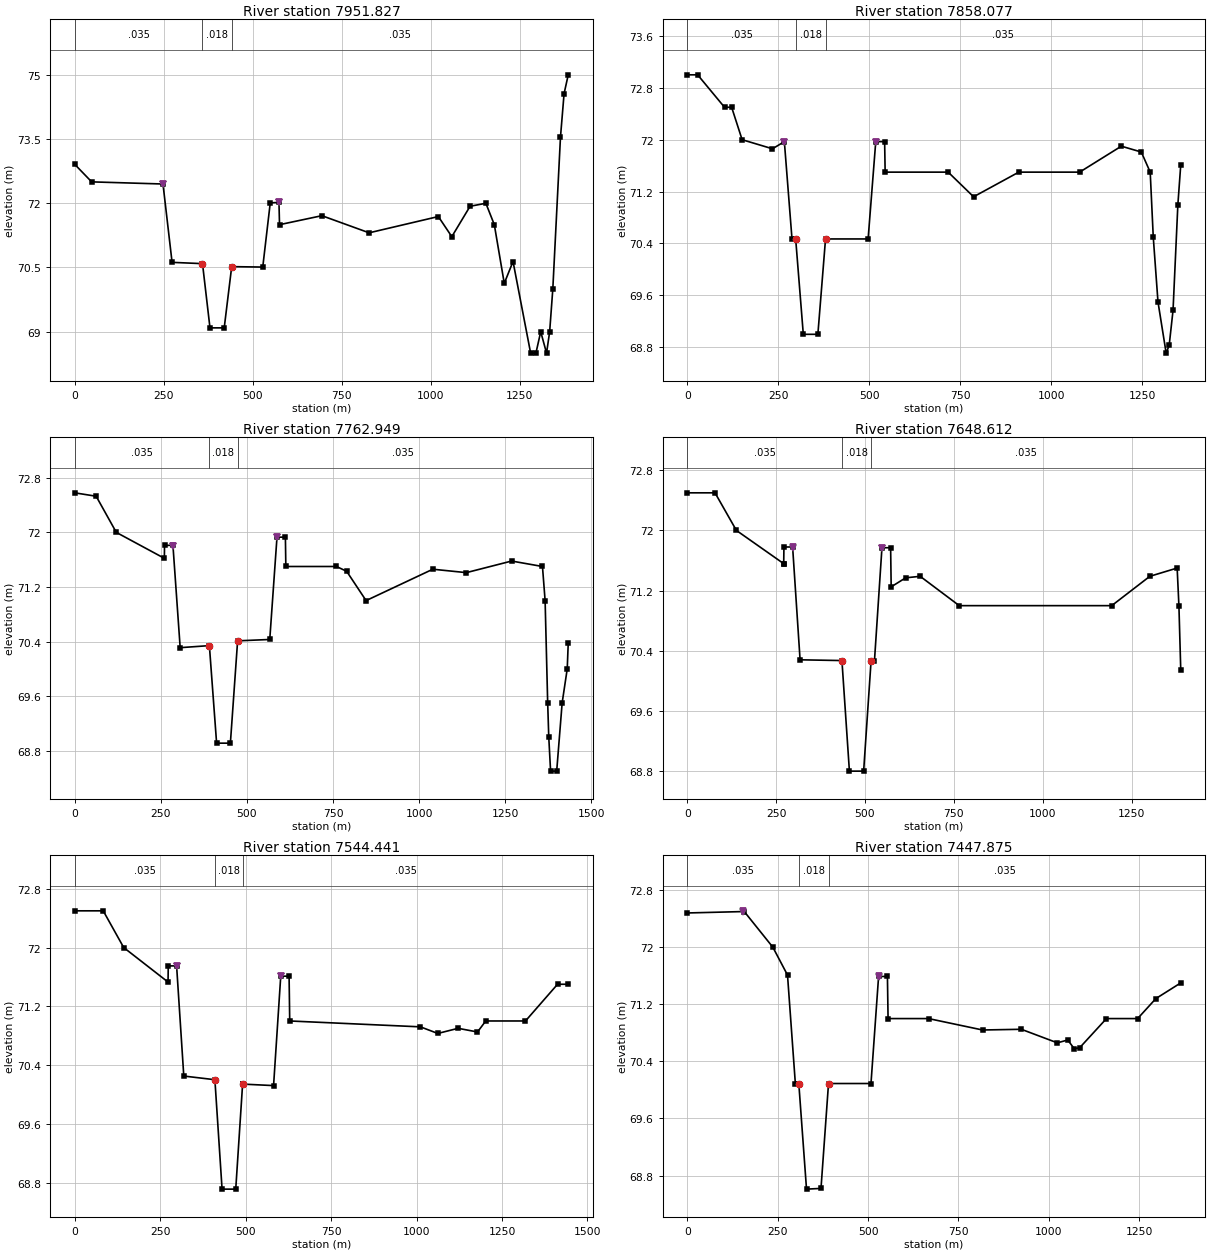
Type RM Length L Ch R = 1 ,7951.827,132.49,93.75,55.01
XS GIS Cut Line= 6
    1079179.6621    1572494.6902    1079087.3428     1572703.224
    1079045.2535    1572789.9658    1078932.8887    1572820.4592
    1078914.0199    1572841.8243    1078634.6193     1573714.951
#Sta/Elev= 30
       0   72.91   47.57    72.5  247.93   72.45  273.46   70.62   358.9   70.59
   379.9   69.09   419.9   69.09   440.9   70.52  528.14   70.51   549.2   72.01
  573.68   72.02  575.23    71.5  694.23   71.71  826.92   71.31  1021.3   71.69
 1059.14   71.22 1110.43   71.93 1154.79      72 1178.52    71.5 1206.48   70.13
 1231.08   70.64 1280.53    68.5 1295.36    68.5 1308.85      69 1325.22    68.5
 1333.96      69 1342.84      70 1364.31   73.54 1374.45   74.56 1386.14      75
#Mann= 3 ,0,0
       0    .035       0   358.9    .018       0   440.9    .035       0
Levee=-1,247.66,72.45,-1,572.62,72.02,	341,	340
Bank Sta=358.9,440.9
XS Rating Curve= 0 ,0
Exp/Cntr=0.3,0.1

Type RM Length L Ch R = 1 ,7858.077,133.73,95.13,56.53
XS GIS Cut Line= 4
    1079064.8327    1572431.4018    1078954.4105    1572645.2909
    1078864.4802    1572883.4531     1078573.765     1573693.996
#Sta/Elev= 30
       0      73   28.62      73  102.49    72.5  122.09    72.5  150.87      72
  234.28   71.86  266.96   71.97  287.96   70.47  298.06   70.47  319.05      69
  359.06      69  380.13   70.47  497.16   70.47  518.16   71.97  542.56   71.97
  543.98    71.5  717.22    71.5  787.06   71.12  911.27    71.5 1078.53    71.5
 1193.12    71.9 1247.99   71.81 1272.48    71.5 1280.85    70.5 1293.84    69.5
 1316.32   68.71 1324.62   68.83 1335.22   69.37  1348.5      71 1356.39   71.61
#Mann= 3 ,0,0
       0    .035       0  298.06    .018       0  380.13    .035       0
Levee=-1,267.02,71.96504,-1,518.24,71.9697,	341,	340
Bank Sta=298.06,380.13
XS Rating Curve= 0 ,0
Exp/Cntr=0.3,0.1

Type RM Length L Ch R = 1 ,7762.949,78.48,114.34,150.19
XS GIS Cut Line= 6
    1078881.4231    1572348.1108    1078808.8085    1572598.7291
    1078784.9029    1572683.3915    1078852.9902    1572787.2213
    1078860.2564    1572814.6251    1078534.2891    1573687.5401
#Sta/Elev= 30
       0   72.58   62.27   72.53  120.78      72   260.3   71.62  260.85   71.81
  285.25   71.81  306.25   70.31  391.06   70.34  412.06   68.91  452.06   68.91
  473.06   70.41  566.41   70.43  587.41   71.93  611.82   71.93  613.12    71.5
  760.06    71.5  789.68   71.43  846.17      71 1039.93   71.46 1137.27   71.41
 1268.84   71.58 1358.38    71.5 1366.04      71 1373.51    69.5 1376.66      69
 1381.93    68.5 1399.68    68.5 1415.51    69.5 1430.31      70  1433.2   70.38
#Mann= 3 ,0,0
       0    .035       0  391.06    .018       0  473.06    .035       0
Levee=-1,285.33,71.8001,-1,587.45,71.9343,	341,	340
Bank Sta=391.06,473.06
XS Rating Curve= 0 ,0
Exp/Cntr=0.3,0.1

Type RM Length L Ch R = 1 ,7648.612,69.71,104.17,138.64
XS GIS Cut Line= 4
    1078856.8697    1572329.4841    1078785.7915    1572590.9508
    1078698.8347    1572878.1138    1078462.3223    1573660.4468
#Sta/Elev= 24
       0    72.5   78.19    72.5  138.34      72   270.9   71.56  271.41   71.56
  272.06   71.78  296.47   71.78  317.48   70.28  435.19   70.27  456.24    68.8
  496.27    68.8  517.26   70.27  526.77   70.27  547.78   71.77  572.19   71.77
  573.73   71.25  614.48   71.37  655.31   71.39   765.3      71 1194.14      71
 1301.33   71.39  1378.2    71.5 1383.16      71  1388.3   70.15
#Mann= 3 ,0,0
       0    .035       0  435.19    .018       0  517.26    .035       0
Levee=-1,296.55,71.77281,-1,547.83,71.77087,	341,	340
Bank Sta=435.19,517.26
XS Rating Curve= 0 ,0
Exp/Cntr=0.3,0.1

Type RM Length L Ch R = 1 ,7544.441,136.14,96.57,56.98
XS GIS Cut Line= 6
     1078809.668    1572315.7257    1078755.1603    1572583.9023
    1078732.1978    1572678.9464    1078622.8718     1572729.903
    1078603.9276    1572741.1766    1078396.2822    1573647.3234
#Sta/Elev= 24
       0    72.5   83.37    72.5  143.29      72  273.01   71.53  273.66   71.75
  298.06   71.75  319.07   70.25  410.06    70.2  431.06   68.71  471.06   68.71
  491.13   70.14  492.06   70.14  581.73   70.12   602.7   71.61  627.12   71.61
  628.96      71 1011.28   70.92 1062.13   70.83  1121.6    70.9 1178.29   70.85
  1202.4      71  1318.7      71 1412.49    71.5 1443.74    71.5
#Mann= 3 ,0,0
       0    .035       0  410.06    .018       0  492.06    .035       0
Levee=-1,298.06,71.74581,-1,602.76,71.61491,	341,	340
Bank Sta=410.06,492.06
XS Rating Curve= 0 ,0
Exp/Cntr=0.3,0.1

Type RM Length L Ch R = 1 ,7447.875,123.11,84.42,45.74
XS GIS Cut Line= 4
     1078660.612     1572303.449    1078611.3139    1572552.2751
    1078568.3847    1572803.1983    1078364.2781    1573635.2584
#Sta/Elev= 24
       0   72.48  157.71    72.5  236.85      72  277.37   71.61  299.04   70.09
  308.61   70.09  329.93   68.61  369.98   68.62  390.79   70.09  508.24   70.09
  529.28   71.59  553.73   71.59   555.5      71  667.43      71  816.89   70.84
  924.02   70.85 1023.66   70.66 1052.44    70.7 1070.11   70.58  1085.2   70.59
  1159.5      71 1245.72      71 1296.12   71.28 1364.96    71.5
#Mann= 3 ,0,0
       0    .035       0  308.61    .018       0  390.79    .035       0
Levee=-1,153.01,72.51,-1,529.34,71.58852,	341,	340
Bank Sta=308.61,390.79
XS Rating Curve= 0 ,0
Exp/Cntr=0.3,0.1