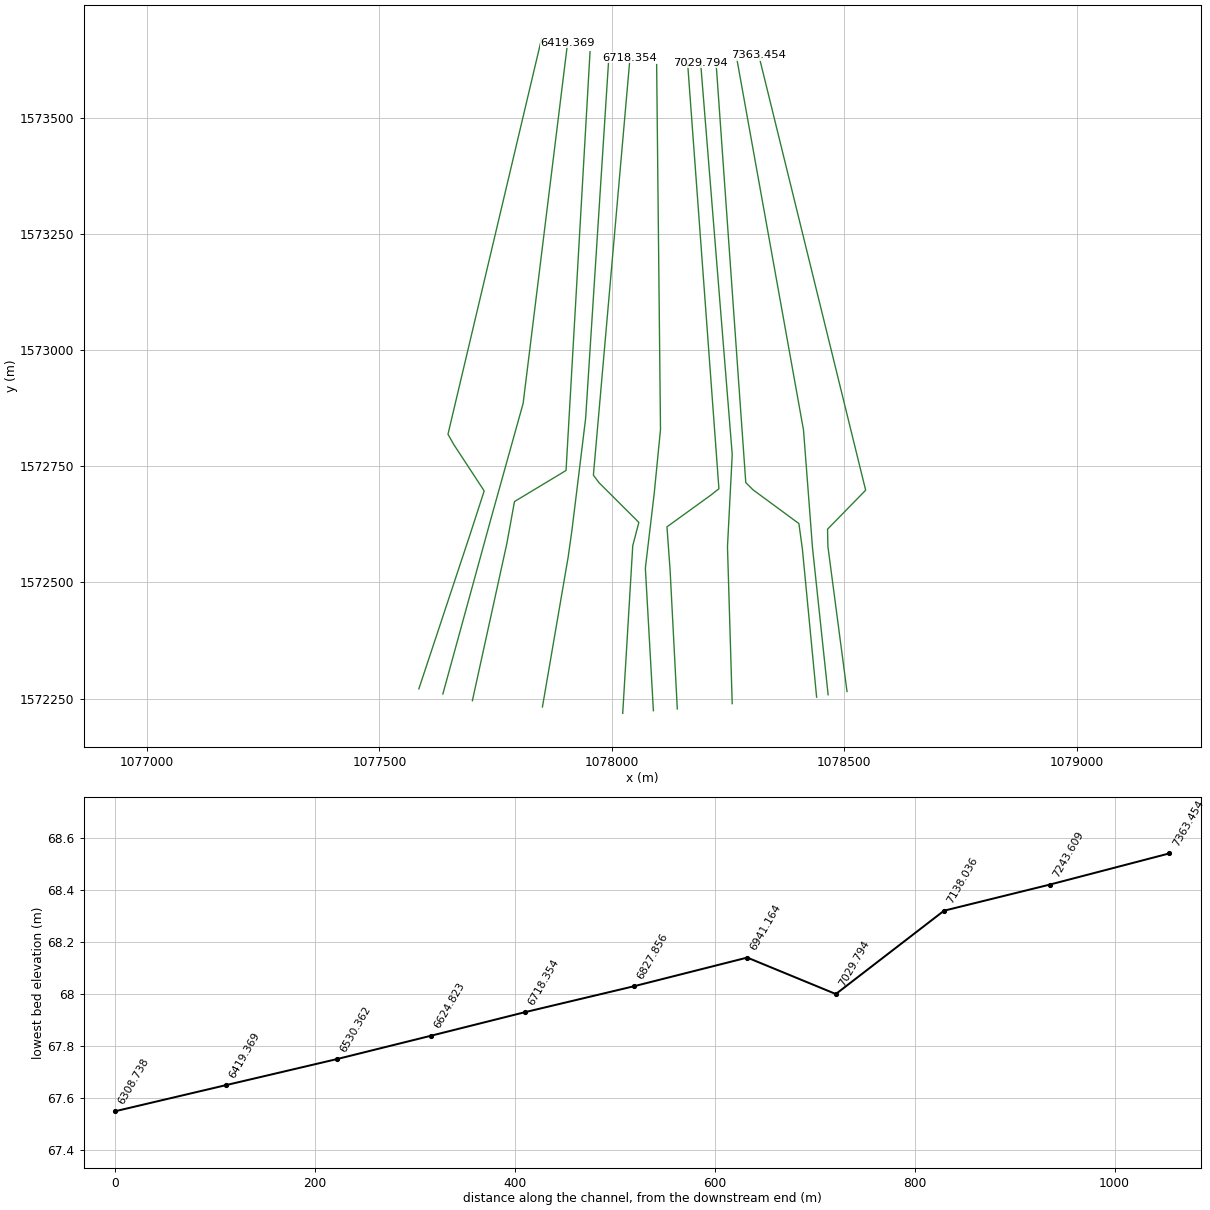
HEC-RAS study HECRAS_v1.prj: HECRAS_v1

--- HECRAS_v1.g02 (geometry) --- (continued)

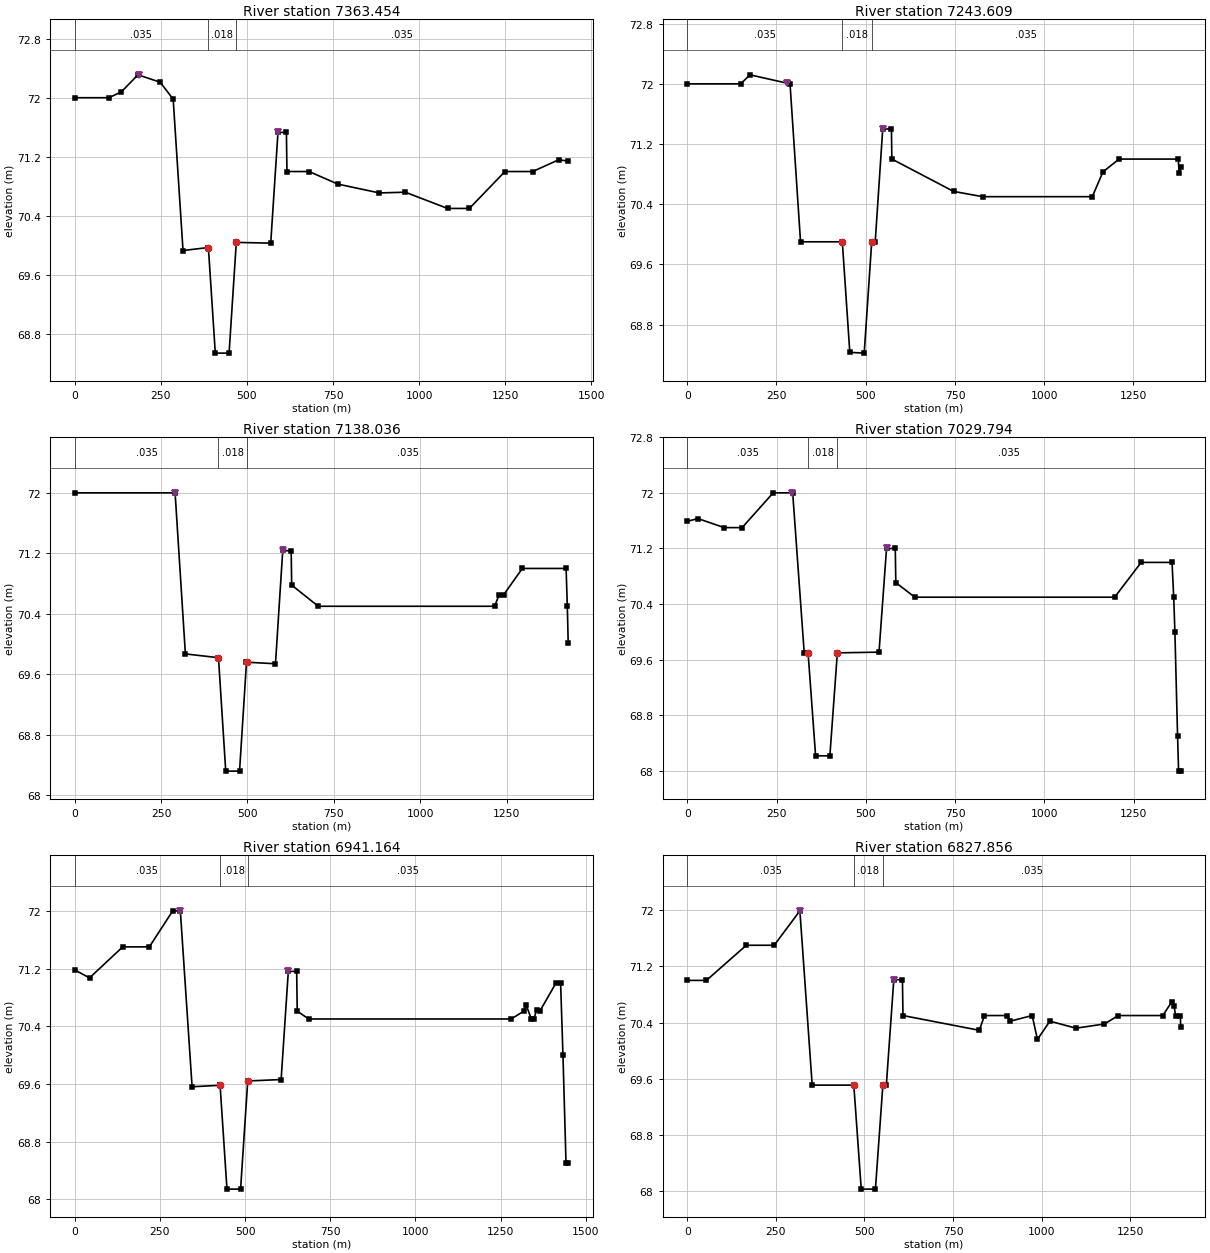
Type RM Length L Ch R = 1 ,7363.454,84.95,119.85,154.72
XS GIS Cut Line= 5
     1078506.095     1572265.349    1078465.0065    1572577.1945
     1078464.185    1572614.5997    1078546.1793     1572698.458
    1078316.2297    1573634.4117
#Sta/Elev= 26
       0      72   99.46      72  135.64   72.08  183.66   72.31   248.2   72.21
  285.92   71.98  314.49   69.93  387.24   69.97  388.18   69.97  408.24   68.54
  448.24   68.54  469.24   70.04  569.16   70.03  590.24   71.53  614.73   71.53
  616.32      71  680.66      71  763.85   70.83   884.7   70.71   959.9   70.72
  1082.7    70.5 1146.02    70.5 1249.41      71 1329.96      71 1405.88   71.16
 1433.03   71.14
#Mann= 3 ,0,0
       0    .035       0  387.24    .018       0  469.24    .035       0
Levee=-1,186.59,72.31,-1,590.23,71.52976,	341,	340
Bank Sta=387.24,469.24
XS Rating Curve= 0 ,0
Exp/Cntr=0.3,0.1

Type RM Length L Ch R = 1 ,7243.609,70.34,105.57,140.83
XS GIS Cut Line= 4
     1078465.455    1572258.3639    1078431.9017    1572573.9409
    1078412.4907    1572827.8406    1078269.2396    1573625.5217
#Sta/Elev= 21
       0      72  149.71      72  175.69   72.12  287.93      72  317.36    69.9
  434.41    69.9  455.37   68.43   495.7   68.42  516.72    69.9  526.57    69.9
  547.57    71.4  571.97    71.4  573.18      71  746.15   70.57  827.44    70.5
 1134.69    70.5 1164.56   70.83  1209.7      71 1375.52      71 1378.08   70.81
 1382.44   70.89
#Mann= 3 ,0,0
       0    .035       0  434.41    .018       0  516.72    .035       0
Levee=-1,280.79,72.01,-1,547.59,71.4004,	341,	340
Bank Sta=434.41,516.72
XS Rating Curve= 0 ,0
Exp/Cntr=0.3,0.1

Type RM Length L Ch R = 1 ,7138.036,148.73,108.24,67.75
XS GIS Cut Line= 6
    1078440.6899    1572253.2839    1078410.0467     1572572.214
    1078402.5898    1572626.6647     1078303.739    1572699.4352
    1078288.2896    1572714.9299    1078224.1545    1573621.0767
#Sta/Elev= 20
       0      72  290.56      72  320.33   69.87  416.11   69.82  437.11   68.32
  477.11   68.32   497.2   69.76  498.11   69.76   581.1   69.74  602.14   71.24
  626.59   71.23  627.94   70.78  704.89    70.5 1215.23    70.5  1228.5   70.65
 1241.25   70.65 1295.63      71 1422.31      71 1425.83    70.5  1428.4   70.01
#Mann= 3 ,0,0
       0    .035       0  416.11    .018       0  498.11    .035       0
Levee=-1,289.16,72,-1,602.22,71.23524,	341,	340
Bank Sta=416.11,498.11
XS Rating Curve= 0 ,0
Exp/Cntr=0.3,0.1

Type RM Length L Ch R = 1 ,7029.794,125.27,88.63,51.99
XS GIS Cut Line= 4
    1078259.0796    1572239.3139    1078248.9277    1572576.7524
    1078259.1448    1572775.2182    1078191.1344    1573617.9017
#Sta/Elev= 24
       0   71.59   29.72   71.63  103.45    71.5  153.63    71.5  240.65      72
   295.2      72  327.46    69.7  338.32    69.7  359.36   68.22   399.3   68.22
  420.26    69.7   536.9   69.71  557.97    71.2  582.45    71.2  583.94   70.71
  637.02    70.5 1196.78    70.5 1270.95      71 1357.37      71 1362.04    70.5
 1365.39      70 1372.89    68.5 1375.74      68 1381.74      68
#Mann= 3 ,0,0
       0    .035       0  338.32    .018       0  420.26    .035       0
Levee=-1,293.39,72,-1,558.01,71.20392,	341,	340
Bank Sta=338.32,420.26
XS Rating Curve= 0 ,0
Exp/Cntr=0.3,0.1

Type RM Length L Ch R = 1 ,6941.164,78.58,113.31,148.04
XS GIS Cut Line= 6
    1078140.9693    1572227.8839    1078125.4875    1572526.2204
    1078118.7443    1572619.6797    1078212.2914    1572687.2832
    1078230.5045    1572701.5948    1078163.1944    1573616.6317
#Sta/Elev= 29
       0   71.18   43.56   71.07  140.93    71.5  219.06    71.5  287.77      72
  310.04      72  344.53   69.56  425.86   69.58  426.73   69.58  446.86   68.14
  486.86   68.14  507.86   69.64  605.87   69.66  626.97   71.16  651.49   71.16
  653.15   70.61  686.37    70.5 1281.23    70.5 1318.69   70.61 1325.47   70.69
 1340.26    70.5 1348.24    70.5 1355.67   70.63 1365.51   70.61 1412.81      71
 1426.23      71 1433.13      70 1442.11    68.5 1448.53    68.5
#Mann= 3 ,0,0
       0    .035       0  425.86    .018       0  507.86    .035       0
Levee=-1,308.88,72,-1,626.99,71.16149,	341,	340
Bank Sta=425.86,507.86
XS Rating Curve= 0 ,0
Exp/Cntr=0.3,0.1

Type RM Length L Ch R = 1 ,6827.856,73.22,109.5,145.78
XS GIS Cut Line= 5
    1078089.5342    1572224.0739    1078072.2662    1572530.7353
    1078091.3989    1572692.3778    1078104.8158    1572829.0109
    1078096.5192    1573614.0916
#Sta/Elev= 30
       0      71   54.07      71  166.58    71.5  245.34    71.5  317.79   71.99
   352.5   69.51  469.92   69.51  490.89   68.03   530.9   68.03  551.91   69.51
  561.72   69.51  582.72   71.01  607.12   71.01  608.66    70.5  824.03   70.29
  838.62    70.5  903.45    70.5  911.13   70.42   973.2    70.5  988.04   70.16
 1023.09   70.42 1096.64   70.32 1177.09   70.38 1216.09    70.5 1341.61    70.5
 1366.45   70.69 1373.55   70.64 1377.74    70.5 1391.08    70.5 1392.33   70.34
#Mann= 3 ,0,0
       0    .035       0  469.92    .018       0  551.91    .035       0
Levee=-1,317.69,71.99,-1,582.81,71.0098,	341,	340
Bank Sta=469.92,551.91
XS Rating Curve= 0 ,0
Exp/Cntr=0.3,0.1

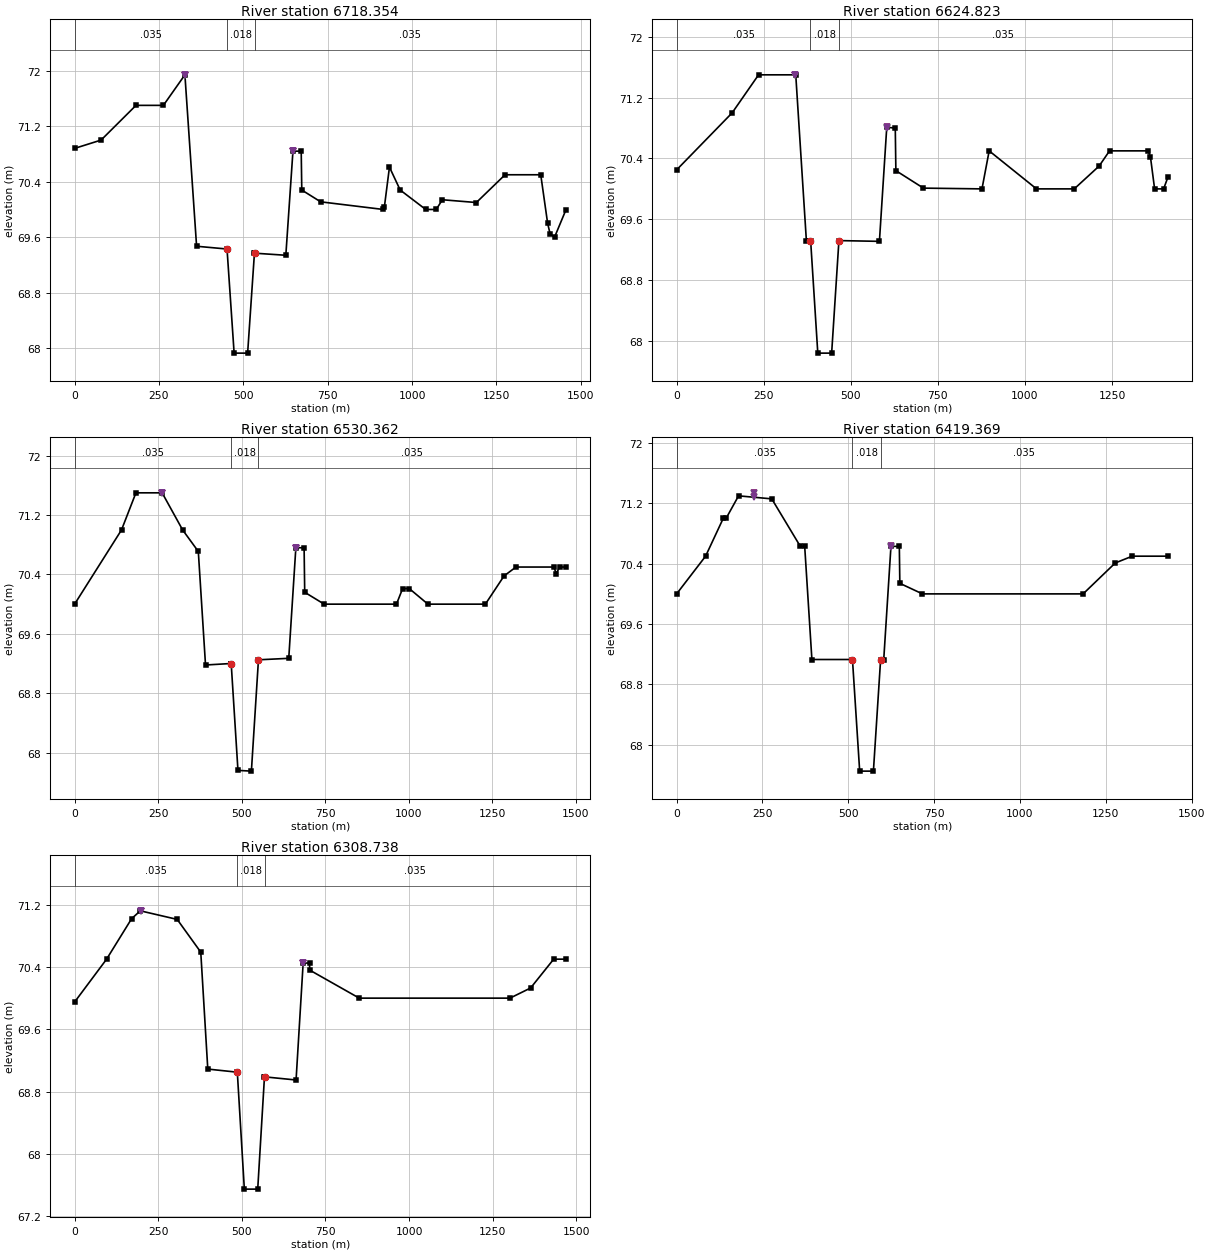
Type RM Length L Ch R = 1 ,6718.354,130.83,93.53,56.23
XS GIS Cut Line= 6
    1078023.5364    1572218.3589    1078045.1515    1572579.2561
    1078058.2498    1572629.2047    1077972.8051    1572714.3585
    1077960.4596    1572730.8049    1078039.1998    1573628.6967
#Sta/Elev= 30
       0   70.88   78.52      71  181.95    71.5  263.13    71.5   326.9   71.94
  361.54   69.47  451.75   69.43  472.77   67.93   512.8   67.93  532.96   69.37
  533.81   69.37     626   69.34  647.09   70.84  671.59   70.84  673.27   70.28
  729.28   70.11  914.95      70  918.16   70.04  933.12   70.61  964.93   70.28
 1040.61      70 1071.76      70 1089.87   70.14 1190.63    70.1 1275.72    70.5
  1381.5    70.5  1401.9    69.8 1409.14   69.65 1422.37    69.6 1455.71   69.99
#Mann= 3 ,0,0
       0    .035       0  451.75    .018       0  533.81    .035       0
Levee=-1,326.75,71.94,-1,647.12,70.84081,	341,	340
Bank Sta=451.75,533.81
XS Rating Curve= 0 ,0
Exp/Cntr=0.3,0.1

Type RM Length L Ch R = 1 ,6624.823,131.59,94.46,57.33
XS GIS Cut Line= 6
    1077850.8161    1572232.1172    1077906.1448    1572554.4187
    1077914.0826    1572610.7491     1077924.109    1572692.1077
    1077943.7248     1572852.662     1077993.903    1573633.3534
#Sta/Elev= 26
       0   70.25  159.41      71  235.22    71.5  341.95    71.5  372.44   69.32
   383.9   69.32  384.65   69.32  405.23   67.84  444.99   67.84  465.88   69.32
  582.12   69.31  603.17   70.81  627.63    70.8  629.35   70.24  708.45   70.01
  876.52      70  897.14    70.5 1032.99      70 1141.36      70 1212.72    70.3
 1242.65    70.5 1353.36    70.5 1360.11   70.42 1372.04      70 1397.87      70
 1409.93   70.15
#Mann= 3 ,0,0
       0    .035       0   383.9    .018       0  465.88    .035       0
Levee=-1,341,71.5,-1,603.18,70.80541,	341,	340
Bank Sta=383.9,465.88
XS Rating Curve= 0 ,0
Exp/Cntr=0.3,0.1

Type RM Length L Ch R = 1 ,6530.362,79.99,110.99,142
XS GIS Cut Line= 6
    1077700.1091    1572245.6639    1077774.2871    1572583.9064
    1077790.7026    1572674.0781    1077886.8148    1572731.9604
    1077901.6162    1572740.9649    1077953.2629      1573641.82
#Sta/Elev= 28
       0      70  140.37      71  183.49    71.5  261.92    71.5  323.27      71
  370.17   70.71  391.74   69.18  467.69    69.2  468.57    69.2  488.81   67.76
  529.02   67.75  550.13   69.25  640.79   69.27  662.05   70.76  686.75   70.76
  688.56   70.16  746.78      70  963.13      70  981.56   70.21 1001.39   70.21
 1057.27      70 1229.18      70 1285.03   70.38 1320.63    70.5 1434.49    70.5
 1441.04   70.41  1451.4    70.5 1469.79    70.5
#Mann= 3 ,0,0
       0    .035       0  467.69    .018       0  550.13    .035       0
Levee=-1,262.31,71.5,-1,662.07,70.76232,	341,	340
Bank Sta=467.69,550.13
XS Rating Curve= 0 ,0
Exp/Cntr=0.3,0.1

Type RM Length L Ch R = 1 ,6419.369,75.69,110.63,145.57
XS GIS Cut Line= 4
     1077636.609    1572260.0573    1077740.8731    1572639.9945
    1077809.3023    1572885.2722    1077905.0028    1573661.2934
#Sta/Elev= 22
       0      70   84.39    70.5  135.63      71  143.89      71  180.44    71.3
  277.11   71.26  360.29   70.63     373   70.63  393.98   69.13  512.11   69.13
  533.12   67.65  573.12   67.65  594.11   69.13   603.2   69.13   624.2   70.63
   648.6   70.63  650.08   70.14  715.95      70 1183.83      70 1277.46   70.41
 1326.95    70.5 1430.53    70.5
#Mann= 3 ,0,0
       0    .035       0  512.11    .018       0  594.11    .035       0
Levee=-1,224.45,71.34,-1,624.23,70.62785,	341,	340
Bank Sta=512.11,594.11
XS Rating Curve= 0 ,0
Exp/Cntr=0.3,0.1

Type RM Length L Ch R = 1 ,6308.738,137.26,95.23,53.18
XS GIS Cut Line= 6
    1077584.9622     1572271.064    1077696.0224    1572605.9842
    1077725.5092    1572696.9381    1077659.7331    1572797.3003
    1077647.6157    1572818.8584    1077849.1227    1573670.6068
#Sta/Elev= 21
       0   69.95   95.65    70.5  170.57   71.02  196.52   71.12  306.69   71.01
  377.18   70.59  398.18   69.09  486.46   69.05  507.46   67.55  547.46   67.55
  567.62   68.99  568.46   68.99   662.1   68.95  683.28   70.45  702.52   70.45
  702.74   70.36     851      70 1301.57      70 1363.22   70.13  1432.3    70.5
 1468.46    70.5
#Mann= 3 ,0,0
       0    .035       0  486.46    .018       0  568.46    .035       0
Levee=-1,197.41,71.12,-1,683.35,70.45068,	341,	340
Bank Sta=486.46,568.46
XS Rating Curve= 0 ,0
Exp/Cntr=0.3,0.1