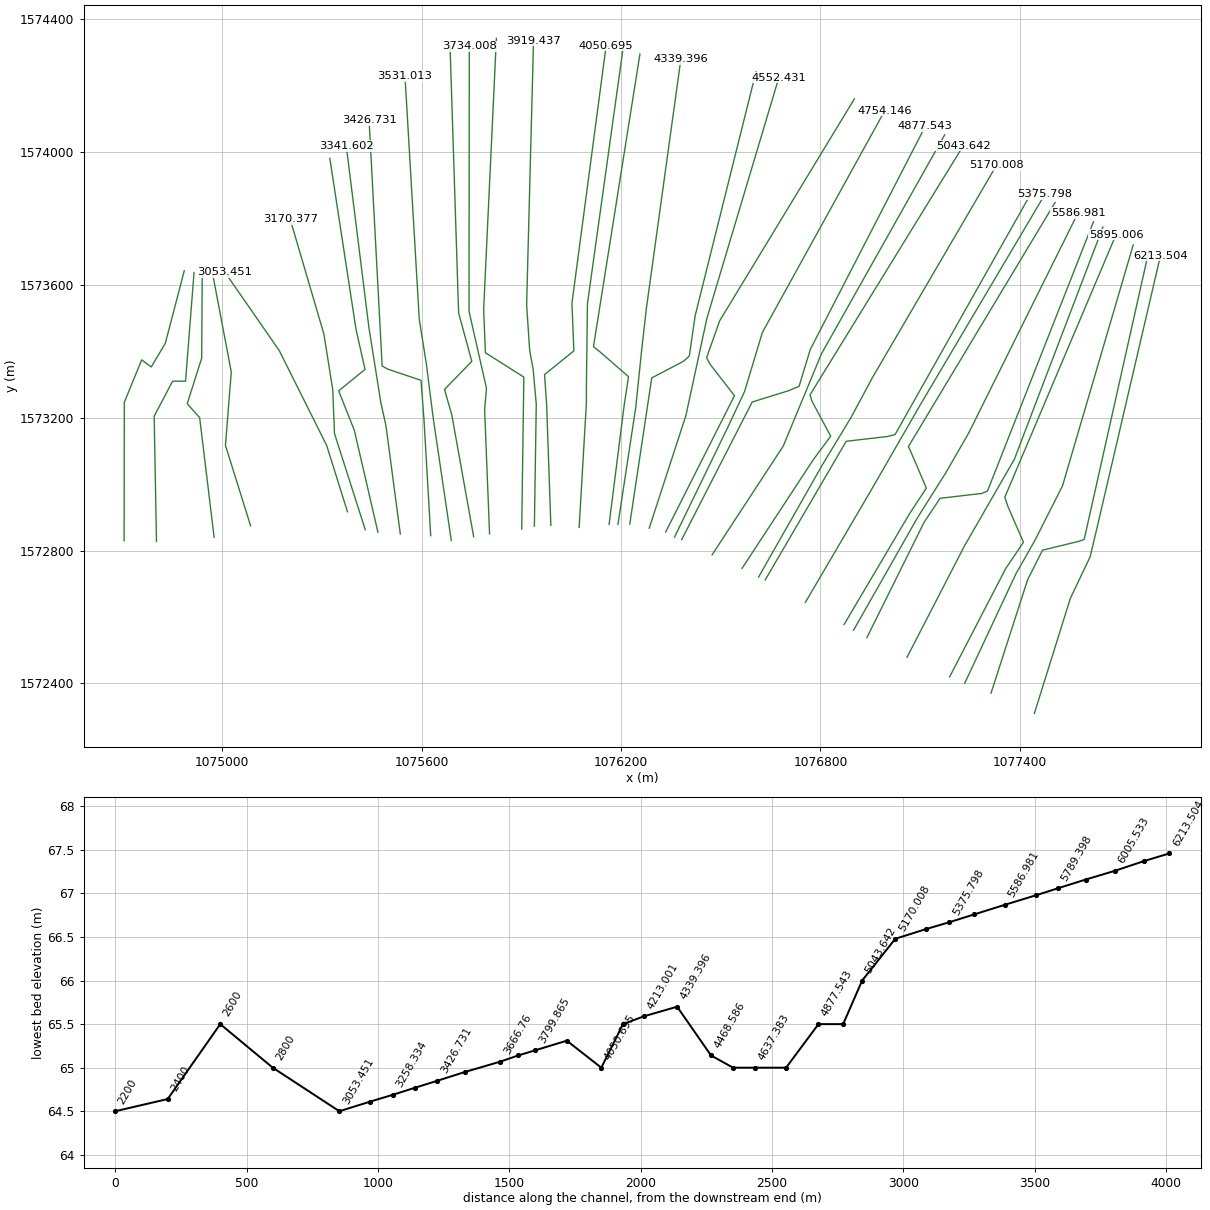
HEC-RAS study HECRAS_v1.prj: HECRAS_v1

--- HECRAS_v1.g02 (geometry) --- (continued)

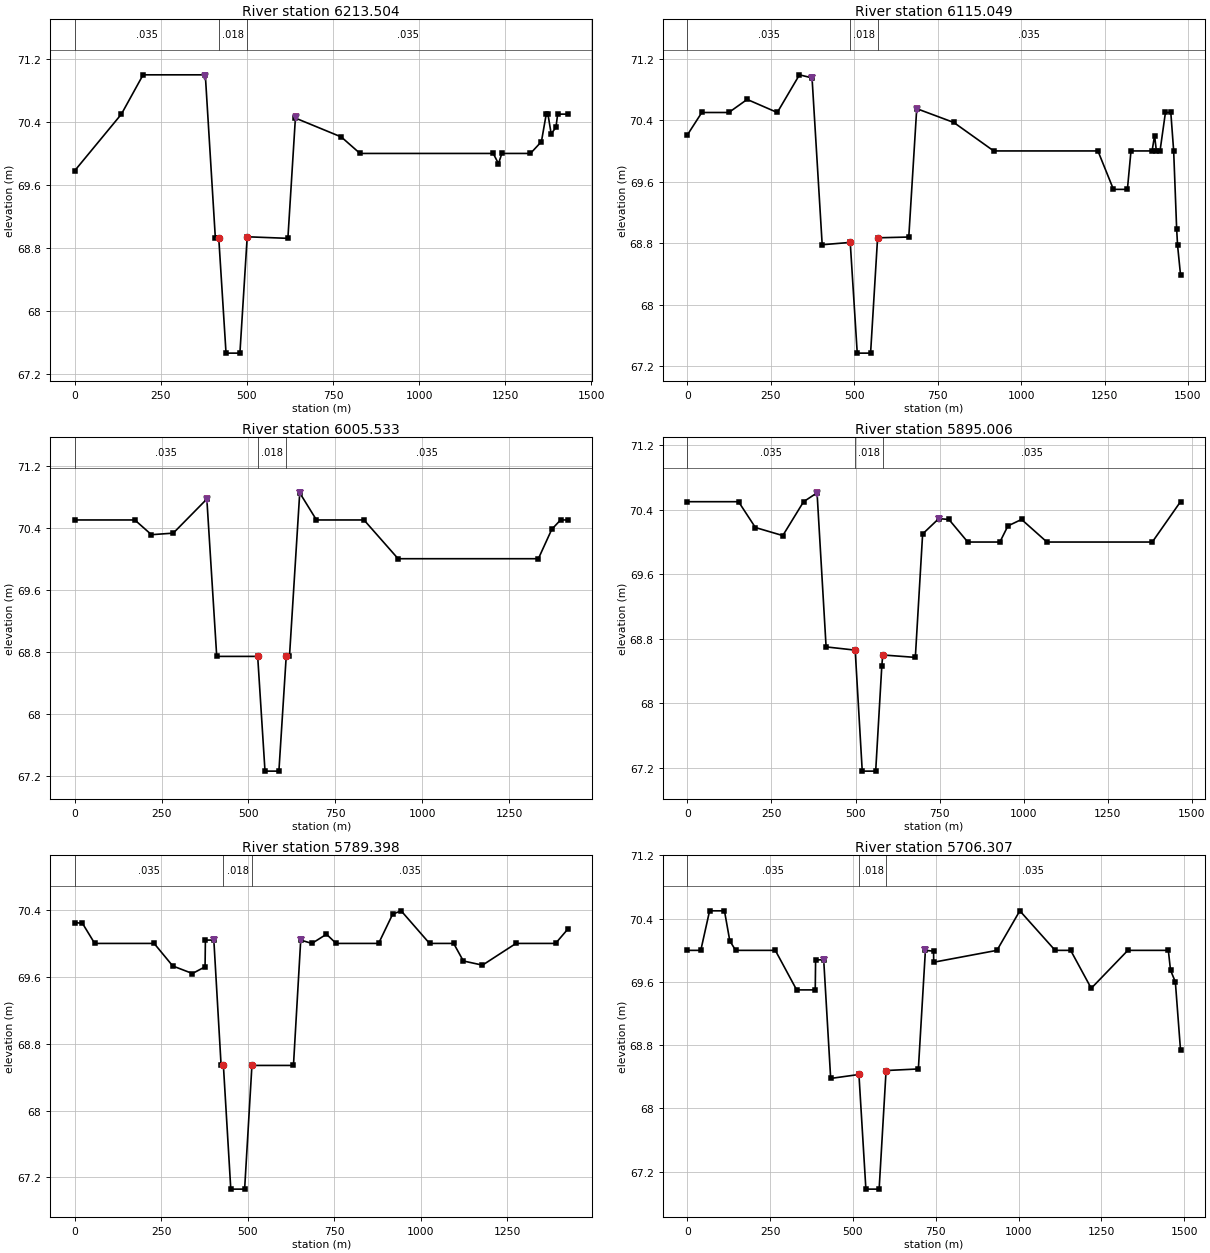
Type RM Length L Ch R = 1 ,6213.504,134.85,98.46,62.09
XS GIS Cut Line= 5
    1077443.5686    1572310.0107    1077551.8597    1572656.1842
     1077611.188    1572780.7703    1077628.1423    1572851.8785
     1077822.876    1573686.6935
#Sta/Elev= 24
       0   69.78  135.54    70.5  198.52      71   379.1      71  408.15   68.93
  418.07   68.93  439.24   67.46  479.53   67.46  500.71   68.94  618.79   68.92
  640.57   70.45  773.66   70.21  828.17      70 1214.78      70 1230.02   69.87
 1239.88      70 1322.84      70 1354.66   70.15 1368.61    70.5 1373.65    70.5
  1382.9   70.25  1396.7   70.33 1401.82    70.5 1431.04    70.5
#Mann= 3 ,0,0
       0    .035       0  418.07    .018       0  500.71    .035       0
Levee=-1,379.49,70.99,-1,640.9,70.46,	341,	340
Bank Sta=418.07,500.71
XS Rating Curve= 0 ,0
Exp/Cntr=0.3,0.1

Type RM Length L Ch R = 1 ,6115.049,74.08,109.52,144.96
XS GIS Cut Line= 6
    1077313.1817    1572370.9708    1077423.2416    1572712.0683
     1077468.122    1572801.0784    1077576.7283    1572827.4692
    1077593.4289    1572833.2518    1077788.1626    1573701.9335
#Sta/Elev= 30
       0   70.21   42.98    70.5  123.98    70.5  178.91   70.67  269.18    70.5
  335.65   70.99  373.42   70.95   403.8   68.78  487.87   68.81  508.87   67.37
  548.87   67.37  569.87   68.87  663.35   68.88  687.16   70.55  798.33   70.37
  917.92      70 1230.29      70 1276.75    69.5 1318.59    69.5 1329.36      70
 1392.59      70 1400.07    70.2 1405.43      70 1416.39      70 1432.61    70.5
 1448.72    70.5 1457.27      70 1466.29   68.98 1469.02   68.77 1477.78   68.39
#Mann= 3 ,0,0
       0    .035       0  487.87    .018       0  569.87    .035       0
Levee=-1,373.18,70.95,-1,686.87,70.55,	341,	340
Bank Sta=487.87,569.87
XS Rating Curve= 0 ,0
Exp/Cntr=0.3,0.1

Type RM Length L Ch R = 1 ,6005.533,74.56,110.53,146.5
XS GIS Cut Line= 5
    1077233.9476    1572400.4631    1077387.8418    1572729.4454
    1077445.6147    1572831.2056    1077528.2412    1572994.6647
    1077740.8903    1573719.1491
#Sta/Elev= 19
       0    70.5  172.95    70.5  220.77   70.31  283.52   70.33  380.17   70.77
  408.61   68.74  526.43   68.74  547.49   67.26  587.46   67.26   608.5   68.74
   617.9   68.74  647.39   70.85  695.53    70.5  832.23    70.5   930.4      70
 1333.93      70 1372.57   70.38 1397.81    70.5 1418.42    70.5
#Mann= 3 ,0,0
       0    .035       0  526.43    .018       0   608.5    .035       0
Levee=-1,380.39,70.77,-1,648.11,70.85,	341,	340
Bank Sta=526.43,608.5
XS Rating Curve= 0 ,0
Exp/Cntr=0.3,0.1

Type RM Length L Ch R = 1 ,5895.006,143.8,105.61,67.44
XS GIS Cut Line= 6
    1077188.4392    1572419.5131     1077357.076    1572745.2403
    1077410.6896    1572824.8556    1077363.6318    1572933.3258
    1077354.5979    1572960.3226    1077689.0319    1573749.8408
#Sta/Elev= 23
       0    70.5  151.99    70.5  202.07   70.18  283.61   70.08   345.5    70.5
  385.59   70.61  412.47    68.7  499.01   68.66  520.01   67.16  560.01   67.16
  578.16   68.46  581.01    68.6  677.97   68.57  699.67    70.1  747.63   70.29
  777.85   70.28  833.95      70  929.52      70  953.49    70.2  994.02   70.28
 1069.52      70 1382.95      70 1466.91    70.5
#Mann= 3 ,0,0
       0    .035       0  499.01    .018       0  581.01    .035       0
Levee=-1,384.9,70.6,-1,749.07,70.29,	341,	340
Bank Sta=499.01,581.01
XS Rating Curve= 0 ,0
Exp/Cntr=0.3,0.1

Type RM Length L Ch R = 1 ,5789.398,121.37,83.09,44.79
XS GIS Cut Line= 4
    1077060.3806    1572478.7799    1077233.6889    1572814.6025
    1077383.3932    1573074.5806    1077649.8734    1573773.1242
#Sta/Elev= 29
       0   70.25   22.52   70.24   57.81      70  229.63      70  283.56   69.73
  340.42   69.64  376.94   69.72  377.91   70.04  402.31   70.04  423.31   68.54
  429.95   68.54  451.32   67.06  491.32   67.06  512.44   68.54  632.51   68.54
  653.51   70.04  685.79      70  728.05   70.11  755.84      70  878.72      70
  919.34   70.35  943.87   70.39 1026.02      70 1095.71      70 1123.69   69.79
 1179.03   69.74 1275.93      70  1390.3      70 1425.55   70.17
#Mann= 3 ,0,0
       0    .035       0  429.95    .018       0  512.44    .035       0
Levee=-1,402.31,70.04148,-1,653.5,70.04148,	341,	340
Bank Sta=429.95,512.44
XS Rating Curve= 0 ,0
Exp/Cntr=0.3,0.1

Type RM Length L Ch R = 1 ,5706.307,81.06,119.33,157.59
XS GIS Cut Line= 6
    1076939.7304    1572538.0467    1077111.7443    1572884.8224
    1077159.8641    1572957.1476    1077285.0474    1572971.6098
    1077302.7394    1572979.3726    1077621.2984    1573788.9992
#Sta/Elev= 30
       0      70   40.27      70   66.86    70.5  111.76    70.5  127.91   70.12
  145.57      70   265.4      70  329.82    69.5  385.96    69.5  387.09   69.88
  411.55   69.88  432.59   68.38  517.98   68.43  538.98   66.98  578.98   66.98
  599.98   68.48  697.51    68.5  718.74      70   743.4   69.99  743.84   69.85
  934.84      70 1003.96    70.5 1110.66      70 1157.53      70 1219.69   69.52
 1330.28      70  1452.6      70 1459.15   69.75 1473.79    69.6 1489.35   68.74
#Mann= 3 ,0,0
       0    .035       0  517.98    .018       0  599.98    .035       0
Levee=-1,411.55,69.87965,-1,718.74,69.99842,	341,	340
Bank Sta=517.98,599.98
XS Rating Curve= 0 ,0
Exp/Cntr=0.3,0.1

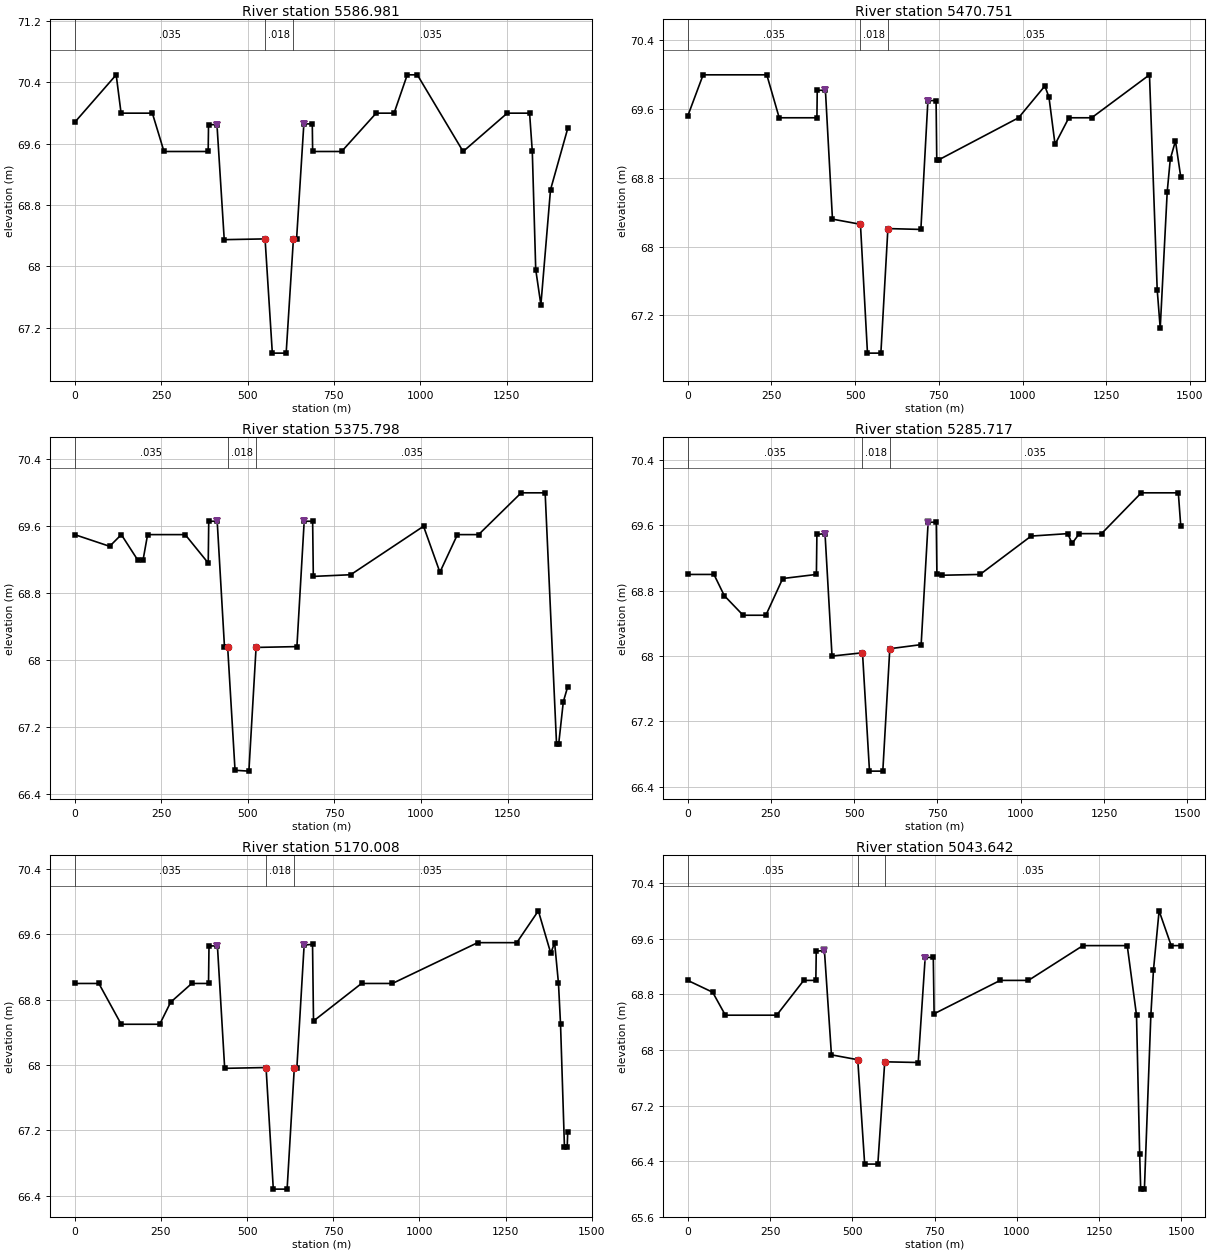
Type RM Length L Ch R = 1 ,5586.981,78.24,116.23,154.22
XS GIS Cut Line= 5
    1076899.5136    1572560.2718    1077090.7895    1572896.8889
    1077177.9757    1573035.2595     1077246.132    1573153.6204
    1077574.7316    1573815.4576
#Sta/Elev= 30
       0   69.88  120.01    70.5  134.18      70  224.66      70  258.32    69.5
  386.12    69.5  387.17   69.85  411.59   69.85   432.6   68.35  550.71   68.36
  571.73   66.87  611.73   66.87  632.72   68.36   641.9   68.36   662.9   69.86
   687.3   69.86  688.37    69.5  772.12    69.5   872.1      70  923.89      70
  962.03    70.5  991.19    70.5 1123.64    69.5 1251.27      70 1315.92      70
 1323.77    69.5 1333.68   67.96  1348.6    67.5 1376.42      69 1426.22    69.8
#Mann= 3 ,0,0
       0    .035       0  550.71    .018       0  632.72    .035       0
Levee=-1,411.59,69.85081,-1,662.9,69.85725,	341,	340
Bank Sta=550.71,632.72
XS Rating Curve= 0 ,0
Exp/Cntr=0.3,0.1

Type RM Length L Ch R = 1 ,5470.751,132.94,94.95,56.97
XS GIS Cut Line= 6
    1076870.9386    1572577.2051     1077067.716    1572910.1754
    1077118.5891    1572987.8393     1077072.109    1573096.5388
    1077064.6139    1573112.7229    1077505.9398    1573847.2077
#Sta/Elev= 30
       0   69.52   45.93      70  236.11      70   273.2    69.5  385.81    69.5
  386.77   69.82  411.21   69.82  432.24   68.32  515.83   68.26  536.83   66.76
  576.83   66.76  597.83   68.21   696.3    68.2  717.31    69.7  741.71    69.7
  743.77   69.01  749.47   69.01  988.08    69.5  1066.6   69.87 1078.89   69.74
 1097.03   69.19 1138.25    69.5 1206.37    69.5 1379.11      70 1402.13    67.5
 1411.17   67.05 1432.07   68.64  1441.3   69.02 1456.65   69.23 1472.54   68.81
#Mann= 3 ,0,0
       0    .035       0  515.83    .018       0  597.83    .035       0
Levee=-1,411.21,69.82031,-1,717.31,69.70021,	341,	340
Bank Sta=515.83,597.83
XS Rating Curve= 0 ,0
Exp/Cntr=0.3,0.1

Type RM Length L Ch R = 1 ,5375.798,128.33,90.08,51.83
XS GIS Cut Line= 4
    1076754.5217    1572643.8803    1076950.2991    1572977.7881
    1077100.0034    1573237.7662    1077475.2481    1573871.5494
#Sta/Elev= 30
       0    69.5  100.91   69.36  134.67    69.5  181.38    69.2  197.57    69.2
   210.5    69.5  319.08    69.5  385.58   69.16  387.07   69.66  411.47   69.66
  432.47   68.16  441.62   68.16  462.99   66.68     503   66.67  523.77   68.15
  641.67   68.16  662.67   69.66  687.07   69.66  689.05      69  796.94   69.02
 1007.31    69.6 1054.55   69.05 1105.13    69.5 1166.26    69.5 1289.24      70
 1358.44      70 1391.28      67  1397.7      67 1410.88    67.5 1423.61   67.68
#Mann= 3 ,0,0
       0    .035       0  441.62    .018       0  523.77    .035       0
Levee=-1,411.47,69.66111,-1,662.67,69.66111,	341,	340
Bank Sta=441.62,523.77
XS Rating Curve= 0 ,0
Exp/Cntr=0.3,0.1

Type RM Length L Ch R = 1 ,5285.717,76.24,115.71,155.18
XS GIS Cut Line= 6
    1076633.8714    1572711.6137    1076829.4693    1573046.4807
    1076877.2886    1573128.5979    1077000.4639    1573142.8945
    1077024.3972    1573148.7063    1077441.3814    1573888.4828
#Sta/Elev= 28
       0      69   78.73      69  109.78   68.74  166.28    68.5  234.63    68.5
  285.26   68.95  386.39      69  387.88   69.49  412.29    69.5  433.31      68
  524.84   68.04  545.84   66.59  585.84   66.59  606.84   68.09  700.97   68.14
  721.98   69.64  746.38   69.64   748.3      69  762.22   68.99  877.91      69
 1031.25   69.47 1141.26    69.5 1154.27   69.38 1175.95    69.5 1242.76    69.5
 1362.07      70 1473.37      70 1480.67   69.59
#Mann= 3 ,0,0
       0    .035       0  524.84    .018       0  606.84    .035       0
Levee=-1,412.22,69.49541,-1,721.98,69.6356,	341,	340
Bank Sta=524.84,606.84
XS Rating Curve= 0 ,0
Exp/Cntr=0.3,0.1

Type RM Length L Ch R = 1 ,5170.008,86.03,126.37,166.7
XS GIS Cut Line= 5
     1076613.763    1572720.0804    1076806.3819    1573058.7514
    1076892.0198    1573200.3694    1076955.7618    1573319.1616
    1077329.1978    1573958.3329
#Sta/Elev= 30
       0      69   70.07      69  134.95    68.5  246.67    68.5  278.32   68.77
  339.58      69  388.22      69   389.6   69.46  414.06   69.46   435.1   67.96
  555.11   67.97  576.15   66.48  616.17   66.48  637.12   67.97  644.56   67.97
  665.56   69.47  689.96   69.48  692.77   68.54  832.05      69  921.62      69
 1168.96    69.5 1282.43    69.5    1345   69.89 1381.04   69.37 1392.19    69.5
  1403.4      69 1409.36    68.5 1420.71      67 1428.75      67 1430.19   67.18
#Mann= 3 ,0,0
       0    .035       0  555.11    .018       0  637.12    .035       0
Levee=-1,414.06,69.46284,-1,665.53,69.47281,	341,	340
Bank Sta=555.11,637.12
XS Rating Curve= 0 ,0
Exp/Cntr=0.3,0.1

Type RM Length L Ch R = 1 ,5043.642,108.46,72.2,35.89
XS GIS Cut Line= 6
     1076564.143    1572746.4171    1076778.2474    1573072.9603
    1076830.8435    1573143.9279     1076774.338    1573249.5473
    1076768.6134    1573268.3881    1077229.6243    1574017.6896
#Sta/Elev= 30
       0      69   75.71   68.83  114.33    68.5  270.22    68.5  352.44      69
  389.21      69  390.48   69.42  415.29   69.43  436.62   67.93  516.59   67.86
  537.59   66.36  577.59   66.36  598.59   67.83  700.27   67.82  721.48   69.33
  746.11   69.33  748.58   68.52  949.27      69 1035.06      69 1200.76    69.5
  1335.4    69.5 1363.58    68.5 1373.19    66.5 1376.29      66 1387.57      66
 1407.17    68.5 1415.13   69.15 1432.21      70 1468.98    69.5 1498.05    69.5
#Mann= 3 ,0,0
       0    .035       0  516.59    .018       0  598.59    .035       0
Levee=-1,415.26,69.4268,-1,721.41,69.32333,	341,	340
Bank Sta=516.59,598.59
XS Rating Curve= 0 ,0
Exp/Cntr=0.3,0.1

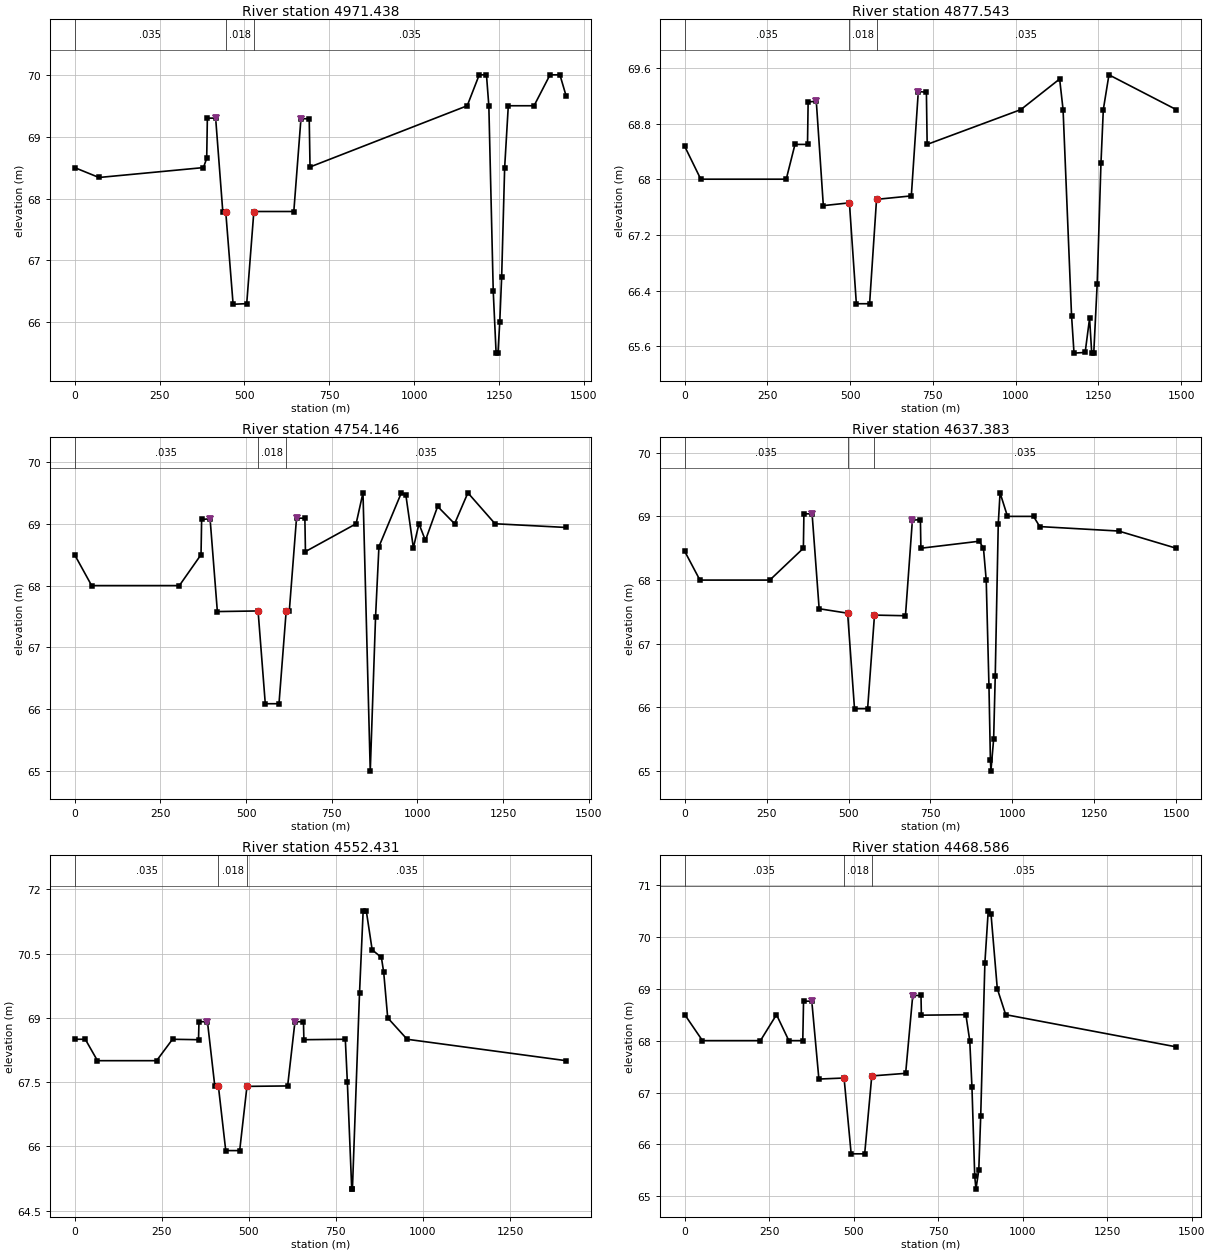
Type RM Length L Ch R = 1 ,4971.438,129.85,93.89,58
XS GIS Cut Line= 4
    1076473.9728    1572787.0572     1076687.982     1573114.152
    1076802.7586    1573391.3524    1077173.7442    1574050.7097
#Sta/Elev= 30
       0    68.5   71.73   68.34  379.43    68.5     389   68.65  390.96    69.3
  415.36    69.3  436.36   67.79  445.03   67.79  466.78   66.29  506.85    66.3
  527.88   67.79  645.56   67.79  666.56   69.29  690.96   69.29  693.32   68.51
  1156.3    69.5 1191.62      70 1212.95      70 1219.94    69.5 1232.91    66.5
 1241.35    65.5 1246.81    65.5 1252.08      66 1257.68   66.73 1266.53    68.5
 1277.26    69.5 1353.11    69.5 1400.12      70 1429.29      70 1447.47   69.66
#Mann= 3 ,0,0
       0    .035       0  445.03    .018       0  527.88    .035       0
Levee=-1,415.32,69.29515,-1,666.51,69.28973,	341,	340
Bank Sta=445.03,527.88
XS Rating Curve= 0 ,0
Exp/Cntr=0.3,0.1

Type RM Length L Ch R = 1 ,4877.543,83.32,123.4,163.47
XS GIS Cut Line= 6
    1076382.5326    1572832.7773     1076594.623    1573246.7981
       1076703.8    1573280.6628    1076735.5933    1573293.7882
    1076769.4509    1573405.0022    1077115.3241    1574076.1098
#Sta/Elev= 30
       0   68.47   48.38      68  306.61      68  333.04    68.5  370.91    68.5
  372.77   69.11  397.46   69.12   418.7   67.62   497.5   67.66   518.5   66.21
   558.5   66.21   579.5   67.71  684.61   67.76  705.68   69.26  730.17   69.25
  732.43    68.5 1015.48      69 1132.79   69.44 1143.16      69 1168.77   66.04
 1176.23    65.5 1209.88   65.51 1223.25      66 1229.74    65.5 1235.88    65.5
 1246.28    66.5 1257.66   68.23 1264.76      69 1281.78    69.5 1485.14      69
#Mann= 3 ,0,0
       0    .035       0   497.5    .018       0   579.5    .035       0
Levee=-1,397.43,69.1175,-1,705.67,69.25621,	341,	340
Bank Sta=497.5,579.5
XS Rating Curve= 0 ,0
Exp/Cntr=0.3,0.1

Type RM Length L Ch R = 1 ,4754.146,77.69,116.76,155.84
XS GIS Cut Line= 5
    1076360.9426    1572840.3973    1076522.6273    1573173.6284
     1076571.763    1573278.5482     1076625.239    1573456.0351
    1076993.4038    1574123.0998
#Sta/Elev= 30
       0    68.5   49.67      68  305.51      68  368.72    68.5  370.46   69.07
  395.13   69.08  416.36   67.58  535.11   67.59  556.13   66.09   596.1   66.09
  617.11   67.59  626.21   67.59  647.21   69.09  671.61   69.09  673.27   68.55
  821.02      69  841.11    69.5  862.31      65  877.82    67.5  887.65   68.63
  953.05    69.5  966.27   69.46  988.07   68.61 1004.36      69  1023.2   68.73
 1058.81   69.28 1108.36      69  1147.1    69.5 1226.28      69 1433.53   68.94
#Mann= 3 ,0,0
       0    .035       0  535.11    .018       0  617.11    .035       0
Levee=-1,395.07,69.0767,-1,647.21,69.09055,	341,	340
Bank Sta=535.11,617.11
XS Rating Curve= 0 ,0
Exp/Cntr=0.3,0.1

Type RM Length L Ch R = 1 ,4637.383,120.75,84.95,49.15
XS GIS Cut Line= 6
    1076334.2725    1572855.6373    1076541.2829    1573265.8481
    1076467.9322    1573360.2821    1076457.4628    1573380.1484
    1076496.7003    1573491.0702    1076901.9637    1574158.6599
#Sta/Elev= 30
       0   68.45   46.23      68  259.58      68  362.04    68.5  363.67   69.04
  388.67   69.04  410.18   67.55  497.12   67.48  518.12   65.98  558.12   65.98
  579.12   67.45  673.65   67.44  694.77   68.94  719.31   68.95  720.72    68.5
  898.87   68.61  911.77    68.5  920.16      68  928.52   66.34  932.91   65.18
  934.48      65  942.79    65.5  947.72    66.5  956.91   68.88  962.43   69.37
  985.08      69 1064.59      69 1083.55   68.84 1324.44   68.77  1500.2    68.5
#Mann= 3 ,0,0
       0    .035       0  497.12    .018       0  579.12    .035       0
Levee=-1,388.6,69.0432,-1,694.69,68.93906,	341,	340
Bank Sta=497.12,579.12
XS Rating Curve= 0 ,0
Exp/Cntr=0.3,0.1

Type RM Length L Ch R = 1 ,4552.431,119.7,83.84,48
XS GIS Cut Line= 4
    1076284.7424    1572867.0673    1076395.3011    1573206.4879
    1076458.6237    1573499.6809    1076674.6332      1574222.16
#Sta/Elev= 30
       0    68.5   30.64    68.5   65.59      68  235.36      68  281.05    68.5
  355.73   68.49     357   68.91   381.4   68.91   402.4   67.41  412.68   67.41
  433.88    65.9  473.88    65.9   494.8    67.4  611.59   67.41  632.59   68.91
  656.99   68.91  658.24   68.49  777.15    68.5  783.01    67.5  795.58      65
  797.57      65  817.95   69.58   828.4    71.5  837.36    71.5  854.22   70.59
   880.8   70.41  887.44   70.06  898.88      69  954.63    68.5 1411.01      68
#Mann= 3 ,0,0
       0    .035       0  412.68    .018       0   494.8    .035       0
Levee=-1,381.33,68.90532,-1,632.53,68.90072,	341,	340
Bank Sta=412.68,494.8
XS Rating Curve= 0 ,0
Exp/Cntr=0.3,0.1

Type RM Length L Ch R = 1 ,4468.586,89.24,129.19,169.14
XS GIS Cut Line= 6
    1076226.3223    1572879.7674    1076292.3624    1573319.1882
    1076388.8975    1573369.8806    1076405.3927    1573385.2284
    1076423.1416    1573506.9892    1076606.0531    1574239.9401
#Sta/Elev= 30
       0    68.5   52.38      68  223.95      68  271.43    68.5  307.99      68
  349.22      68  351.49   68.76  375.89   68.76   396.9   67.26  471.41   67.28
  492.41   65.82  532.41   65.82  553.41   67.32  653.62   67.37  674.64   68.87
  699.07   68.87   700.2   68.49   831.9    68.5  843.31      68  849.85   67.11
  858.08   65.39  861.66   65.14  870.03    65.5  875.78   66.55  888.15    69.5
  898.03    70.5  906.37   70.43  924.85      69   949.7    68.5 1454.42   67.88
#Mann= 3 ,0,0
       0    .035       0  471.41    .018       0  553.41    .035       0
Levee=-1,375.89,68.75673,-1,674.56,68.86215,	341,	340
Bank Sta=471.41,553.41
XS Rating Curve= 0 ,0
Exp/Cntr=0.3,0.1

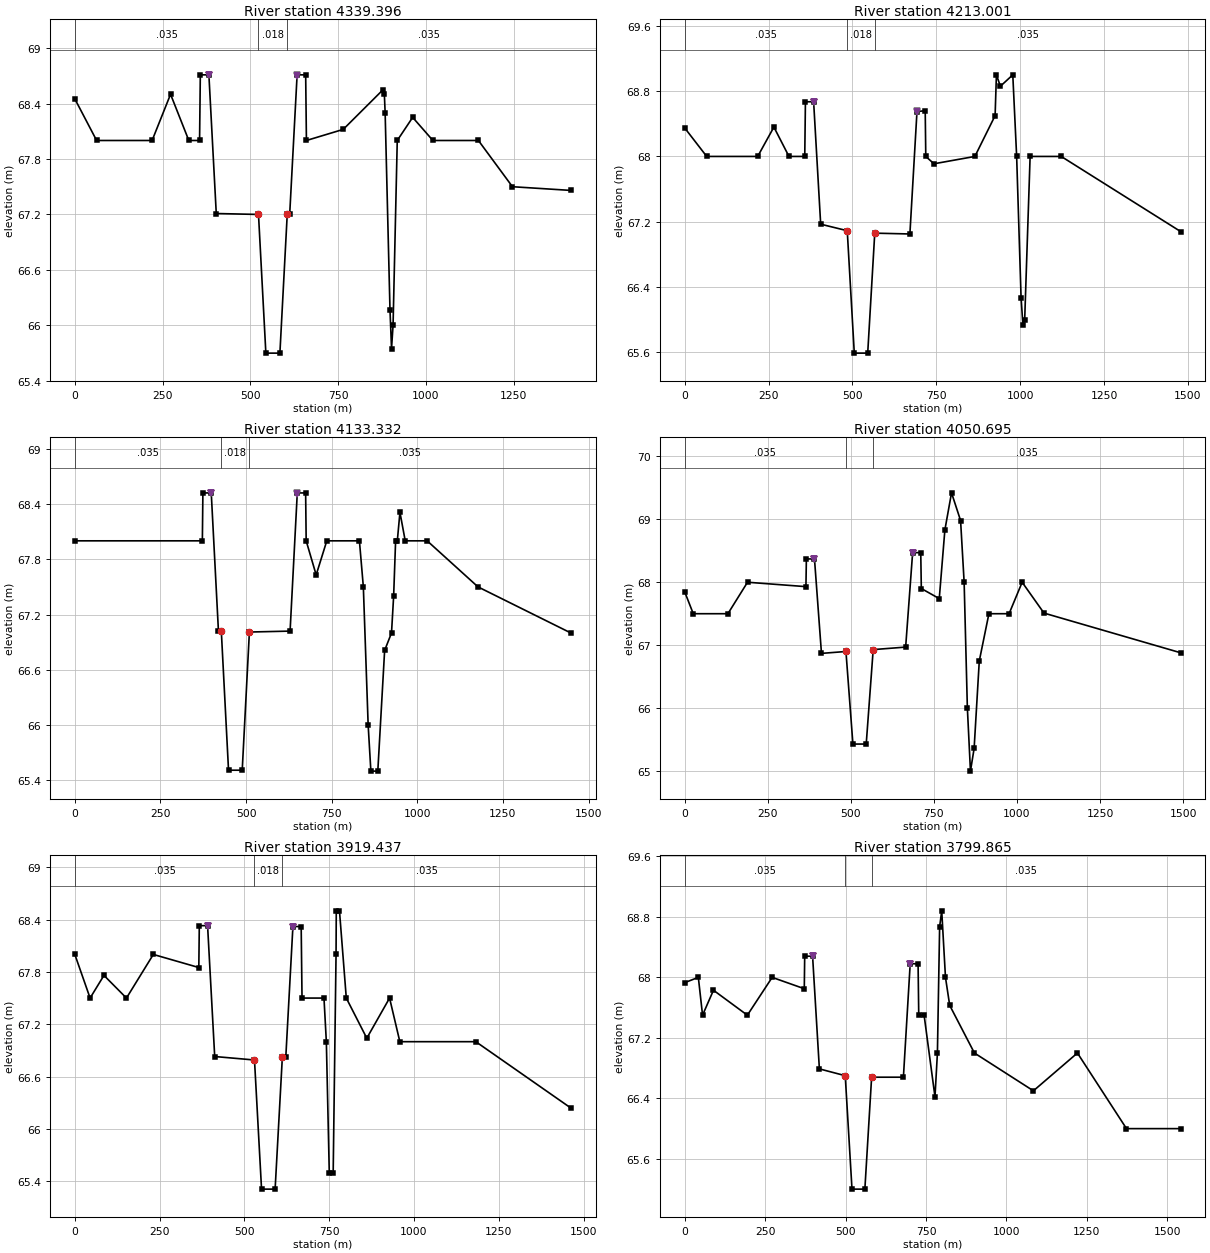
Type RM Length L Ch R = 1 ,4339.396,86.71,126.39,166.08
XS GIS Cut Line= 5
    1076190.7622    1572878.4974    1076244.4195    1573231.7166
    1076261.3718    1573396.5976    1076276.4864    1573530.0372
    1076379.9926    1574278.0402
#Sta/Elev= 30
       0   68.45   62.01      68  220.03      68  272.59    68.5   324.6      68
  355.22      68  357.35   68.71  381.76   68.71  402.76   67.21  523.02    67.2
  543.99    65.7  583.97    65.7  604.98   67.21  611.99   67.21  632.99   68.71
  657.38   68.71  659.51      68   764.3   68.12   877.9   68.55  881.45    68.5
  883.68    68.3  897.48   66.17  901.88   65.75  906.23      66   918.2      68
  962.09   68.25 1019.72      68  1149.3      68 1246.25    67.5 1412.45   67.46
#Mann= 3 ,0,0
       0    .035       0  523.02    .018       0  604.98    .035       0
Levee=-1,381.76,68.71024,-1,632.92,68.70232,	341,	340
Bank Sta=523.02,604.98
XS Rating Curve= 0 ,0
Exp/Cntr=0.3,0.1

Type RM Length L Ch R = 1 ,4213.001,115.26,79.67,44.08
XS GIS Cut Line= 6
    1076164.0922    1572878.4974    1076209.2256     1573235.565
    1076222.5123    1573322.9982    1076133.2626    1573400.5867
    1076117.1021    1573413.1684    1076256.8024    1574293.2802
#Sta/Elev= 30
       0   68.35   65.75      68   217.7      68     266   68.36  310.94      68
  357.98      68  359.98   68.67  384.41   68.67  405.44   67.17  484.61   67.09
  505.61   65.59  545.61   65.59  566.61   67.06  671.33   67.05  692.46   68.55
  717.02   68.56   718.7      68  743.11   67.91  865.02      68  925.31    68.5
  929.23      69  941.06   68.86     978      69  989.52      68 1002.71   66.27
 1008.28   65.93 1013.48      66 1029.66      68  1122.4      68 1478.22   67.08
#Mann= 3 ,0,0
       0    .035       0  484.61    .018       0  566.61    .035       0
Levee=-1,384.42,68.66766,-1,692.46,68.55412,	341,	340
Bank Sta=484.61,566.61
XS Rating Curve= 0 ,0
Exp/Cntr=0.3,0.1

Type RM Length L Ch R = 1 ,4133.332,118.69,82.64,46.58
XS GIS Cut Line= 5
     1076073.922    1572869.6073    1076095.7669    1573242.7902
    1076095.8113    1573296.6783    1076098.9794    1573542.8593
    1076206.0023    1574309.7902
#Sta/Elev= 30
       0      68  372.36      68  373.92   68.52  398.33   68.52  419.33   67.02
  427.71   67.02  448.79   65.51  488.77   65.51   509.7   67.01  628.54   67.02
  649.54   68.52  673.95   68.52   675.5      68   704.7   67.63  735.73      68
  830.98      68  842.46    67.5   856.5      66  864.43    65.5  884.68    65.5
   904.6   66.81   924.7      67  930.92    67.4  936.67      68  941.65      68
  949.31   68.31  964.73      68 1028.81      68 1177.27    67.5 1448.27      67
#Mann= 3 ,0,0
       0    .035       0  427.71    .018       0   509.7    .035       0
Levee=-1,398.26,68.52109,-1,649.51,68.51376,	341,	340
Bank Sta=427.71,509.7
XS Rating Curve= 0 ,0
Exp/Cntr=0.3,0.1

Type RM Length L Ch R = 1 ,4050.695,91.93,131.26,170.59
XS GIS Cut Line= 6
    1075988.8318    1572875.9574    1075976.0759    1573241.9826
    1075969.7818    1573329.3483    1076058.1338    1573400.5828
    1076052.2987    1573543.5784    1076155.2022    1574318.6802
#Sta/Elev= 30
       0   67.85   25.95    67.5  130.16    67.5  189.18      68  364.95   67.93
  366.28   68.37  390.69   68.37   411.7   66.87  485.33    66.9  506.33   65.43
  546.33   65.43  567.33   66.93  664.99   66.97     686   68.47  710.43   68.47
  712.14    67.9  766.12   67.74  783.01   68.83  803.04   69.42  830.27   68.98
  840.97      68  850.71      66  859.99      65  871.02   65.36  886.55   66.75
   915.5    67.5  976.22    67.5 1015.52      68 1081.23   67.51 1492.35   66.88
#Mann= 3 ,0,0
       0    .035       0  485.33    .018       0  567.33    .035       0
Levee=-1,390.63,68.36914,-1,686.03,68.46698,	341,	340
Bank Sta=485.33,567.33
XS Rating Curve= 0 ,0
Exp/Cntr=0.3,0.1

Type RM Length L Ch R = 1 ,3919.437,81.06,119.57,158.08
XS GIS Cut Line= 6
    1075939.3017    1572873.4173    1075944.9918     1573240.313
    1075935.4917    1573345.8583     1075925.201     1573401.759
    1075915.9794    1573539.0491    1075936.7617    1574333.9203
#Sta/Elev= 30
       0      68   44.98    67.5   85.85   67.76   152.2    67.5  231.42      68
  365.57   67.85  367.01   68.33  391.42   68.33  412.42   66.83  529.75   66.79
  550.55   65.31  590.57   65.31  611.84   66.82  622.02   66.82  643.02   68.32
  667.42   68.32  669.89    67.5  734.65    67.5  741.62      67  750.32   65.49
  761.78    65.5  770.24      68  770.91    68.5  780.32    68.5  800.45    67.5
  860.88   67.04  928.06    67.5  958.33      67 1182.36      67 1462.49   66.24
#Mann= 3 ,0,0
       0    .035       0  529.75    .018       0  611.84    .035       0
Levee=-1,391.34,68.32965,-1,642.95,68.31428,	341,	340
Bank Sta=529.75,611.84
XS Rating Curve= 0 ,0
Exp/Cntr=0.3,0.1

Type RM Length L Ch R = 1 ,3799.865,97.98,65.86,33.74
XS GIS Cut Line= 6
    1075901.2017    1572864.5273    1075907.5517    1573321.7282
    1075803.0057    1573387.9396    1075791.9814    1573394.7534
     1075786.682    1573526.0121    1075825.0015    1574340.9053
#Sta/Elev= 30
       0   67.93   42.55      68   55.67    67.5   89.53   67.83  194.85    67.5
  271.96      68  371.73   67.85  373.03   68.28  397.55   68.28  418.66   66.79
  498.99    66.7  519.99    65.2  559.99    65.2  580.99   66.68  679.75   66.68
  700.84   68.18  725.34   68.18  727.42    67.5  744.08    67.5  777.85   66.42
  785.42      67  792.32   68.67   798.8   68.88  810.47      68  823.59   67.63
  900.37      67 1083.71    66.5 1220.45      67 1372.93      66 1541.11      66
#Mann= 3 ,0,0
       0    .035       0  498.99    .018       0  580.99    .035       0
Levee=-1,397.48,68.28445,-1,700.83,68.17663,	341,	340
Bank Sta=498.99,580.99
XS Rating Curve= 0 ,0
Exp/Cntr=0.3,0.1

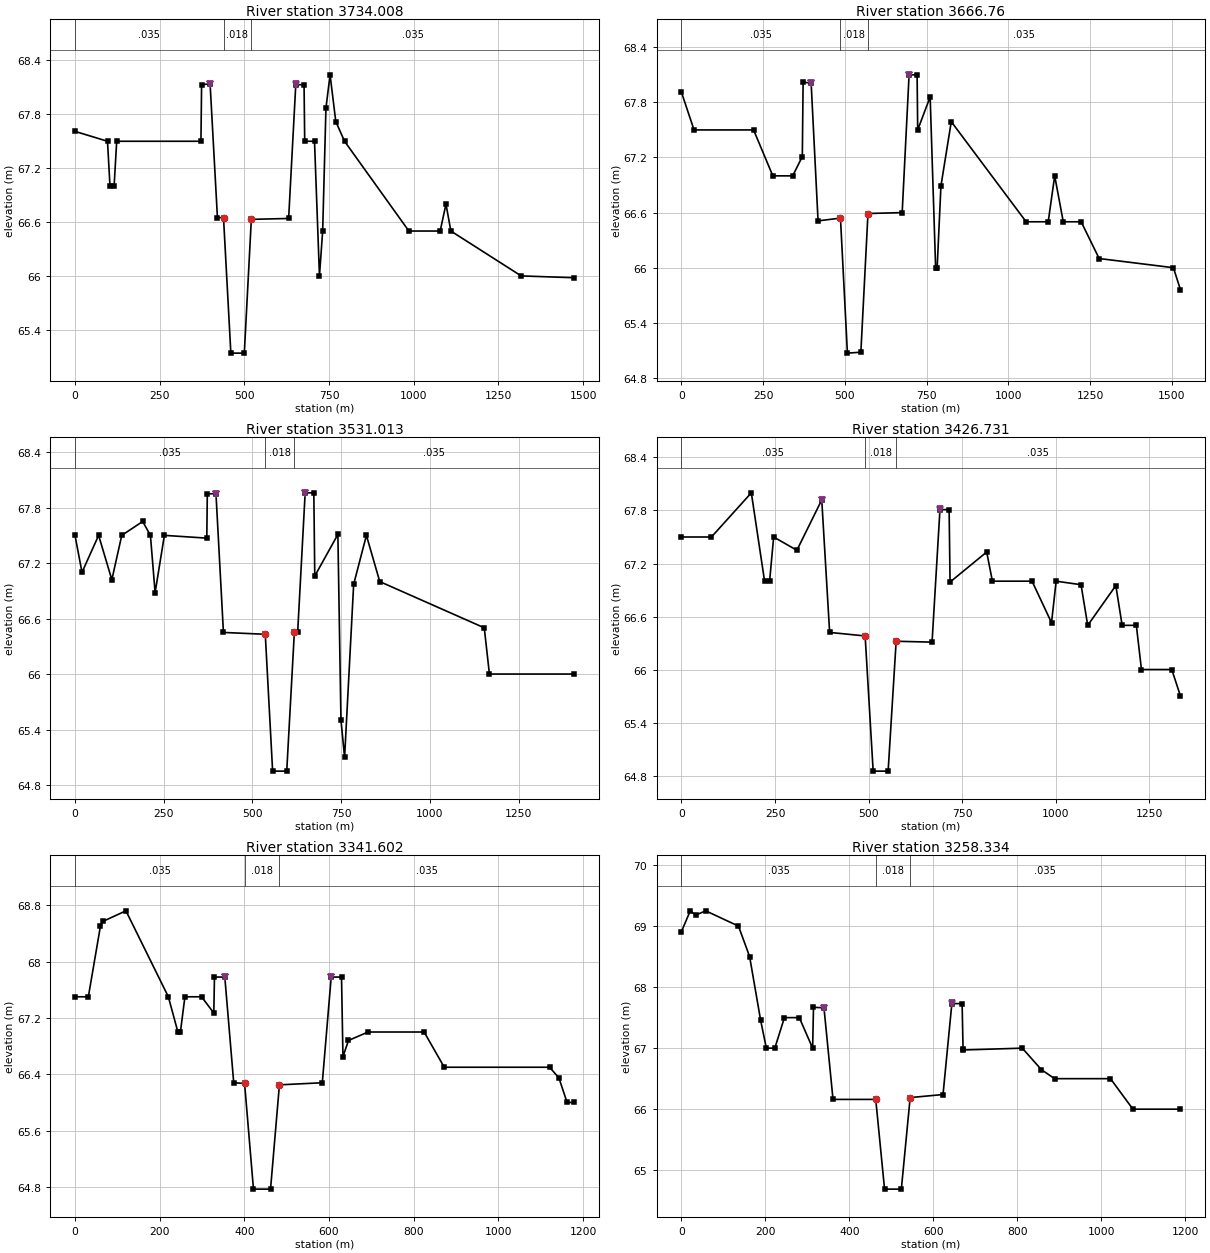
Type RM Length L Ch R = 1 ,3734.008,108.06,67.25,26.76
XS GIS Cut Line= 5
    1075804.4698    1572849.9223    1075789.6089    1573223.3002
    1075795.2326    1573287.7291    1075742.7034    1573519.6107
    1075743.5097    1574316.3519
#Sta/Elev= 30
       0   67.61   95.96    67.5  103.26      67  115.44      67  123.08    67.5
  371.76    67.5  373.67   68.13  398.79   68.14  420.41   66.65  438.35   66.65
  460.03   65.14  499.76   65.14  520.46   66.63  630.59   66.64  651.64   68.13
   676.1   68.13  678.02    67.5  706.95    67.5  721.56      66  731.03    66.5
   740.7   67.87  752.87   68.24  769.74   67.72   795.6    67.5   985.5    66.5
 1077.86    66.5 1094.95    66.8 1109.44    66.5 1316.99      66 1472.85   65.98
#Mann= 3 ,0,0
       0    .035       0  438.35    .018       0  520.46    .035       0
Levee=-1,398.75,68.13969,-1,651.64,68.13318,	341,	340
Bank Sta=438.35,520.46
XS Rating Curve= 0 ,0
Exp/Cntr=0.3,0.1

Type RM Length L Ch R = 1 ,3666.76 ,97.63,135.75,173.54
XS GIS Cut Line= 6
     1075756.633    1572841.4556    1075690.9219    1573207.6782
    1075669.0029    1573284.6865     1075751.079    1573369.0688
    1075711.3641    1573514.6497    1075685.5129    1574319.7386
#Sta/Elev= 30
       0   67.91   38.47    67.5  220.65    67.5  279.46      67   340.2      67
  369.66   67.21  372.07   68.02  396.65   68.01   417.8   66.51  486.35   66.54
  507.57   65.07  548.72   65.08  570.49   66.59  675.08    66.6  696.21    68.1
  720.75    68.1  722.55    67.5  760.66   67.86  777.38      66  782.08      66
  793.63   66.89  825.25   67.59 1054.23    66.5 1121.74    66.5 1141.59      67
 1167.79    66.5  1222.5    66.5 1277.57    66.1 1504.65      66 1526.26   65.76
#Mann= 3 ,0,0
       0    .035       0  486.35    .018       0  570.49    .035       0
Levee=-1,396.65,68.01248,-1,696.21,68.0983,	341,	340
Bank Sta=486.35,570.49
XS Rating Curve= 0 ,0
Exp/Cntr=0.3,0.1

Type RM Length L Ch R = 1 ,3531.013,59.63,104.28,148.99
XS GIS Cut Line= 5
    1075689.3229    1572830.0256     1075634.901    1573198.8102
    1075614.3722    1573360.8447    1075592.9913    1573495.9114
    1075549.9401    1574227.6634
#Sta/Elev= 30
       0    67.5   19.76    67.1   66.56    67.5  103.84   67.02  131.76    67.5
   190.7   67.65   212.5    67.5  225.73   66.88  251.83    67.5  371.32   67.47
  372.78   67.95  397.19   67.95   418.2   66.45  536.11   66.43  556.78   64.95
  596.55   64.95  618.12   66.46  627.46   66.46  648.46   67.96  672.86   67.96
  675.55   67.06  740.63   67.51  749.32    65.5  759.58    65.1  785.09   66.97
  821.01    67.5  858.59      67 1153.07    66.5 1167.56      66 1405.87      66
#Mann= 3 ,0,0
       0    .035       0  536.11    .018       0  618.12    .035       0
Levee=-1,397.19,67.95079,-1,648.45,67.95578,	341,	340
Bank Sta=536.11,618.12
XS Rating Curve= 0 ,0
Exp/Cntr=0.3,0.1

Type RM Length L Ch R = 1 ,3426.731,129.79,85.13,40.45
XS GIS Cut Line= 6
    1075627.4103    1572844.6306    1075607.1429    1573194.4161
    1075598.2002    1573311.9916    1075498.3482    1573345.6608
      1075481.36    1573355.1716    1075441.9899    1574094.3131
#Sta/Elev= 30
       0    67.5   80.12    67.5   186.7      68  222.09      67  235.53      67
  246.34    67.5  308.41   67.35  374.85   67.92  395.92   66.42  490.78   66.38
  512.21   64.85  552.21   64.85  573.66   66.32   669.6   66.31  690.69   67.81
  715.19   67.81  717.68   66.99  815.59   67.33  830.81      67  936.77      67
  988.77   66.53 1001.15      67 1067.64   66.96 1085.51    66.5 1160.61   66.95
 1177.49    66.5 1215.41    66.5 1229.11      66 1310.09      66 1333.33    65.7
#Mann= 3 ,0,0
       0    .035       0  490.78    .018       0  573.66    .035       0
Levee=-1,374.85,67.91953,-1,690.69,67.81227,	341,	340
Bank Sta=490.78,573.66
XS Rating Curve= 0 ,0
Exp/Cntr=0.3,0.1

Type RM Length L Ch R = 1 ,3341.602,126.01,83.27,40.5
XS GIS Cut Line= 5
    1075535.9701    1572849.7106    1075492.6232    1573176.2878
    1075477.1842    1573245.7481    1075441.3828     1573471.912
    1075373.4098     1574016.843
#Sta/Elev= 30
       0    67.5   31.53    67.5   60.02    68.5   65.89   68.57  120.34   68.72
  220.52    67.5  243.08      67  249.02      67  259.66    67.5  298.88    67.5
  327.91   67.27  329.44   67.78  353.89   67.78  374.93   66.28   400.6   66.27
  421.58   64.77  461.92   64.77  482.88   66.25  584.18   66.28  605.18   67.78
  629.58   67.78  632.97   66.65  646.01   66.88   692.3      67  824.68      67
  872.25    66.5 1120.97    66.5 1143.02   66.35 1162.39      66 1178.73      66
#Mann= 3 ,0,0
       0    .035       0   400.6    .018       0  482.88    .035       0
Levee=-1,353.89,67.78058,-1,605.18,67.77722,	341,	340
Bank Sta=400.6,482.88
XS Rating Curve= 0 ,0
Exp/Cntr=0.3,0.1

Type RM Length L Ch R = 1 ,3258.334,45.21,87.96,130.7
XS GIS Cut Line= 6
      1075468.66    1572854.7906    1075397.7402     1573161.268
    1075350.5497    1573280.2415    1075429.7808    1573344.9978
    1075402.6022    1573465.7731    1075323.8797    1573980.0129
#Sta/Elev= 30
       0   68.91   20.91   69.25   34.05   69.18   57.75   69.25  135.83      69
   162.4    68.5  188.54   67.46  202.25      67  222.42      67  245.32    67.5
  280.79    67.5  312.56      67  314.58   67.67  339.58   67.66   361.1   66.16
  462.89   66.16  483.89   64.69  523.89   64.69  544.89   66.19   623.2   66.24
  644.24   67.73  668.69   67.73  670.95   66.98  671.58   66.97  812.08      67
  857.18   66.65  889.04    66.5 1022.19    66.5 1075.62      66 1188.92      66
#Mann= 3 ,0,0
       0    .035       0  462.89    .018       0  544.89    .035       0
Levee=-1,339.58,67.66425,-1,644.24,67.73341,	341,	340
Bank Sta=462.89,544.89
XS Rating Curve= 0 ,0
Exp/Cntr=0.3,0.1

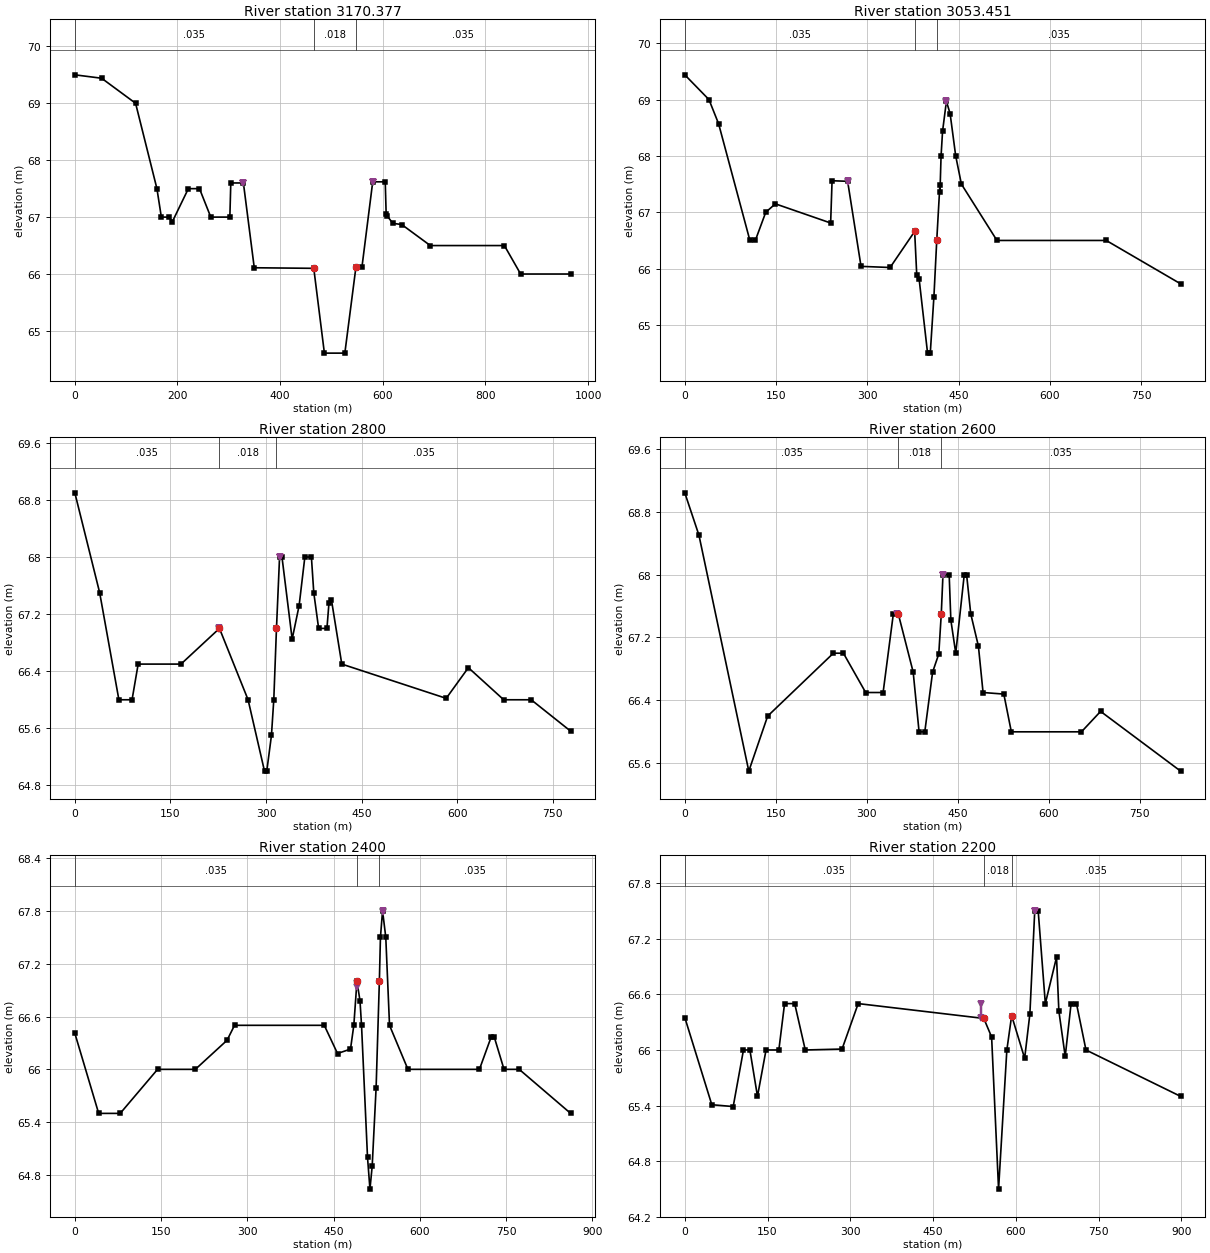
Type RM Length L Ch R = 1 ,3170.377,105.01,116.93,129.01
XS GIS Cut Line= 5
    1075430.5599    1572862.4107    1075337.9403    1573151.8017
    1075332.7697    1573282.7815    1075306.2176    1573450.5156
    1075204.4994    1573797.1325
#Sta/Elev= 29
       0    69.5   52.22   69.44  118.38      69  159.94    67.5  168.56      67
  183.23      67  190.02   66.92  221.16    67.5  242.88    67.5  264.87      67
  302.03      67  303.85    67.6  328.42    67.6  349.57   66.11  465.52    66.1
  486.21   64.61  526.05   64.61  547.63   66.12  559.36   66.12  580.36   67.62
  604.76   67.62  606.53   67.06  608.65   67.02  619.57   66.89   636.8   66.87
  692.59    66.5  836.87    66.5  868.55      66  965.99      66
#Mann= 3 ,0,0
       0    .035       0  465.52    .018       0  547.63    .035       0
Levee=-1,328.42,67.60355,-1,580.36,67.6181,	341,	340
Bank Sta=465.52,547.63
XS Rating Curve= 0 ,0
Exp/Cntr=0.3,0.1

Type RM Length L Ch R = 1 ,3053.451,270.63,253.45,287.83
XS GIS Cut Line= 4
    1075376.9439    1572916.6924    1075314.3958    1573116.1355
    1075171.5789    1573401.7692    1075008.1404    1573637.4453
#Sta/Elev= 30
       0   69.44   39.74      69   55.61   68.57  107.01    66.5  115.95    66.5
  133.06      67   148.9   67.15  239.77   66.81  242.11   67.56  267.71   67.55
  289.73   66.04  337.54   66.02  377.88   66.66  381.37   65.88   385.3   65.81
  399.12    64.5  403.57    64.5  409.55    65.5  414.21    66.5  419.34   67.48
  419.54   67.36  421.31      68  423.79   68.44   430.1   68.97  436.21   68.75
  445.38      68  454.75    67.5   513.2    66.5  692.88    66.5  815.17   65.73
#Mann= 3 ,0,0
       0    .035       0  377.88    .018       0  414.21    .035       0
Levee=-1,267.7,67.54606,-1,429.85,68.98,	341,
Bank Sta=377.88,414.21
XS Rating Curve= 0 ,0
Exp/Cntr=0.3,0.1

Type RM Length L Ch R = 1 ,2800    ,173.16,200,161.41
XS GIS Cut Line= 4
    1075085.5796    1572874.2425    1075009.8838    1573116.4647
    1075027.4083    1573337.2613    1074970.9089    1573634.4449
#Sta/Elev= 30
       0    68.9   38.96    67.5   69.12      66   89.75      66   99.35    66.5
  166.51    66.5  226.86      67  271.77      66  297.53      65   301.1      65
  308.41    65.5  312.09      66  316.31      67  321.15      68  324.95      68
  340.91   66.85  351.83   67.32  360.81      68   371.1      68  374.83    67.5
  382.45      67  395.47      67  398.59   67.35  402.53    67.4  418.76    66.5
  582.56   66.02  617.34   66.45  672.77      66  715.87      66  777.77   65.56
#Mann= 3 ,0,0
       0    .035       0  226.86    .018       0  316.31    .035       0
Levee=-1,225.59,67,-1,321.82,68,,
Bank Sta=226.86,316.31
XS Rating Curve= 0 ,0
Exp/Cntr=0.3,0.1

Type RM Length L Ch R = 1 ,2600    ,229.25,200,147.14
XS GIS Cut Line= 5
    1074975.7773    1572839.8466     1074932.279    1573199.6772
    1074894.8615    1573241.6759     1074938.394    1573378.7808
    1074939.9526    1573633.6511
#Sta/Elev= 30
       0   69.04   23.35    68.5   105.5    65.5  136.59    66.2  244.93      67
  261.49      67   298.2    66.5  326.92    66.5  343.78    67.5  351.98    67.5
  376.49   66.76  386.23      66  395.64      66  408.54   66.76   418.7   66.99
  422.83    67.5  425.62      68  435.84      68  438.62   67.42  446.68      67
  460.71      68  464.56      68  471.42    67.5  484.04   67.09  491.71    66.5
  525.94   66.48  538.33      66  653.93      66  685.49   66.26  817.42    65.5
#Mann= 3 ,0,0
       0    .035       0  351.98    .018       0  422.83    .035       0
Levee=-1,350.49,67.5,-1,426.3,68,,
Bank Sta=351.98,422.83
XS Rating Curve= 0 ,0
Exp/Cntr=0.3,0.1

Type RM Length L Ch R = 1 ,2400    ,152.29,200,272.51
XS GIS Cut Line= 5
     1074802.369    1572827.1995     1074795.417    1573204.1704
    1074850.8937    1573309.4669    1074889.7875    1573309.4669
    1074915.3463    1573636.0324
#Sta/Elev= 30
       0   66.41   41.48    65.5   78.92    65.5  143.92      66  209.61      66
  264.77   66.33  277.81    66.5  433.93    66.5  456.96   66.18  479.54   66.23
  485.32    66.5  490.75      67  496.05   66.78  498.73    66.5  509.15      65
  513.38   64.64  517.26    64.9  524.09   65.79  529.76      67  531.63    67.5
  535.31    67.8  540.91    67.5  547.43    66.5  579.46      66  703.84      66
  724.39   66.37  729.48   66.37   746.6      66  773.03      66  862.51    65.5
#Mann= 3 ,0,0
       0    .035       0  490.75    .018       0  529.76    .035       0
Levee=-1,490.04,66.98,-1,535.21,67.8,,
Bank Sta=490.75,529.76
XS Rating Curve= 0 ,0
Exp/Cntr=0.3,0.1

Type RM Length L Ch R = 1 ,2200    ,201.37,200,132.8
XS GIS Cut Line= 6
    1074705.0021    1572829.3162    1074705.5453     1573245.692
    1074757.8285    1573373.6044    1074786.6337    1573352.2546
     1074828.845    1573423.1331    1074885.9775    1573641.5886
#Sta/Elev= 30
       0   66.35   48.93   65.41   87.71   65.39  106.33      66  117.97      66
  131.74    65.5  147.23      66  170.45      66  180.84    66.5  199.17    66.5
  218.35      66  285.03   66.01  314.27    66.5  541.96   66.34  556.12   66.14
  568.71    64.5  583.73      66  592.44   66.37  615.99   65.91  625.49   66.39
  634.28    67.5  640.51    67.5  653.48    66.5  673.79      67  678.01   66.42
  689.52   65.93  700.16    66.5  709.92    66.5  727.14      66  898.71    65.5
#Mann= 3 ,0,0
       0    .035       0  541.96    .018       0  592.44    .035       0
Levee=-1,536.61,66.5,-1,634.59,67.5,,
Bank Sta=541.96,592.44
XS Rating Curve= 0 ,0
Exp/Cntr=0.3,0.1