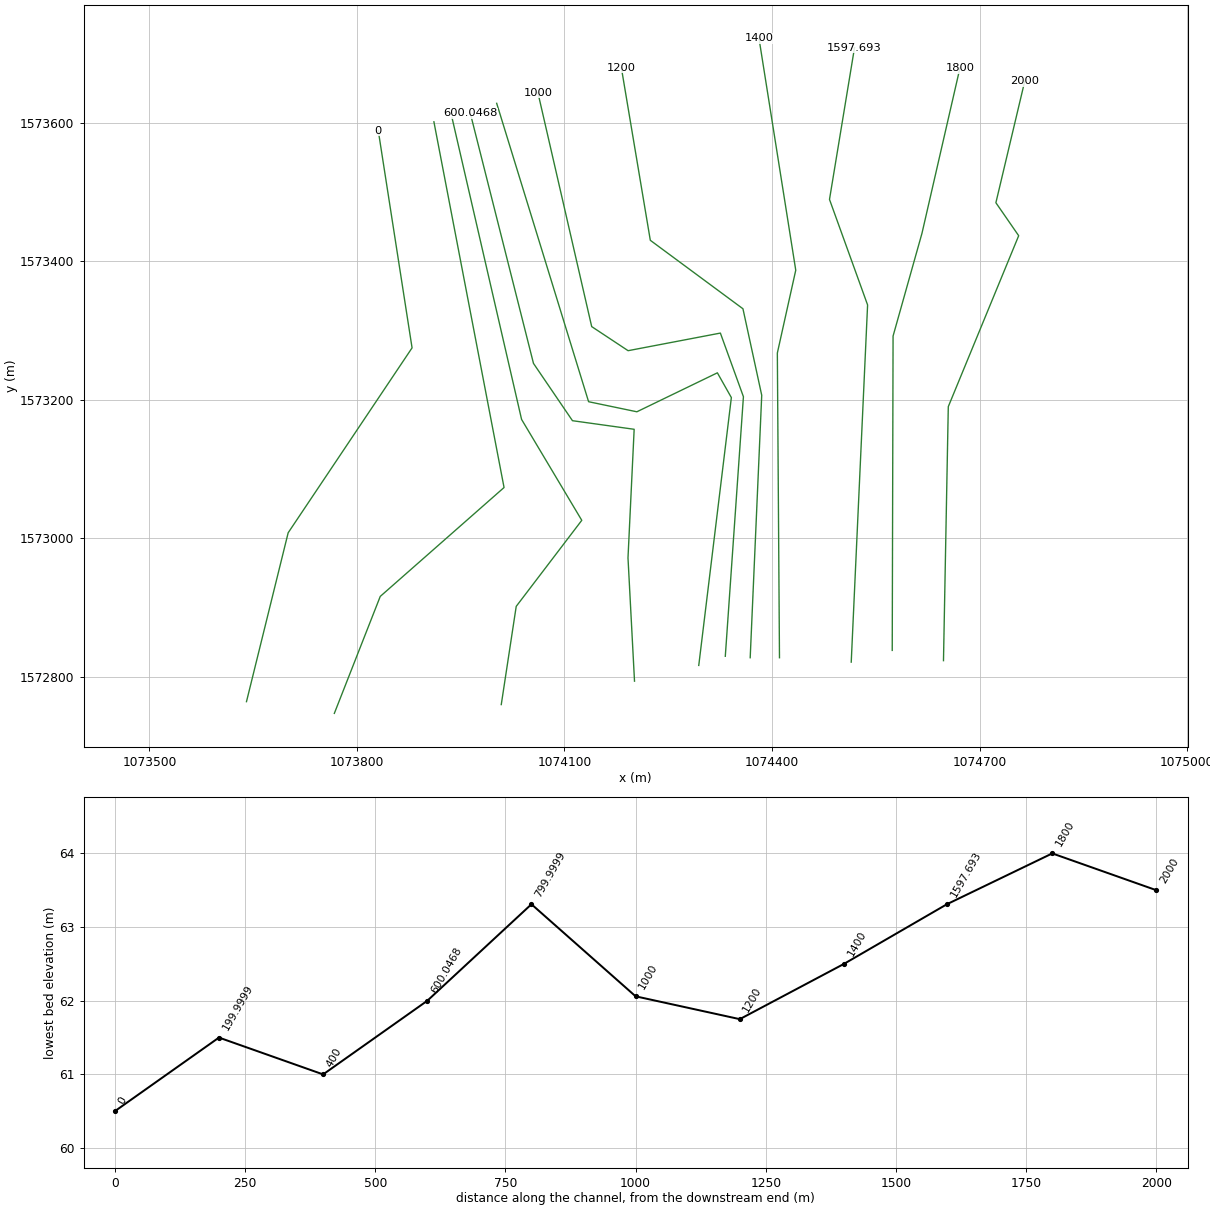
HEC-RAS study HECRAS_v1.prj: HECRAS_v1

--- HECRAS_v1.g02 (geometry) --- (continued)

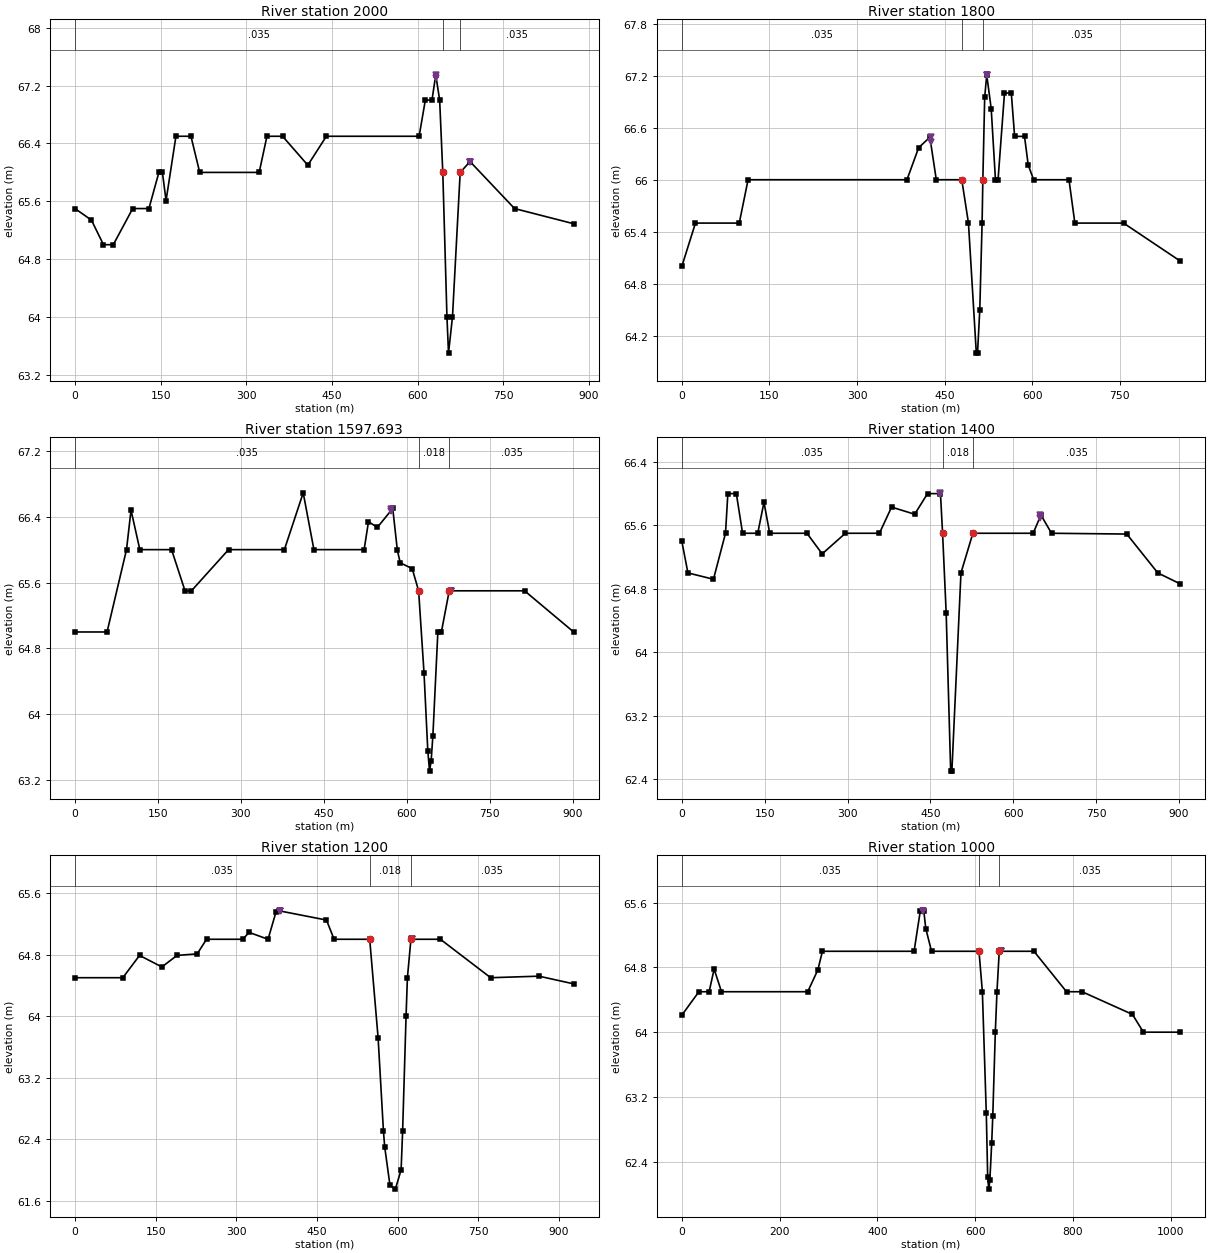
Type RM Length L Ch R = 1 ,2000    ,210.95,200,171.25
XS GIS Cut Line= 5
     1074647.852    1572822.9662    1074654.8093    1573190.1452
    1074756.5623    1573437.2428    1074723.6121    1573484.9154
    1074765.3273    1573660.6387
#Sta/Elev= 30
       0    65.5   28.84   65.34   49.86      65   67.08      65  101.06    65.5
  129.45    65.5  146.89      66  153.06      66  159.45   65.61  176.74    66.5
  203.04    66.5  218.36      66  322.49      66  336.06    66.5  363.46    66.5
  407.64    66.1  440.13    66.5   602.5    66.5  613.36      67  625.02      67
  631.61   67.35  638.46      67  643.93      66  651.23      64  653.95    63.5
  660.89      64  674.39      66  691.66   66.15  769.56    65.5  873.03   65.29
#Mann= 3 ,0,0
       0    .035       0  643.93    .018       0  674.39    .035       0
Levee=-1,632.36,67.35,-1,691.68,66.15,,
Bank Sta=643.93,674.39
XS Rating Curve= 0 ,0
Exp/Cntr=0.3,0.1

Type RM Length L Ch R = 1 ,1800    ,178.48,202.31,216.87
XS GIS Cut Line= 4
    1074573.7685    1572837.7829    1074574.9818    1573292.1952
    1074616.7788    1573440.8024    1074671.6646    1573679.6887
#Sta/Elev= 30
       0      65   23.35    65.5   98.36    65.5  113.46      66  385.56      66
  405.57   66.37  424.79   66.49  435.77      66   479.4      66  490.84    65.5
  504.29      64  506.36      64  510.23    64.5  514.19    65.5  515.48      66
  518.62   66.95  522.13   67.21  529.78   66.82  537.07      66  541.51      66
  552.55      67  564.19      67  569.89    66.5  586.83    66.5  593.16   66.17
  602.47      66  662.98      66  673.03    65.5  756.43    65.5   853.9   65.06
#Mann= 3 ,0,0
       0    .035       0   479.4    .018       0  515.48    .035       0
Levee=-1,425.92,66.49,-1,522.13,67.21,,
Bank Sta=479.4,515.48
XS Rating Curve= 0 ,0
Exp/Cntr=0.3,0.1

Type RM Length L Ch R = 1 ,1597.693,214.45,197.69,185.65
XS GIS Cut Line= 4
    1074514.5018    1572820.8495    1074538.1554    1573337.1533
    1074483.0853    1573489.6785    1074519.2643    1573709.0575
#Sta/Elev= 30
       0      65   57.98      65   93.14      66  101.31   66.48  117.22      66
   174.6      66  198.88    65.5   210.5    65.5  277.59      66  378.51      66
  412.53   66.69   431.9      66  522.64      66  530.54   66.34   546.5   66.27
  574.38    66.5  582.74   65.99  587.92   65.84  609.49   65.77  621.15    65.5
  630.92    64.5  637.71   63.56  640.84   63.31  643.73   63.43  646.92   63.74
  655.91      65  662.28      65  676.48    65.5  812.64    65.5  901.35      65
#Mann= 3 ,0,0
       0    .035       0  621.15    .018       0  676.48    .035       0
Levee=-1,571.27,66.49,-1,680,65.5,,
Bank Sta=621.15,676.48
XS Rating Curve= 0 ,0
Exp/Cntr=0.3,0.1

Type RM Length L Ch R = 1 ,1400    ,134.48,200,216.46
XS GIS Cut Line= 4
    1074410.7849    1572827.1995    1074407.7038    1573267.6814
     1074434.311    1573387.4131    1074381.1515    1573722.5513
#Sta/Elev= 30
       0    65.4   11.05      65   57.27   64.92   79.08    65.5   83.31      66
   98.66      66  109.99    65.5  137.43    65.5  148.67   65.89  159.11    65.5
  226.48    65.5  254.02   65.24  296.01    65.5  357.63    65.5  379.63   65.83
  421.45   65.74  444.65      66  468.11      66  471.94    65.5   478.4    64.5
  486.58    62.5  488.75    62.5   505.2      65  526.76    65.5  635.79    65.5
  649.99   65.73  669.06    65.5  805.29   65.49  861.41      65  902.47   64.86
#Mann= 3 ,0,0
       0    .035       0  471.94    .018       0  526.76    .035       0
Levee=-1,466.86,66.01,-1,647.9,65.73,,
Bank Sta=471.94,526.76
XS Rating Curve= 0 ,0
Exp/Cntr=0.3,0.1

Type RM Length L Ch R = 1 ,1200    ,66.77,200,200.75
XS GIS Cut Line= 5
    1074368.4515    1572827.1995    1074385.1202    1573206.6128
    1074357.9785    1573331.6301    1074224.0756    1573430.5995
    1074182.1844    1573680.2179
#Sta/Elev= 29
       0    64.5   88.97    64.5  120.09   64.79  161.64   64.64  189.73   64.79
  227.26   64.81  244.67      65  312.31      65  323.63   65.09  359.04      65
  374.04   65.36  379.78   65.37   467.7   65.25  481.84      65  548.07      65
  563.68   63.72  573.67    62.5  575.96    62.3  585.76    61.8  595.77   61.75
  606.47      62  609.26    62.5  615.68      64  618.19    64.5  624.74      65
  679.54      65  773.02    64.5  862.85   64.52  927.33   64.42
#Mann= 3 ,0,0
       0    .035       0  548.07    .018       0  624.74    .035       0
Levee=-1,380.67,65.37,-1,626.35,65,,
Bank Sta=548.07,624.74
XS Rating Curve= 0 ,0
Exp/Cntr=0.3,0.1

Type RM Length L Ch R = 1 ,1000    ,254.92,200,253.54
XS GIS Cut Line= 6
    1074332.4681    1572829.3162    1074358.6619    1573204.4961
    1074325.3532    1573296.4952    1074191.9693    1573271.0397
    1074139.3303     1573305.863    1074061.5342    1573644.2345
#Sta/Elev= 30
       0   64.21   34.97    64.5   55.86    64.5   66.14   64.78   81.16    64.5
  257.52    64.5  278.28   64.77  287.63      65  475.11      65  487.84    65.5
  494.94    65.5  499.07   65.28  510.83      65  607.92      65   614.8    64.5
  622.81      63  625.67   62.21  627.91   62.06  630.11   62.17  633.89   62.63
  636.05   62.96  641.27      64  644.66    64.5  649.32      65  720.32      65
  786.94    64.5  818.68    64.5  921.71   64.22  944.22      64 1020.04      64
#Mann= 3 ,0,0
       0    .035       0  607.92    .018       0  649.32    .035       0
Levee=-1,493.68,65.5,-1,652.08,65,,
Bank Sta=607.92,649.32
XS Rating Curve= 0 ,0
Exp/Cntr=0.3,0.1

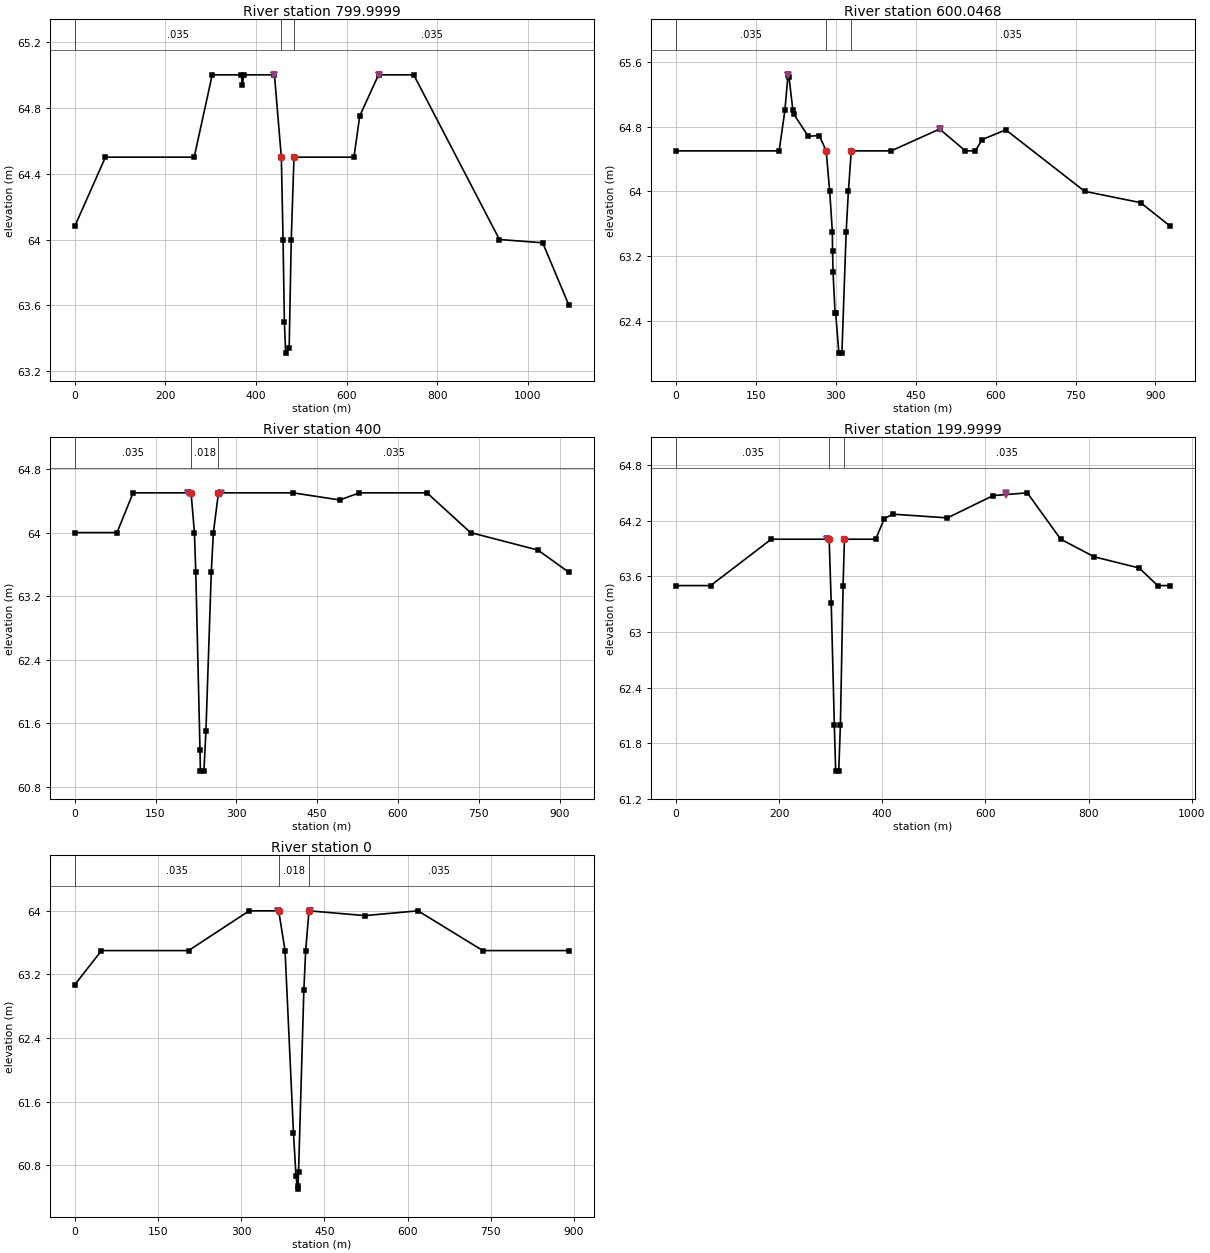
Type RM Length L Ch R = 1 ,799.9999,294.09,199.95,86.36
XS GIS Cut Line= 6
    1074294.1034     1572816.087    1074341.2283    1573203.2294
    1074321.0168    1573239.0549    1074204.6368    1573182.7241
    1074134.8528    1573197.2763    1074002.0028     1573628.624
#Sta/Elev= 22
       0   64.08   67.69    64.5  263.62    64.5  303.38      65  367.67      65
  369.78   64.94  373.48      65  440.71      65  455.92    64.5   459.7      64
  462.65    63.5  465.46   63.31  473.18   63.34  477.84      64  483.82    64.5
  616.16    64.5  628.94   64.75  670.41      65  748.08      65  937.24      64
 1032.72   63.98 1090.67    63.6
#Mann= 3 ,0,0
       0    .035       0  455.92    .018       0  483.82    .035       0
Levee=-1,439.54,65,-1,672.12,65,,
Bank Sta=455.92,483.82
XS Rating Curve= 0 ,0
Exp/Cntr=0.3,0.1

Type RM Length L Ch R = 1 ,600.0468,171.38,200.05,152.94
XS GIS Cut Line= 6
    1074201.2345    1572793.3328    1074191.8097    1572971.5487
    1074200.7204    1573157.4253    1074111.5405    1573169.8356
    1074055.1842    1573252.6504    1073963.9027    1573614.0719
#Sta/Elev= 30
       0    64.5  193.71    64.5  204.47      65  210.37   65.44  212.23   65.41
  219.55      65  221.68   64.95  248.33   64.68  268.99   64.69  281.96    64.5
   288.6      64  293.57    63.5  293.96   63.26  294.89      63  298.62    62.5
  299.76    62.5  305.81      62  311.51      62  319.51    63.5  323.67      64
  329.11    64.5   403.9    64.5  494.96   64.77  543.24    64.5  561.83    64.5
  574.89   64.64  619.07   64.76  767.17      64  872.08   63.86  927.54   63.57
#Mann= 3 ,0,0
       0    .035       0  281.96    .018       0  329.11    .035       0
Levee=-1,210.5,65.44,-1,495.67,64.77,,
Bank Sta=281.96,329.11
XS Rating Curve= 0 ,0
Exp/Cntr=0.3,0.1

Type RM Length L Ch R = 1 ,400     ,201.9,200,218.01
XS GIS Cut Line= 5
    1074008.6174     1572759.466    1074030.2323    1572901.4454
    1074124.9951    1573025.8185    1074037.9862    1573171.6877
    1073937.4443    1573607.7219
#Sta/Elev= 20
       0      64   78.46      64  108.31    64.5  215.89    64.5  222.13      64
  224.65    63.5  232.46   61.27  233.18      61  239.72      61  243.46    61.5
  253.42    63.5   257.3      64  266.76    64.5  404.91    64.5  491.96   64.41
  528.45    64.5  653.76    64.5  734.64      64  859.78   63.78   917.3    63.5
#Mann= 3 ,0,0
       0    .035       0  215.89    .018       0  266.76    .035       0
Levee=-1,210.7,64.5,-1,271.55,64.49,,
Bank Sta=215.89,266.76
XS Rating Curve= 0 ,0
Exp/Cntr=0.3,0.1

Type RM Length L Ch R = 1 ,199.9999,192.3,200,207.7
XS GIS Cut Line= 4
    1073767.3169     1572746.766    1073833.6822     1572915.828
    1074012.6483    1573073.2531    1073911.2505    1573601.9011
#Sta/Elev= 22
       0    63.5   67.28    63.5  184.83      64   297.1      64  301.12   63.31
  307.11      62  309.74    61.5  315.67    61.5  318.91      62  324.11    63.5
  326.74      64   387.3      64   403.9   64.22  419.97   64.27  526.46   64.23
  615.02   64.47  681.27    64.5  746.05      64  811.16   63.81   898.1   63.69
  934.08    63.5  958.26    63.5
#Mann= 3 ,0,0
       0    .035       0   297.1    .018       0  326.74    .035       0
Levee=-1,292.85,64,-1,639.85,64.5,,
Bank Sta=297.1,326.74
XS Rating Curve= 0 ,0
Exp/Cntr=0.3,0.1

Type RM Length L Ch R = 1 ,0       ,0,0,0
XS GIS Cut Line= 4
    1073640.3167    1572763.6994    1073700.5868    1573007.8409
    1073879.6812    1573275.1143    1073830.8171     1573589.201
#Sta/Elev= 18
       0   63.07   48.22    63.5  205.12    63.5  314.52      64  367.72      64
  379.18    63.5  394.34   61.21  398.95   60.66  401.86    60.5  402.68   60.54
  403.56   60.72  413.06      63  416.37    63.5  422.34      64  523.01   63.94
  618.92      64  735.75    63.5  891.07    63.5
#Mann= 3 ,0,0
       0    .035       0  367.72    .018       0  422.34    .035       0
Levee=-1,366.48,64,-1,423.86,64,,
Bank Sta=367.72,422.34
XS Rating Curve= 0 ,0
Exp/Cntr=0.3,0.1
LCMann Table=0

Chan Stop Cuts=-1
Use User Specified Reach Order=0
Composite Channel Slope=5

--- HECRAS_v1.g01 (geometry) ---

Geom Title=HECRAS_V1
Program Version=6.50

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
Junct Name=1
Junct Desc=, 0 , 0 ,-1 ,0
Up River,Reach=ARROYOELZORRO   ,ARRIBALAT1
Up River,Reach=LATERAL1        ,LATERAL1
Dn River,Reach=ARROYOELZORRO   ,ABAJOLAT1
Junc L&A=0,0
Junc L&A=0,0

River Reach=ARROYOELZORRO   ,ARRIBALAT1
Reach XY= 30
    1080707.4374    1573339.5833    1080687.7523    1573349.7434
    1080636.3172     1573396.416    1080550.5921    1573432.2935
    1080519.1595     1573427.531    1080513.4445     1573418.641
    1080528.0495    1573365.6184    1080525.5095    1573345.6159
     1080519.477    1573340.2184    1080492.1719    1573342.1234
    1080422.9568    1573444.6761     1080410.836    1573501.8389
    1080390.1985    1573530.9431    1080370.0901    1573533.8535
    1080237.7982    1573498.1347    1080173.2397    1573449.1867
     1080139.536     1573378.935    1080113.4599    1573351.9355
    1080078.0847    1573339.3843    1079986.1122    1573341.3699
    1079950.6469    1573323.7062    1079927.6034    1573291.4759
    1079900.9914    1573205.3105    1079862.9313    1573168.1895
     1079817.723    1573160.9037    1079670.7934    1573191.5554
     1079620.597    1573176.3569    1079592.4691    1573141.0177
    1079561.4908    1573047.14751079526.957286981573013.08491518

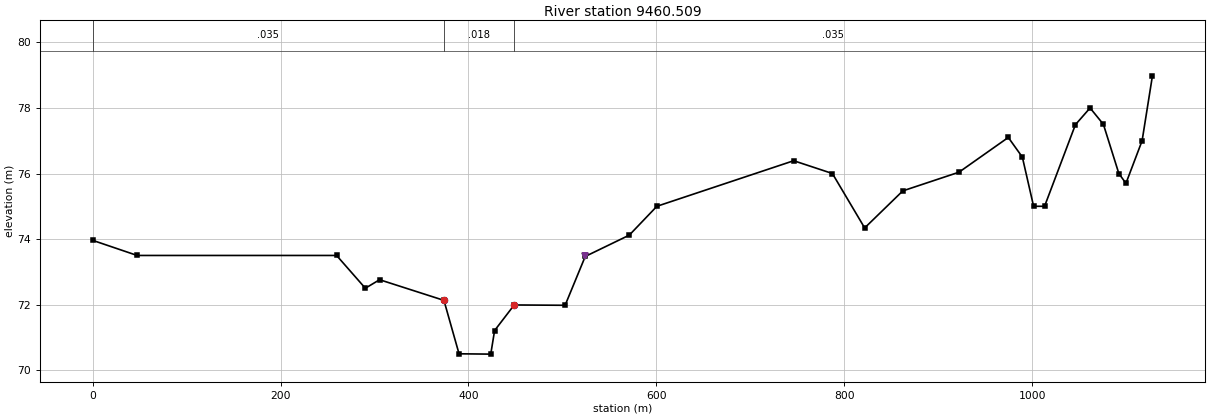
Type RM Length L Ch R = 1 ,9460.509,133.24,126.88,116.59
XS GIS Cut Line= 5
    1080161.9306    1572958.9446    1080152.5873    1573251.4818
    1080095.9811    1573338.1023    1079991.8435    1573479.1967
    1080234.5059    1573980.1218
#Sta/Elev= 30
       0   73.96   47.29    73.5  259.57    73.5  290.18    72.5  305.36   72.76
  373.85   72.13  389.93    70.5   423.7   70.49  427.79   71.21  448.67   71.99
  502.86   71.98  524.29   73.47  571.18   74.12  600.56      75  746.21   76.39
  787.41      76  821.77   74.34  862.37   75.47  922.19   76.04  974.68    77.1
  989.65    76.5 1001.61      75 1013.29      75 1046.14   77.49 1061.74      78
 1075.93    77.5 1092.37      76 1099.93    75.7 1117.14      77 1128.13   78.98
#Mann= 3 ,0,0
       0    .035       0  373.85    .018       0  448.67    .035       0
Levee=0,,,-1,524.29,73.47035,,	340
Bank Sta=373.85,448.67
XS Rating Curve= 0 ,0
Exp/Cntr=0.3,0.1

River Reach=LATERAL1        ,LATERAL1
Reach XY= 30
    1081518.2289    1570397.8927    1081511.8789    1570446.5761
    1081461.9254    1570477.9029    1081153.9498    1570449.5395
    1081055.5246    1570500.3396    1081080.9247    1570687.0299
    1080962.8144    1570866.1003    1080974.8794    1570928.9654
    1081079.6547    1571054.6957    1081159.0298    1571260.4361
    1081169.1898    1571352.5113    1081112.6747    1571549.9967
    1081025.0445    1571595.7168    1080818.6691    1571610.3218
     1080738.024    1571650.3269    1080469.4184    1571690.9669
     1080494.501     1571945.285    1080595.1487    1572107.2103
    1080410.6808    1572306.9182    1080314.1606    1572330.7307
    1080193.5104    1572296.1232    1080067.1451    1572348.5108
    1079951.8924     1572216.748    1079907.7598     1572209.763
    1079755.9945    1572323.4282    1079699.7969    1572415.5034
    1079697.2569    1572607.9088    1079609.6267    1572706.0165
    1079550.5716    1572842.85931079526.957286981573013.08491518

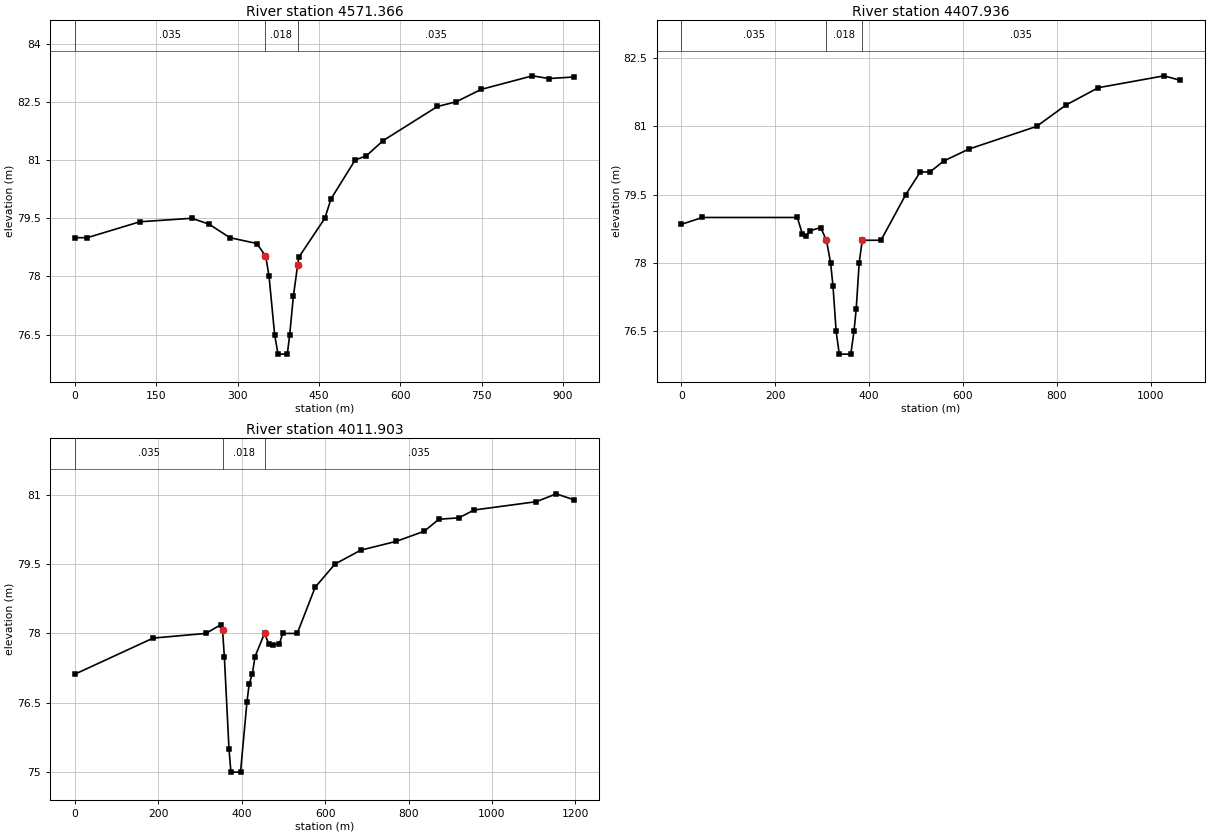
Type RM Length L Ch R = 1 ,4571.366,152.41,163.43,174.48
XS GIS Cut Line= 4
    1081393.6367    1570101.9591     1081441.199    1570332.9487
    1081520.5742    1570623.9909    1081860.0449    1570801.3279
#Sta/Elev= 28
       0      79   22.59      79  119.76   79.41  215.29    79.5  247.13   79.35
  285.76      79  335.51   78.85  350.79   78.54  352.15    78.5  357.99      78
   368.3    76.5  374.48      76   391.7      76  396.05    76.5  402.91    77.5
   410.8    78.3  413.09    78.5  460.85    79.5   472.3      80  516.74      81
  537.51   81.11  568.36    81.5  668.54   82.38  703.02    82.5  749.23   82.82
  843.89   83.17   874.3    83.1  920.51   83.14
#Mann= 3 ,0,0
       0    .035       0  350.79    .018       0   410.8    .035       0
Bank Sta=350.79,410.8
XS Rating Curve= 0 ,0
Exp/Cntr=0.3,0.1

Type RM Length L Ch R = 1 ,4407.936,443.54,396.03,348.49
XS GIS Cut Line= 4
    1081253.6858     1570142.195    1081335.3655    1570306.4903
    1081306.8387     1570585.175    1081790.6318    1570939.9528
#Sta/Elev= 28
       0   78.85   44.52      79  246.94      79  257.64   78.64  266.41    78.6
  274.78   78.71  296.55   78.78  309.08    78.5  317.91      78  322.92    77.5
  329.69    76.5  336.34      76  360.94      76  367.68    76.5  372.39   76.98
  378.77      78  385.27    78.5  425.28    78.5  477.96    79.5  508.98      80
  529.77      80  559.12   80.24  612.06    80.5  756.96      81  819.72   81.47
  888.71   81.85 1028.57   82.11 1063.56   82.01
#Mann= 3 ,0,0
       0    .035       0  309.08    .018       0  385.27    .035       0
Bank Sta=309.08,385.27
XS Rating Curve= 0 ,0
Exp/Cntr=0.3,0.1

Type RM Length L Ch R = 1 ,4011.903,127.44,145.59,163.74
XS GIS Cut Line= 4
    1080708.7383    1570491.5304    1080921.5307    1570597.1121
    1081192.4902    1570621.3451    1081748.8517    1571024.5408
#Sta/Elev= 30
       0   77.12  187.64    77.9  313.75      78  349.88   78.19  353.85   78.07
  358.17    77.5  369.27   75.51   373.9      75     397      75  412.29   76.51
  417.77   76.91  425.44   77.13  431.74    77.5  454.52      78  464.98   77.77
  475.37   77.75  490.31   77.78  498.14      78  532.95      78     576      79
  623.34    79.5  685.03    79.8  769.65   79.99  837.48   80.21  872.64   80.47
  920.67    80.5  956.98   80.67 1106.34   80.85 1154.21   81.02 1196.69   80.89
#Mann= 3 ,0,0
       0    .035       0  353.85    .018       0  454.52    .035       0
Bank Sta=353.85,454.52
XS Rating Curve= 0 ,0
Exp/Cntr=0.3,0.1