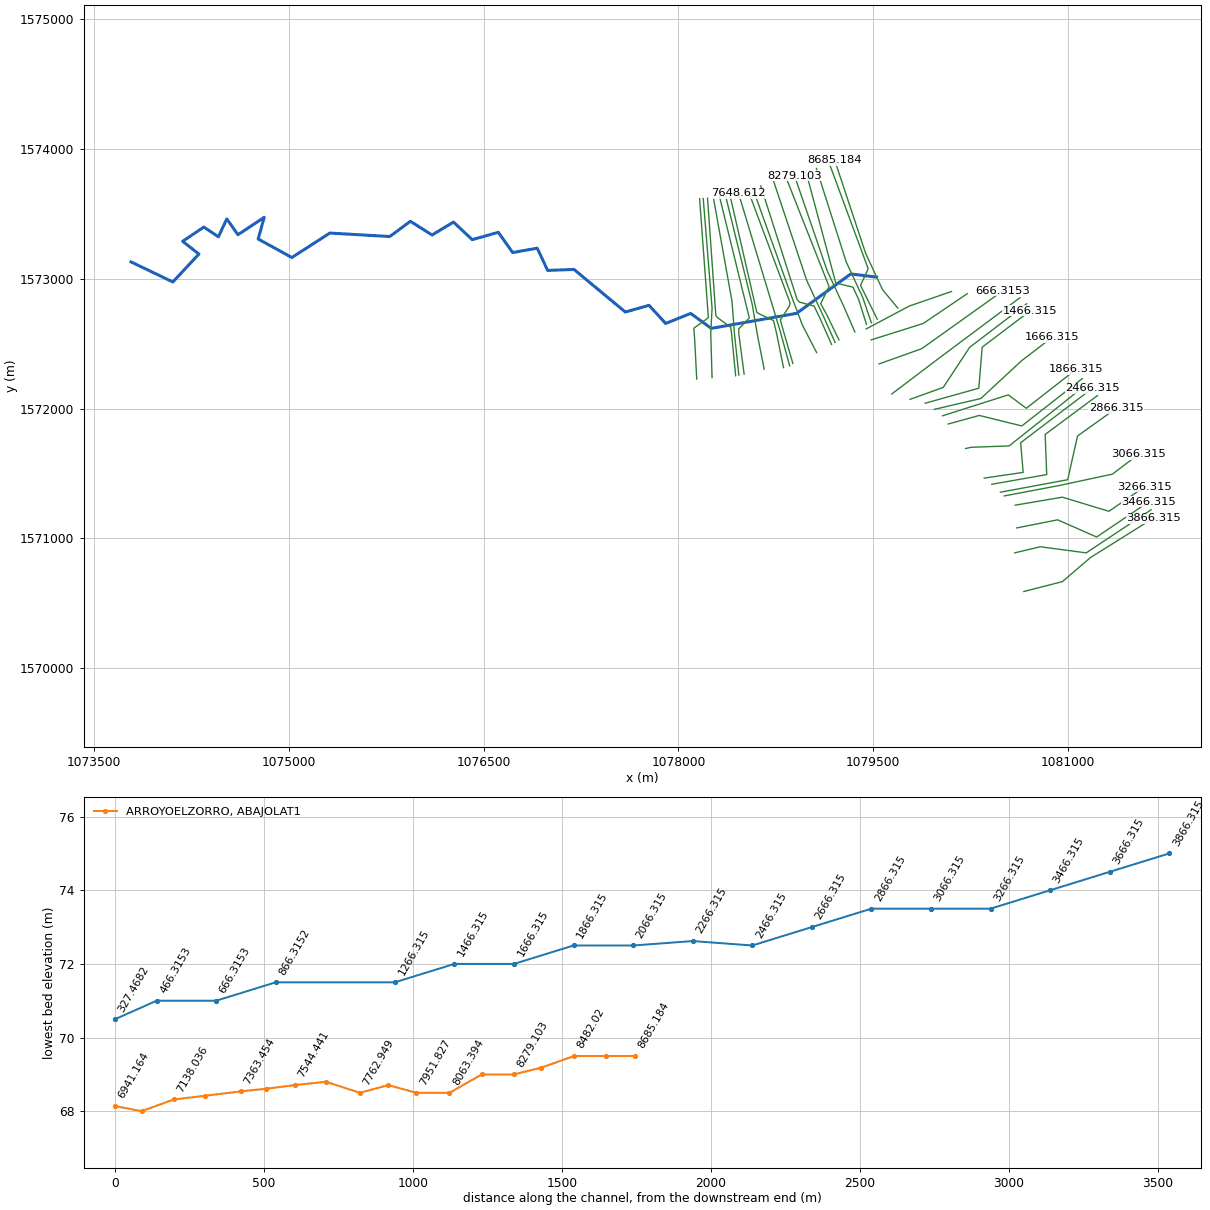
HEC-RAS study HECRAS_v1.prj: HECRAS_v1

--- HECRAS_v1.g01 (geometry) --- (continued)

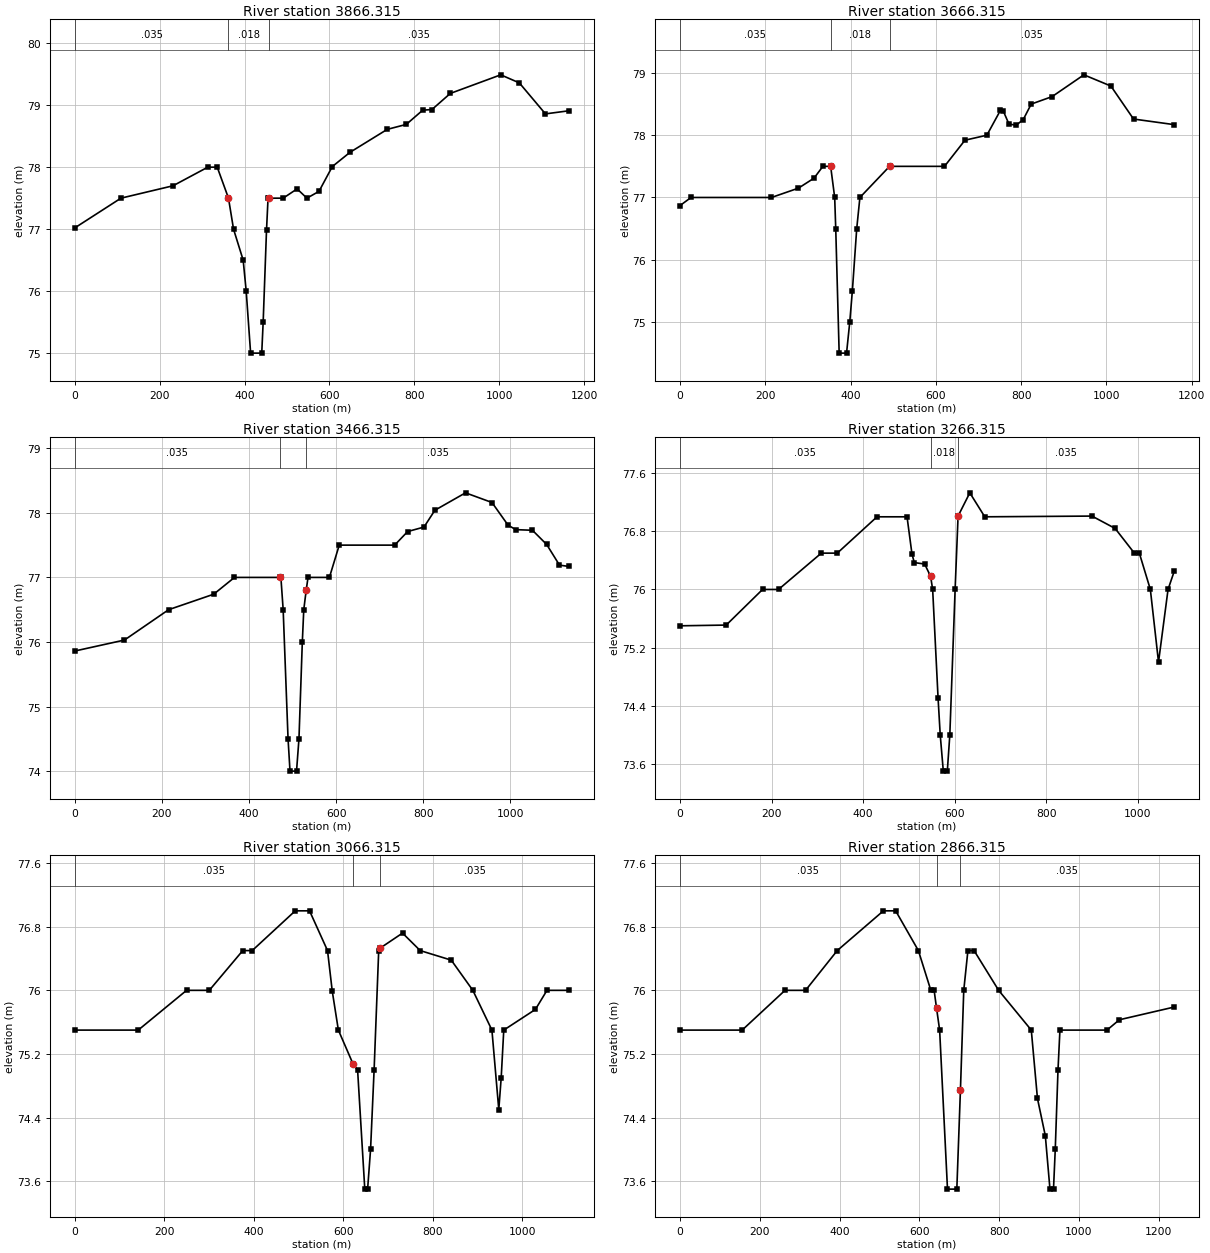
Type RM Length L Ch R = 1 ,3866.315,225.37,200,174.75
XS GIS Cut Line= 4
    1080660.7755    1570590.9984    1080958.4221    1570667.3234
    1081175.4436    1570853.3408    1081659.8275    1571156.3035
#Sta/Elev= 30
       0   77.02  108.83    77.5  231.58    77.7  313.44      78  335.73      78
  362.24    77.5  374.15      77  396.85    76.5  403.98      76  414.38      75
  440.59      75  443.95    75.5  451.88   76.99  455.46    77.5  458.75    77.5
  491.12    77.5  523.92   77.65  547.04    77.5   575.5   77.61  606.89   78.01
   648.6   78.24  736.29   78.61  781.16   78.69  819.96   78.92  841.68   78.93
  884.92   79.19 1003.74   79.49 1047.54   79.36 1109.03   78.86 1164.44   78.91
#Mann= 3 ,0,0
       0    .035       0  362.24    .018       0  458.75    .035       0
Bank Sta=362.24,458.75
XS Rating Curve= 0 ,0
Exp/Cntr=0.3,0.1

Type RM Length L Ch R = 1 ,3666.315,208.53,200,191.35
XS GIS Cut Line= 4
    1080591.5109    1570888.9546    1080787.6296    1570935.8453
     1081141.525    1570888.6593    1081641.6243    1571220.7033
#Sta/Elev= 30
       0   76.87    25.8      77  214.53      77  277.74   77.15  314.23   77.31
  335.05    77.5  353.25    77.5  362.73      77  365.18    76.5  373.23    74.5
  390.54    74.5  398.08      75  404.18    75.5   414.4    76.5  421.85      77
  491.43    77.5  620.24    77.5  668.23   77.92  719.59      78  751.47    78.4
  758.02   78.39  771.36   78.18  788.12   78.16  804.82   78.25   823.6    78.5
  872.58   78.62  947.16   78.97 1010.47   78.79 1063.58   78.26 1158.97   78.17
#Mann= 3 ,0,0
       0    .035       0  353.25    .018       0  491.43    .035       0
Bank Sta=353.25,491.43
XS Rating Curve= 0 ,0
Exp/Cntr=0.3,0.1

Type RM Length L Ch R = 1 ,3466.315,196.37,200,203.63
XS GIS Cut Line= 4
     1080606.752    1571080.9971    1080921.7505    1571143.2625
    1081221.8512    1571010.8655    1081624.2068    1571282.5043
#Sta/Elev= 30
       0   75.86   114.1   76.03  215.51    76.5  319.04   76.74  366.74      77
  471.31      77  473.26      77  478.48    76.5   489.7    74.5  494.18      74
  509.17      74  514.75    74.5  522.46      76  525.79    76.5  531.31    76.8
  535.57      77  584.65      77  607.19    77.5  734.46    77.5  764.18   77.71
  801.81   77.78  826.78   78.04  897.13   78.31  957.89   78.16  994.73   77.81
  1012.4   77.74 1050.79   77.73 1083.48   77.51 1112.89   77.19 1134.57   77.17
#Mann= 3 ,0,0
       0    .035       0  471.31    .018       0  531.31    .035       0
Bank Sta=471.31,531.31
XS Rating Curve= 0 ,0
Exp/Cntr=0.3,0.1

Type RM Length L Ch R = 1 ,3266.315,184.79,200,215.21
XS GIS Cut Line= 4
    1080595.0101    1571256.4086    1080957.9986    1571317.8097
    1081316.1518    1571209.0849    1081593.8293    1571399.4434
#Sta/Elev= 30
       0    75.5  100.87   75.51  180.22      76  215.05      76  308.54    76.5
   343.4    76.5  430.16      77  495.72      77  506.44   76.49  511.56   76.37
  534.21   76.35  547.17   76.18  551.66      76  563.52    74.5  568.16      74
  574.91    73.5  583.66    73.5  589.15      74  600.69      76  607.17   77.01
  632.77   77.33  665.46      77  899.52   77.01  950.09   76.84   992.1    76.5
 1002.96    76.5 1027.01      76 1044.84      75 1065.64      76  1079.1   76.25
#Mann= 3 ,0,0
       0    .035       0  547.17    .018       0  607.17    .035       0
Bank Sta=547.17,607.17
XS Rating Curve= 0 ,0
Exp/Cntr=0.3,0.1

Type RM Length L Ch R = 1 ,3066.315,165.67,200,234.33
XS GIS Cut Line= 4
    1080510.4142    1571327.4268    1080932.1897    1571407.2786
    1081343.4433    1571495.4044    1081546.3129    1571648.9608
#Sta/Elev= 30
       0    75.5  141.84    75.5  249.87      76  300.64      76  375.41    76.5
  396.52    76.5  492.71      77  524.68      77  564.84    76.5  575.39   75.99
  589.07    75.5  622.19   75.07  632.03      75   648.1    73.5  654.41    73.5
  661.02      74  668.93      75   679.2    76.5  682.19   76.53  732.44   76.72
  771.91    76.5   841.3   76.38  889.54      76  932.18    75.5  947.53    74.5
  952.91    74.9  958.64    75.5 1029.37   75.76  1055.2      76 1104.29      76
#Mann= 3 ,0,0
       0    .035       0  622.19    .018       0  682.19    .035       0
Bank Sta=622.19,682.19
XS Rating Curve= 0 ,0
Exp/Cntr=0.3,0.1

Type RM Length L Ch R = 1 ,2866.315,192.19,200,207.81
XS GIS Cut Line= 4
    1080480.4185    1571356.0345    1080998.9119    1571452.4209
    1081074.7051    1571789.2748    1081372.5527    1572002.1389
#Sta/Elev= 30
       0    75.5  155.77    75.5  263.17      76  314.66      76  394.08    76.5
  509.81      77  540.56      77  597.49    76.5   628.7      76  636.94      76
  642.91   75.78  650.75    75.5  670.45    73.5  693.83    73.5  702.91   74.75
  711.22      76  721.63    76.5  737.08    76.5  798.69      76   880.5    75.5
  895.95   74.64   915.7   74.17   927.3    73.5  936.17    73.5  940.58      74
  947.45      75  952.29    75.5 1070.23    75.5 1101.31   75.63 1238.74   75.79
#Mann= 3 ,0,0
       0    .035       0  642.91    .018       0  702.91    .035       0
Bank Sta=642.91,702.91
XS Rating Curve= 0 ,0
Exp/Cntr=0.3,0.1

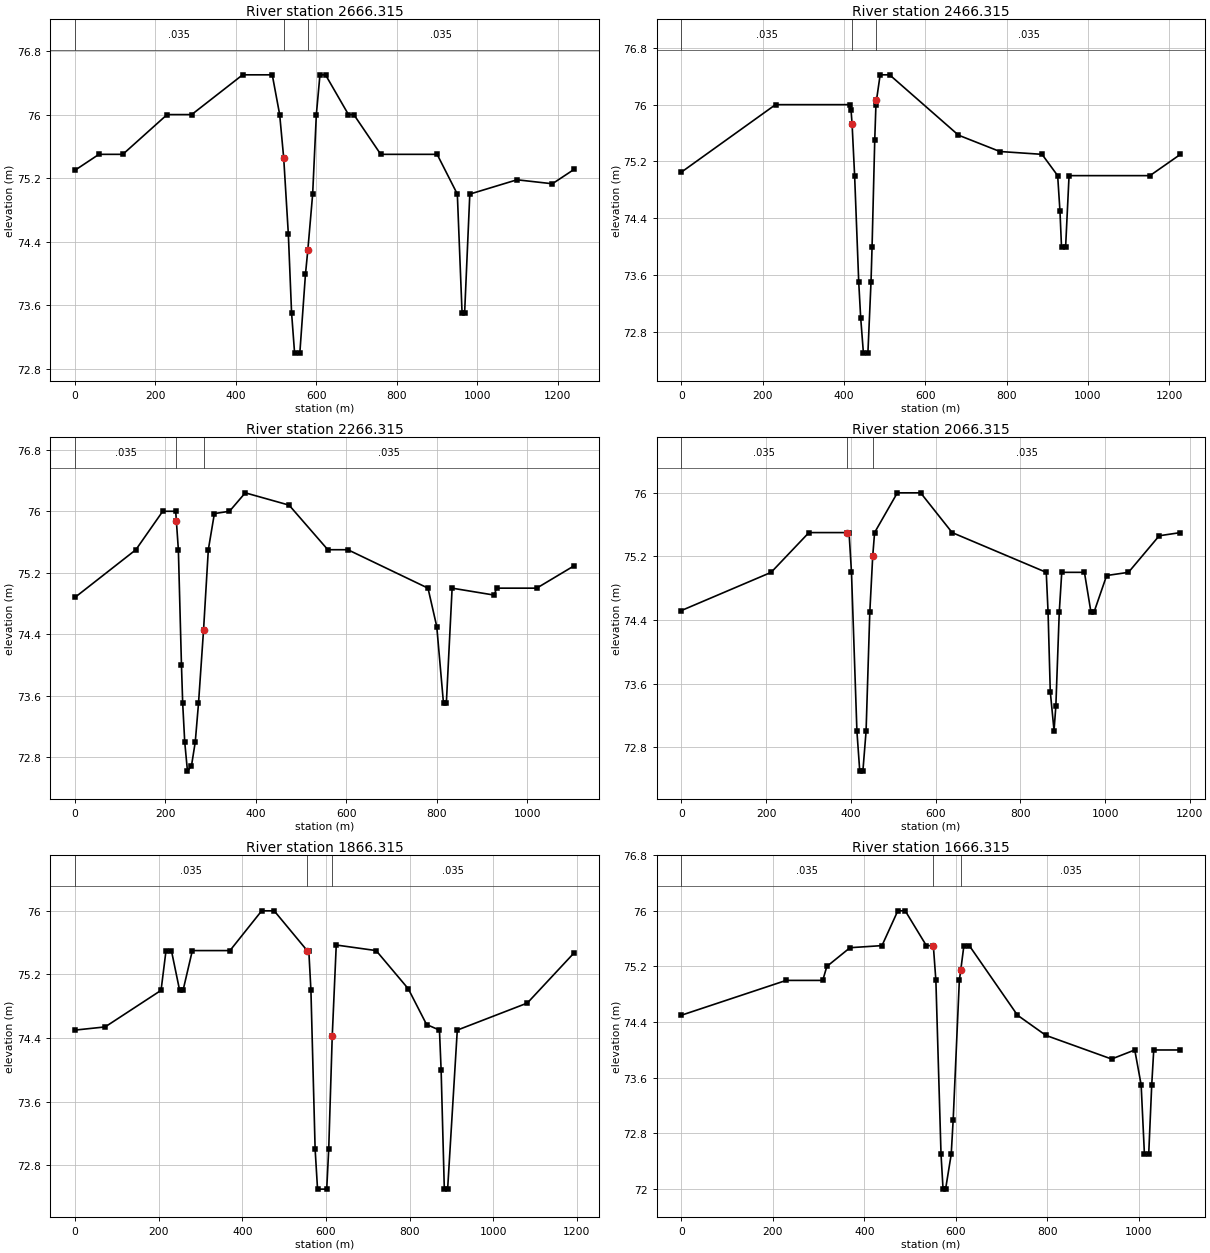
Type RM Length L Ch R = 1 ,2666.315,198.69,200,201.31
XS GIS Cut Line= 4
    1080413.8089    1571417.1216    1080837.3071    1571491.9031
     1080825.417    1571801.0496    1081227.9039    1572100.2957
#Sta/Elev= 30
       0    75.3   59.54    75.5  118.93    75.5  229.11      76  290.18      76
  416.93    76.5  490.59    76.5  509.01      76   519.1   75.45  530.54    74.5
  538.59   73.51  546.13      73  559.12      73  573.11   73.99   579.1    74.3
  591.04      75  600.21      76  609.19    76.5  623.05    76.5  680.09      76
   693.4      76  760.36    75.5  900.59    75.5  950.83      75  962.64    73.5
  968.92    73.5  981.86      75 1099.24   75.18 1187.19   75.13 1240.97   75.31
#Mann= 3 ,0,0
       0    .035       0   519.1    .018       0   579.1    .035       0
Bank Sta=519.1,579.1
XS Rating Curve= 0 ,0
Exp/Cntr=0.3,0.1

Type RM Length L Ch R = 1 ,2466.315,249.51,200,150.31
XS GIS Cut Line= 4
    1080356.2232    1571464.6942    1080655.8705    1571508.8005
    1080636.4999    1571737.3738    1081190.6132    1572157.6623
#Sta/Elev= 27
       0   75.05  231.45      76  414.03      76  417.14   75.93  419.77   75.73
  426.04      75  436.16    73.5  440.94      73  447.68    72.5   458.7    72.5
  466.35    73.5  468.97      74  475.54    75.5  478.49      76  479.77   76.06
  488.87   76.42  512.11   76.42  681.57   75.57  783.39   75.34  887.13    75.3
   925.6      75  931.26    74.5  935.05      74   945.2      74  953.65      75
 1152.64      75 1227.74    75.3
#Mann= 3 ,0,0
       0    .035       0  419.77    .018       0  479.77    .035       0
Bank Sta=419.77,479.77
XS Rating Curve= 0 ,0
Exp/Cntr=0.3,0.1

Type RM Length L Ch R = 1 ,2266.315,208.24,200,191.76
XS GIS Cut Line= 4
    1080212.2983    1571692.6391    1080255.2301    1571702.1731
    1080547.5626    1571712.6135     1081148.028    1572190.0326
#Sta/Elev= 30
       0   74.88  134.68    75.5  194.08      76  222.74      76  224.25   75.87
  228.63    75.5  235.47      74  238.21    73.5  242.68      73  248.74   72.62
  257.67   72.69     266      73  273.15    73.5  284.25   74.45  294.88    75.5
  308.28   75.97  341.67      76  376.61   76.24  473.47   76.08  559.15    75.5
  603.46    75.5  780.73      75  800.12    74.5  815.02    73.5  821.27    73.5
  834.08      75  926.94   74.91  932.61      75 1021.16      75 1103.63   75.29
#Mann= 3 ,0,0
       0    .035       0  224.25    .018       0  284.25    .035       0
Bank Sta=224.25,284.25
XS Rating Curve= 0 ,0
Exp/Cntr=0.3,0.1

Type RM Length L Ch R = 1 ,2066.315,211.93,200,188.07
XS GIS Cut Line= 4
    1080078.1307    1571881.4182    1080317.4153     1571947.621
    1080645.3778    1571866.6952    1081111.3766    1572231.5927
#Sta/Elev= 30
       0   74.52   211.7      75  300.93    75.5  391.45    75.5  395.62    75.5
  401.35      75   414.2      73  420.87    72.5  428.26    72.5  435.78      73
  444.61    74.5  451.45    75.2   455.9    75.5  509.59      76  564.57      76
  638.95    75.5  861.11      75  865.39    74.5  870.63    73.5  879.49   73.01
   883.8   73.32  891.84    74.5   897.7      75  951.24      75  966.65    74.5
  973.92    74.5  1003.7   74.96 1055.17      75 1127.79   75.46 1177.94    75.5
#Mann= 3 ,0,0
       0    .035       0  391.45    .018       0  451.45    .035       0
Bank Sta=391.45,451.45
XS Rating Curve= 0 ,0
Exp/Cntr=0.3,0.1

Type RM Length L Ch R = 1 ,1866.315,158.12,200,241.88
XS GIS Cut Line= 4
    1080035.6115    1571945.0255    1080541.2594    1572105.8958
    1080680.2679    1572002.6317    1081065.8008    1572304.3412
#Sta/Elev= 30
       0    74.5   72.07   74.54  205.82      75  217.69    75.5   230.6    75.5
  250.24      75  258.43      75  280.63    75.5  370.62    75.5  446.42      76
  476.36      76  555.16    75.5  559.14    75.5  564.22      75  574.28      73
  580.04    72.5  601.97    72.5  606.75      73  615.16   74.42  624.78   75.57
  720.12    75.5  796.96   75.02  840.82   74.57  871.58    74.5  875.56      74
  883.22    72.5  891.13    72.5  914.23    74.5 1081.66   74.84 1193.34   75.47
#Mann= 3 ,0,0
       0    .035       0  555.16    .018       0  615.16    .035       0
Bank Sta=555.16,615.16
XS Rating Curve= 0 ,0
Exp/Cntr=0.3,0.1

Type RM Length L Ch R = 1 ,1666.315,177.66,200,222.34
XS GIS Cut Line= 4
    1079970.6561    1571994.2082    1080329.7154    1572077.9904
    1080643.9976    1572369.1636    1080877.7629    1572548.1553
#Sta/Elev= 30
       0    74.5  229.07      75  309.06      75  317.96    75.2   368.7   75.47
  438.64    75.5  473.27      76  489.48      76  535.71    75.5  550.97    75.5
  556.53      75   567.8    72.5  572.23      72  577.77      72  590.06    72.5
   594.4      73  607.86      75  610.97   75.15  617.83    75.5  629.63    75.5
  735.03    74.5  797.14   74.21  940.89   73.87  991.57      74 1005.53    73.5
 1012.74    72.5 1022.07    72.5 1028.71    73.5  1033.1      74 1091.56      74
#Mann= 3 ,0,0
       0    .035       0  550.97    .018       0  610.97    .035       0
Bank Sta=550.97,610.97
XS Rating Curve= 0 ,0
Exp/Cntr=0.3,0.1

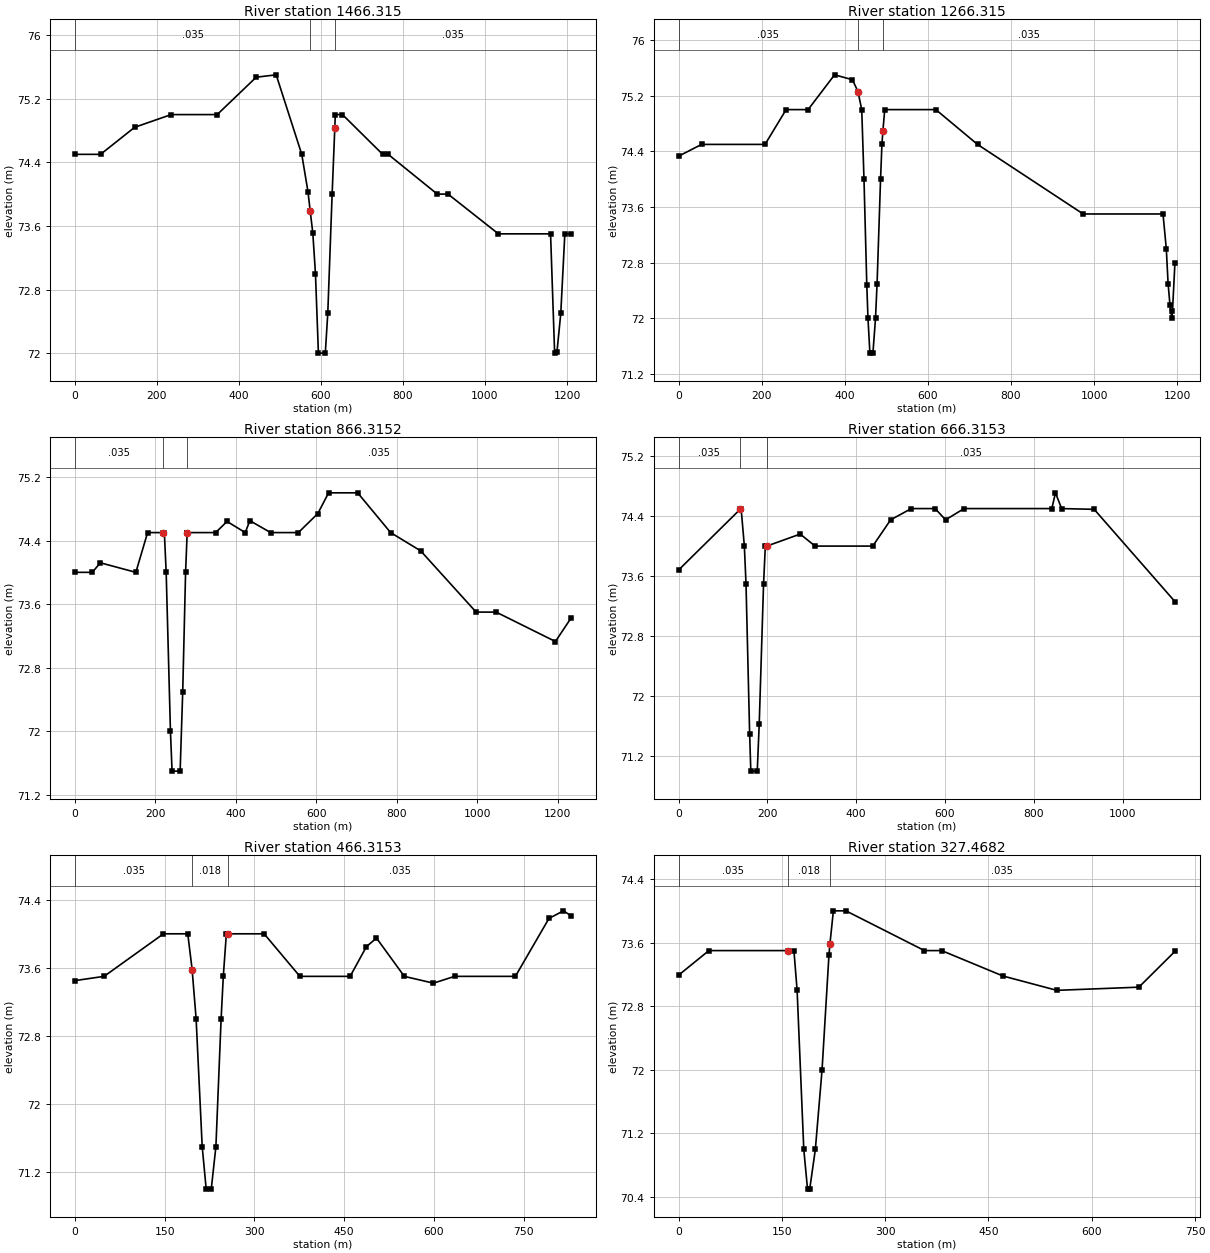
Type RM Length L Ch R = 1 ,1466.315,215.04,200,184.95
XS GIS Cut Line= 4
    1079900.4549     1572041.573    1080314.2202    1572157.3594
    1080340.1248     1572473.396    1080710.0367    1572753.1583
#Sta/Elev= 30
       0    74.5   62.68    74.5  145.72   74.84   234.9      75  347.09      75
  442.19   75.47   490.9    75.5  553.27    74.5  568.45   74.03  573.79   73.79
  580.24   73.51  586.69      73  593.86      72  610.69      72  616.73    72.5
  627.34      74  633.83   74.83  635.08      75  652.52      75  750.56    74.5
  763.97    74.5  883.71      74  909.99      74 1032.79    73.5 1159.98    73.5
  1169.9      72 1175.51   72.01 1184.89    72.5 1194.77    73.5 1210.55    73.5
#Mann= 3 ,0,0
       0    .035       0  573.79    .018       0  633.83    .035       0
Bank Sta=573.79,633.83
XS Rating Curve= 0 ,0
Exp/Cntr=0.3,0.1

Type RM Length L Ch R = 1 ,1266.315,410.51,400,389.53
XS GIS Cut Line= 4
    1079784.3397     1572071.356    1080040.1108    1572163.4889
    1080243.6466    1572472.3018    1080683.0551    1572807.7735
#Sta/Elev= 30
       0   74.33   55.54    74.5   208.2    74.5  258.96      75  311.83      75
  375.49    75.5  418.48   75.43   431.8   75.26  440.92      75  446.31      74
  453.08   72.48  455.92      72  460.55    71.5  467.82    71.5  474.04      72
  477.82    72.5  486.19      74  489.47    74.5   491.8   74.69  496.21      75
   619.2      75  719.46    74.5  973.75    73.5 1165.84    73.5 1173.76      73
 1178.08    72.5 1182.58   72.19  1187.1      72 1188.63    72.1 1194.54    72.8
#Mann= 3 ,0,0
       0    .035       0   431.8    .018       0   491.8    .035       0
Bank Sta=431.8,491.8
XS Rating Curve= 0 ,0
Exp/Cntr=0.3,0.1

Type RM Length L Ch R = 1 ,866.3152,209.16,200,190.8
XS GIS Cut Line= 3
    1079643.4541    1572112.7012    1080005.4348    1572386.9289
    1080630.2867    1572854.0753
#Sta/Elev= 30
       0      74   43.11      74   63.48   74.12  151.63      74  180.83    74.5
  219.59    74.5  222.51    74.5  227.04      74  237.66      72  241.66    71.5
  261.73    71.5  268.17    72.5  275.29      74  279.23    74.5     280    74.5
  350.02    74.5  378.36   74.64  423.61    74.5  435.04   74.65  486.71    74.5
  555.69    74.5  604.18   74.74  630.84      75  703.11      75  785.12    74.5
  859.83   74.27  997.67    73.5 1047.47    73.5 1194.82   73.13  1234.3   73.43
#Mann= 3 ,0,0
       0    .035       0  219.59    .018       0     280    .035       0
Bank Sta=219.59,280
XS Rating Curve= 0 ,0
Exp/Cntr=0.3,0.1

Type RM Length L Ch R = 1 ,666.3153,201.09,200,198.91
XS GIS Cut Line= 3
     1079545.912    1572344.5175     1079874.612    1572461.9099
    1080500.4923    1572908.3154
#Sta/Elev= 25
       0   73.68  138.79   74.49  141.01    74.5  148.27      74  151.99    73.5
  160.17    71.5  162.81      71  177.32      71  181.77   71.63  191.54    73.5
  195.51      74  198.79      74  273.97   74.16  307.62      74   437.4      74
  477.62   74.35  524.23    74.5   577.9    74.5  601.32   74.35  642.99    74.5
  840.62    74.5  848.79   74.71  862.69    74.5  935.95   74.49  1117.8   73.26
#Mann= 3 ,0,0
       0    .035       0  138.79    .018       0  198.79    .035       0
Bank Sta=138.79,198.79
XS Rating Curve= 0 ,0
Exp/Cntr=0.3,0.1

Type RM Length L Ch R = 1 ,466.3153,133.35,138.85,144.35
XS GIS Cut Line= 3
    1079485.0302    1572529.6118     1079885.609      1572655.92
    1080224.8188    1572885.3892
#Sta/Elev= 26
       0   73.45   48.82    73.5  148.09      74  188.66      74  195.95   73.58
  202.63      73  212.77    71.5  219.46      71  227.92      71  235.69    71.5
  244.38      73  248.04    73.5  253.15      74  255.95      74  316.28      74
  376.01    73.5  459.96    73.5   487.3   73.85  504.04   73.95  550.53    73.5
  599.18   73.42  634.57    73.5  736.13    73.5  792.18   74.18  816.37   74.27
  829.56   74.21
#Mann= 3 ,0,0
       0    .035       0  195.95    .018       0  255.95    .035       0
Bank Sta=195.95,255.95
XS Rating Curve= 0 ,0
Exp/Cntr=0.3,0.1

Type RM Length L Ch R = 1 ,327.4682,124.13,327.54,124.31
XS GIS Cut Line= 3
    1079445.6949    1572613.6877    1079779.4184    1572790.7109
    1080103.7223    1572902.2829
#Sta/Elev= 20
       0   73.19   44.14    73.5  158.42    73.5  167.56    73.5   172.2      73
  181.88      71  187.32    70.5  190.49    70.5  198.68      71   208.4      72
  218.41   73.44   219.8   73.58  224.86      74  243.01      74  357.09    73.5
     382    73.5  471.16   73.18  549.23      73  668.41   73.04  720.73   73.49
#Mann= 3 ,0,0
       0    .035       0  158.42    .018       0   219.8    .035       0
Bank Sta=158.42,219.8
XS Rating Curve= 0 ,0
Exp/Cntr=0.3,0.1

River Reach=ARROYOELZORRO   ,ABAJOLAT1
Reach XY= 30
1079526.957286981573013.08491518    1079327.7203    1573037.6709
    1078910.1353    1572733.9715    1078253.1058    1572618.3051
    1078094.2524    1572733.3828     1077901.525    1572656.1992
    1077773.5463    1572795.8368    1077590.4555    1572744.3908
    1077195.6486    1573072.3463    1076992.2968    1573064.6889
    1076912.2578    1573236.1591    1076722.9953    1573202.6476
    1076612.4146    1573358.3916    1076411.5354    1573301.7432
     1076266.837    1573437.2883    1076101.9001    1573337.8544
    1075934.8719    1573443.2967    1075776.3981    1573325.9612
    1075314.2113    1573352.5123    1075021.8357    1573164.1616
    1074762.1036    1573307.0204    1074809.0672    1573474.3696
     1074606.396     1573339.961    1074520.4062    1573461.8019
    1074456.1675    1573323.7608    1074343.8516    1573398.9026
    1074180.2065    1573289.1003     1074305.487    1573190.8074
    1074104.9324     1572975.833    1073782.6483    1573130.3062

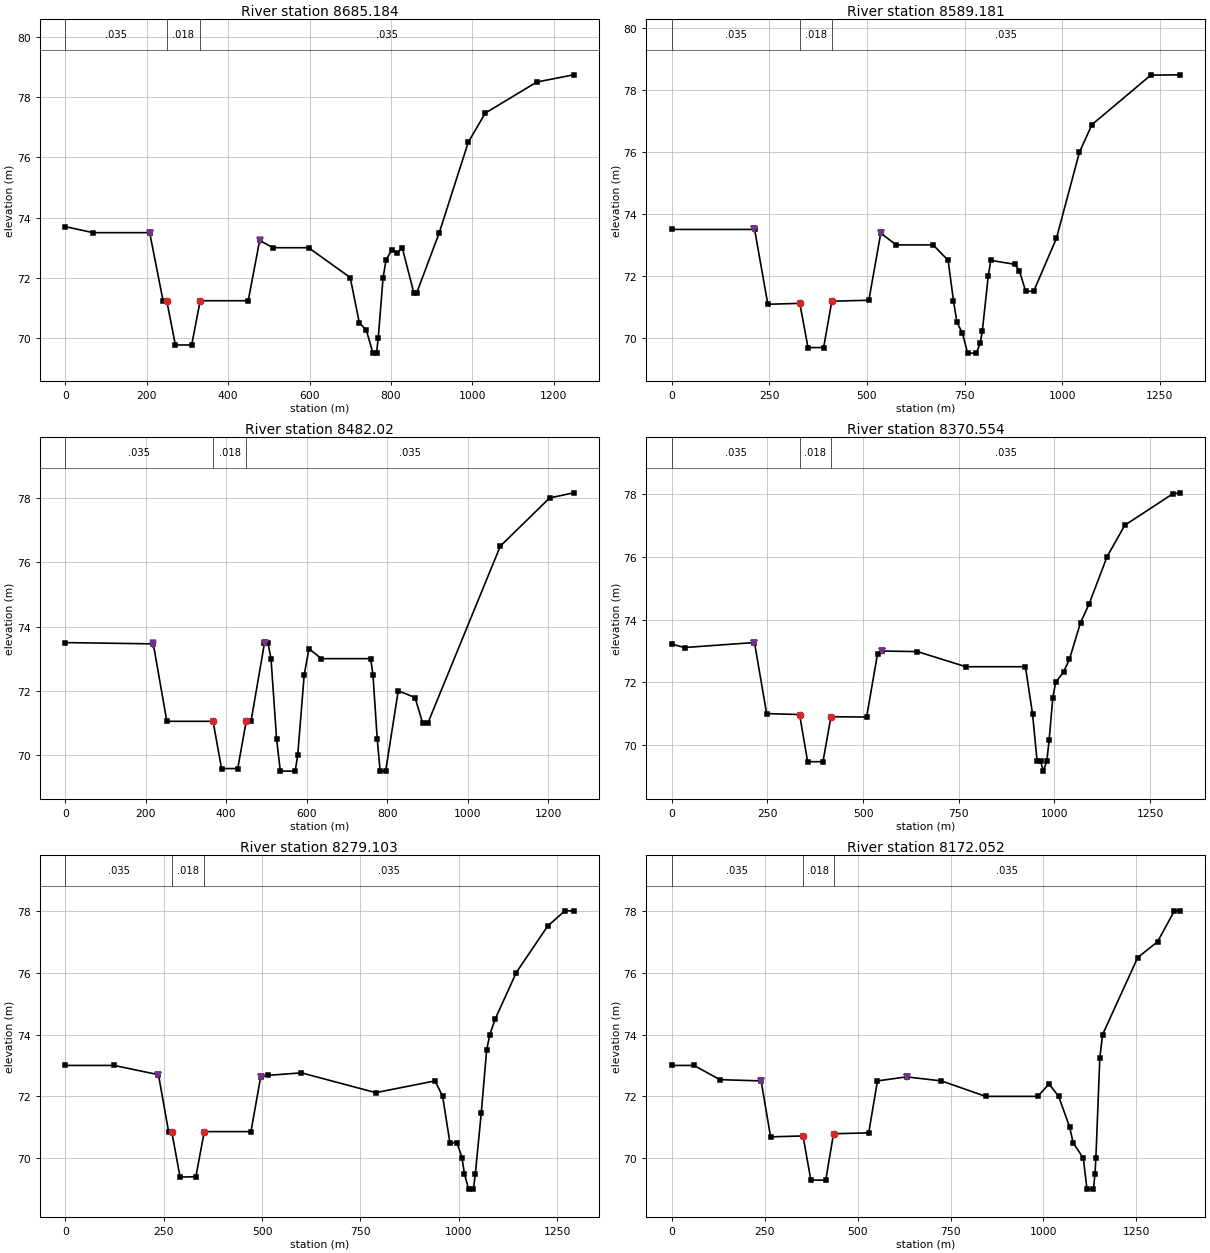
Type RM Length L Ch R = 1 ,8685.184,132.08,96,60.24
XS GIS Cut Line= 5
    1079689.4749    1572775.0158    1079573.3755    1572915.1394
    1079527.1627    1573013.1873     1079441.341    1573198.8588
    1079203.8048    1573913.9964
#Sta/Elev= 30
       0    73.7   68.38    73.5  207.45    73.5  240.31   71.24  249.34   71.24
  270.65   69.77  310.66   69.77  331.47   71.24  449.51   71.24  477.54   73.24
   510.5      73  597.78      73  699.99   72.01  722.46    70.5  739.33   70.27
  755.91    69.5  764.56    69.5  768.83      70  780.68      72  788.11    72.6
  802.42   72.93  815.94   72.83  827.78      73  856.22    71.5  863.31    71.5
  918.75    73.5  989.86    76.5 1031.74   77.47 1158.17    78.5 1248.47   78.74
#Mann= 3 ,0,0
       0    .035       0  249.34    .018       0  331.47    .035       0
Levee=-1,207.6,73.5,-1,477.97,73.24,	341,	340
Bank Sta=249.34,331.47
XS Rating Curve= 0 ,0
Exp/Cntr=0.3,0.1

Type RM Length L Ch R = 1 ,8589.181,71.26,107.16,143.04
XS GIS Cut Line= 5
    1079531.8761    1572688.6196    1079402.7592    1572950.0285
    1079453.2203    1573057.3448    1079460.9676    1573080.2037
    1079160.4004    1573894.0637
#Sta/Elev= 30
       0    73.5  212.39    73.5  246.26   71.08  328.15   71.11  349.15   69.68
  389.15   69.68  410.15   71.18  504.98   71.21  535.47   73.38  575.11      73
  669.62      73  708.06    72.5  721.73   71.19  730.62    70.5  744.79   70.14
  757.94    69.5  780.38    69.5  790.23   69.83  795.63   70.22  810.78   71.99
  817.23    72.5  879.82   72.37   890.5   72.16  906.69    71.5  927.06    71.5
  985.34   73.21 1044.39      76 1076.42   76.89 1227.07   78.49 1301.87    78.5
#Mann= 3 ,0,0
       0    .035       0  328.15    .018       0  410.15    .035       0
Levee=-1,211.38,73.5,-1,535.71,73.38,	341,	340
Bank Sta=328.15,410.15
XS Rating Curve= 0 ,0
Exp/Cntr=0.3,0.1

Type RM Length L Ch R = 1 ,8482.02 ,74.63,111.47,148.33
XS GIS Cut Line= 4
    1079486.3677    1572661.6321    1079419.3723    1572857.7406
    1079292.7963    1573129.7306    1079063.1393    1573850.2486
#Sta/Elev= 30
       0    73.5  218.95   73.46  252.64   71.05  367.49   71.05  388.54   69.58
  428.82   69.58  449.82   71.05  461.84   71.05  495.23   73.48  503.71    73.5
  511.53      73  525.43    70.5  534.64    69.5  571.54    69.5  577.94      70
  594.06    72.5   605.9   73.31  636.65      73  759.24      73  764.93    72.5
  775.55    70.5  782.78    69.5  796.46    69.5  827.74      72  869.52   71.79
  888.29      71  901.54      71 1081.42    76.5 1203.96      78 1263.47   78.16
#Mann= 3 ,0,0
       0    .035       0  367.49    .018       0  449.82    .035       0
Levee=-1,219.27,73.5,-1,495.44,73.49,	341,	340
Bank Sta=367.49,449.82
XS Rating Curve= 0 ,0
Exp/Cntr=0.3,0.1

Type RM Length L Ch R = 1 ,8370.554,128.33,91.45,54.52
XS GIS Cut Line= 6
    1079448.3734    1572649.6729    1079387.8709    1572843.0808
    1079344.2332    1572935.8468    1079236.2393    1572961.8225
     1079212.153    1572968.0202    1078982.7058    1573824.8486
#Sta/Elev= 30
       0   73.22   33.56   73.11  216.39   73.27  248.05   71.01  334.24   70.98
  355.24   69.48  395.24   69.48  416.24   70.91  509.33    70.9  537.96   72.92
  548.92      73  642.28   72.98  768.63    72.5  924.21    72.5  942.88      71
  954.78    69.5  963.72    69.5   971.2   69.18  980.22    69.5  986.24   70.17
  995.65    71.5 1003.15      72 1024.17   72.34 1039.11   72.73 1068.18    73.9
 1090.81    74.5 1137.54      76 1183.97      77 1309.43      78 1328.13   78.03
#Mann= 3 ,0,0
       0    .035       0  334.24    .018       0  416.24    .035       0
Levee=-1,216.11,73.27,-1,549.07,73.01,	341,	340
Bank Sta=334.24,416.24
XS Rating Curve= 0 ,0
Exp/Cntr=0.3,0.1

Type RM Length L Ch R = 1 ,8279.103,143.28,107.05,70.86
XS GIS Cut Line= 4
    1079359.4733    1572590.4061    1079272.7216    1572789.4938
    1079146.1456    1573061.4837    1078894.6523    1573793.5218
#Sta/Elev= 30
       0      73  124.03      73  236.91    72.7  262.57   70.86  270.55   70.86
  291.77   69.39  331.85    69.4  353.22   70.86  471.77   70.86  496.41   72.62
  515.77   72.68  600.11   72.76  788.72   72.12  939.38    72.5  958.72      72
  977.18    70.5  995.44    70.5 1008.04      70 1014.04    69.5  1024.6      69
 1036.88      69 1041.74   69.49 1056.77   71.46 1070.54    73.5 1078.59      74
 1092.19    74.5  1145.6      76 1225.16    77.5 1269.15      78  1291.2      78
#Mann= 3 ,0,0
       0    .035       0  270.55    .018       0  353.22    .035       0
Levee=-1,236.62,72.7,-1,496.9,72.62,	341,	340
Bank Sta=270.55,353.22
XS Rating Curve= 0 ,0
Exp/Cntr=0.3,0.1

Type RM Length L Ch R = 1 ,8172.052,72.42,108.66,144.91
XS GIS Cut Line= 6
    1079236.8122    1572529.6153    1079140.6199    1572728.0176
    1079096.0536    1572807.9575    1079149.5197     1572919.071
     1079160.612    1572940.2495    1078827.2364    1573784.8012
#Sta/Elev= 30
       0      73   60.19      73  129.66   72.54  240.63    72.5  266.01   70.69
  353.32   70.72  374.32   69.29  414.32   69.29  435.32   70.79  529.97   70.82
  553.46    72.5   631.7   72.63  725.27    72.5  844.52      72  984.55      72
 1014.89    72.4 1040.75      72 1070.66      71 1079.68    70.5 1107.13      70
 1116.99      69 1134.46      69  1138.6    69.5 1140.93      70  1151.6   73.25
 1159.01      74 1253.53   76.49 1306.77      77 1352.23      78  1367.2      78
#Mann= 3 ,0,0
       0    .035       0  353.32    .018       0  435.32    .035       0
Levee=-1,239.77,72.51,-1,631.77,72.63,	341,	340
Bank Sta=353.32,435.32
XS Rating Curve= 0 ,0
Exp/Cntr=0.3,0.1

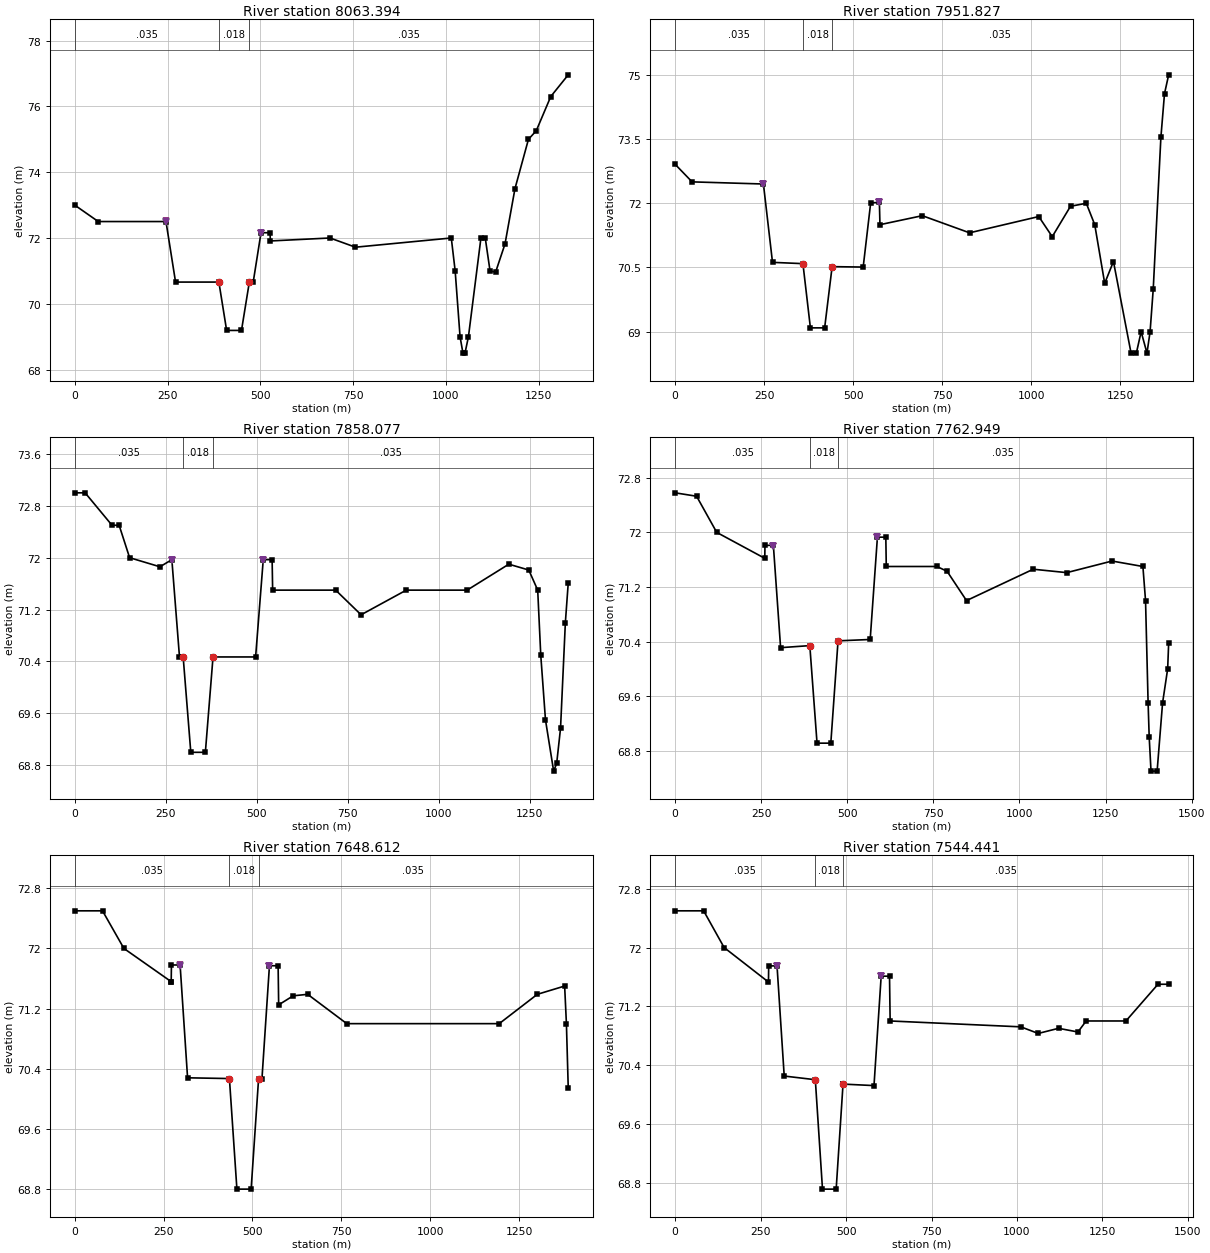
Type RM Length L Ch R = 1 ,8063.394,75.89,111.57,147.24
XS GIS Cut Line= 4
    1079207.1788    1572509.5069    1079114.7195    1572715.9643
    1078988.1435    1572987.9543    1078734.1028    1573749.8761
#Sta/Elev= 30
       0      73   63.41    72.5  245.85    72.5  271.62   70.66  388.31   70.66
  409.19   69.19  449.23   69.19  470.35   70.66  480.82   70.66  501.82   72.16
  526.22   72.16  526.96   71.91  687.74      72  756.24   71.72 1014.35      72
 1024.78      71 1037.96      69 1045.76    68.5 1051.26    68.5 1060.57      69
 1094.21      72 1105.86      72 1118.71      71  1133.7   70.96 1159.07   71.82
  1185.9    73.5  1222.2      75 1243.25   75.26 1282.31    76.3 1329.37   76.96
#Mann= 3 ,0,0
       0    .035       0  388.31    .018       0  470.35    .035       0
Levee=-1,246.08,72.51,-1,501.81,72.15994,	341,	340
Bank Sta=388.31,470.35
XS Rating Curve= 0 ,0
Exp/Cntr=0.3,0.1

Type RM Length L Ch R = 1 ,7951.827,132.49,93.75,55.01
XS GIS Cut Line= 6
    1079179.6621    1572494.6902    1079087.3428     1572703.224
    1079045.2535    1572789.9658    1078932.8887    1572820.4592
    1078914.0199    1572841.8243    1078634.6193     1573714.951
#Sta/Elev= 30
       0   72.91   47.57    72.5  247.93   72.45  273.46   70.62   358.9   70.59
   379.9   69.09   419.9   69.09   440.9   70.52  528.14   70.51   549.2   72.01
  573.68   72.02  575.23    71.5  694.23   71.71  826.92   71.31  1021.3   71.69
 1059.14   71.22 1110.43   71.93 1154.79      72 1178.52    71.5 1206.48   70.13
 1231.08   70.64 1280.53    68.5 1295.36    68.5 1308.85      69 1325.22    68.5
 1333.96      69 1342.84      70 1364.31   73.54 1374.45   74.56 1386.14      75
#Mann= 3 ,0,0
       0    .035       0   358.9    .018       0   440.9    .035       0
Levee=-1,247.66,72.45,-1,572.62,72.02,	341,	340
Bank Sta=358.9,440.9
XS Rating Curve= 0 ,0
Exp/Cntr=0.3,0.1

Type RM Length L Ch R = 1 ,7858.077,133.73,95.13,56.53
XS GIS Cut Line= 4
    1079064.8327    1572431.4018    1078954.4105    1572645.2909
    1078864.4802    1572883.4531     1078573.765     1573693.996
#Sta/Elev= 30
       0      73   28.62      73  102.49    72.5  122.09    72.5  150.87      72
  234.28   71.86  266.96   71.97  287.96   70.47  298.06   70.47  319.05      69
  359.06      69  380.13   70.47  497.16   70.47  518.16   71.97  542.56   71.97
  543.98    71.5  717.22    71.5  787.06   71.12  911.27    71.5 1078.53    71.5
 1193.12    71.9 1247.99   71.81 1272.48    71.5 1280.85    70.5 1293.84    69.5
 1316.32   68.71 1324.62   68.83 1335.22   69.37  1348.5      71 1356.39   71.61
#Mann= 3 ,0,0
       0    .035       0  298.06    .018       0  380.13    .035       0
Levee=-1,267.02,71.96504,-1,518.24,71.9697,	341,	340
Bank Sta=298.06,380.13
XS Rating Curve= 0 ,0
Exp/Cntr=0.3,0.1

Type RM Length L Ch R = 1 ,7762.949,78.48,114.34,150.19
XS GIS Cut Line= 6
    1078881.4231    1572348.1108    1078808.8085    1572598.7291
    1078784.9029    1572683.3915    1078852.9902    1572787.2213
    1078860.2564    1572814.6251    1078534.2891    1573687.5401
#Sta/Elev= 30
       0   72.58   62.27   72.53  120.78      72   260.3   71.62  260.85   71.81
  285.25   71.81  306.25   70.31  391.06   70.34  412.06   68.91  452.06   68.91
  473.06   70.41  566.41   70.43  587.41   71.93  611.82   71.93  613.12    71.5
  760.06    71.5  789.68   71.43  846.17      71 1039.93   71.46 1137.27   71.41
 1268.84   71.58 1358.38    71.5 1366.04      71 1373.51    69.5 1376.66      69
 1381.93    68.5 1399.68    68.5 1415.51    69.5 1430.31      70  1433.2   70.38
#Mann= 3 ,0,0
       0    .035       0  391.06    .018       0  473.06    .035       0
Levee=-1,285.33,71.8001,-1,587.45,71.9343,	341,	340
Bank Sta=391.06,473.06
XS Rating Curve= 0 ,0
Exp/Cntr=0.3,0.1

Type RM Length L Ch R = 1 ,7648.612,69.71,104.17,138.64
XS GIS Cut Line= 4
    1078856.8697    1572329.4841    1078785.7915    1572590.9508
    1078698.8347    1572878.1138    1078462.3223    1573660.4468
#Sta/Elev= 24
       0    72.5   78.19    72.5  138.34      72   270.9   71.56  271.41   71.56
  272.06   71.78  296.47   71.78  317.48   70.28  435.19   70.27  456.24    68.8
  496.27    68.8  517.26   70.27  526.77   70.27  547.78   71.77  572.19   71.77
  573.73   71.25  614.48   71.37  655.31   71.39   765.3      71 1194.14      71
 1301.33   71.39  1378.2    71.5 1383.16      71  1388.3   70.15
#Mann= 3 ,0,0
       0    .035       0  435.19    .018       0  517.26    .035       0
Levee=-1,296.55,71.77281,-1,547.83,71.77087,	341,	340
Bank Sta=435.19,517.26
XS Rating Curve= 0 ,0
Exp/Cntr=0.3,0.1

Type RM Length L Ch R = 1 ,7544.441,136.14,96.57,56.98
XS GIS Cut Line= 6
     1078809.668    1572315.7257    1078755.1603    1572583.9023
    1078732.1978    1572678.9464    1078622.8718     1572729.903
    1078603.9276    1572741.1766    1078396.2822    1573647.3234
#Sta/Elev= 24
       0    72.5   83.37    72.5  143.29      72  273.01   71.53  273.66   71.75
  298.06   71.75  319.07   70.25  410.06    70.2  431.06   68.71  471.06   68.71
  491.13   70.14  492.06   70.14  581.73   70.12   602.7   71.61  627.12   71.61
  628.96      71 1011.28   70.92 1062.13   70.83  1121.6    70.9 1178.29   70.85
  1202.4      71  1318.7      71 1412.49    71.5 1443.74    71.5
#Mann= 3 ,0,0
       0    .035       0  410.06    .018       0  492.06    .035       0
Levee=-1,298.06,71.74581,-1,602.76,71.61491,	341,	340
Bank Sta=410.06,492.06
XS Rating Curve= 0 ,0
Exp/Cntr=0.3,0.1

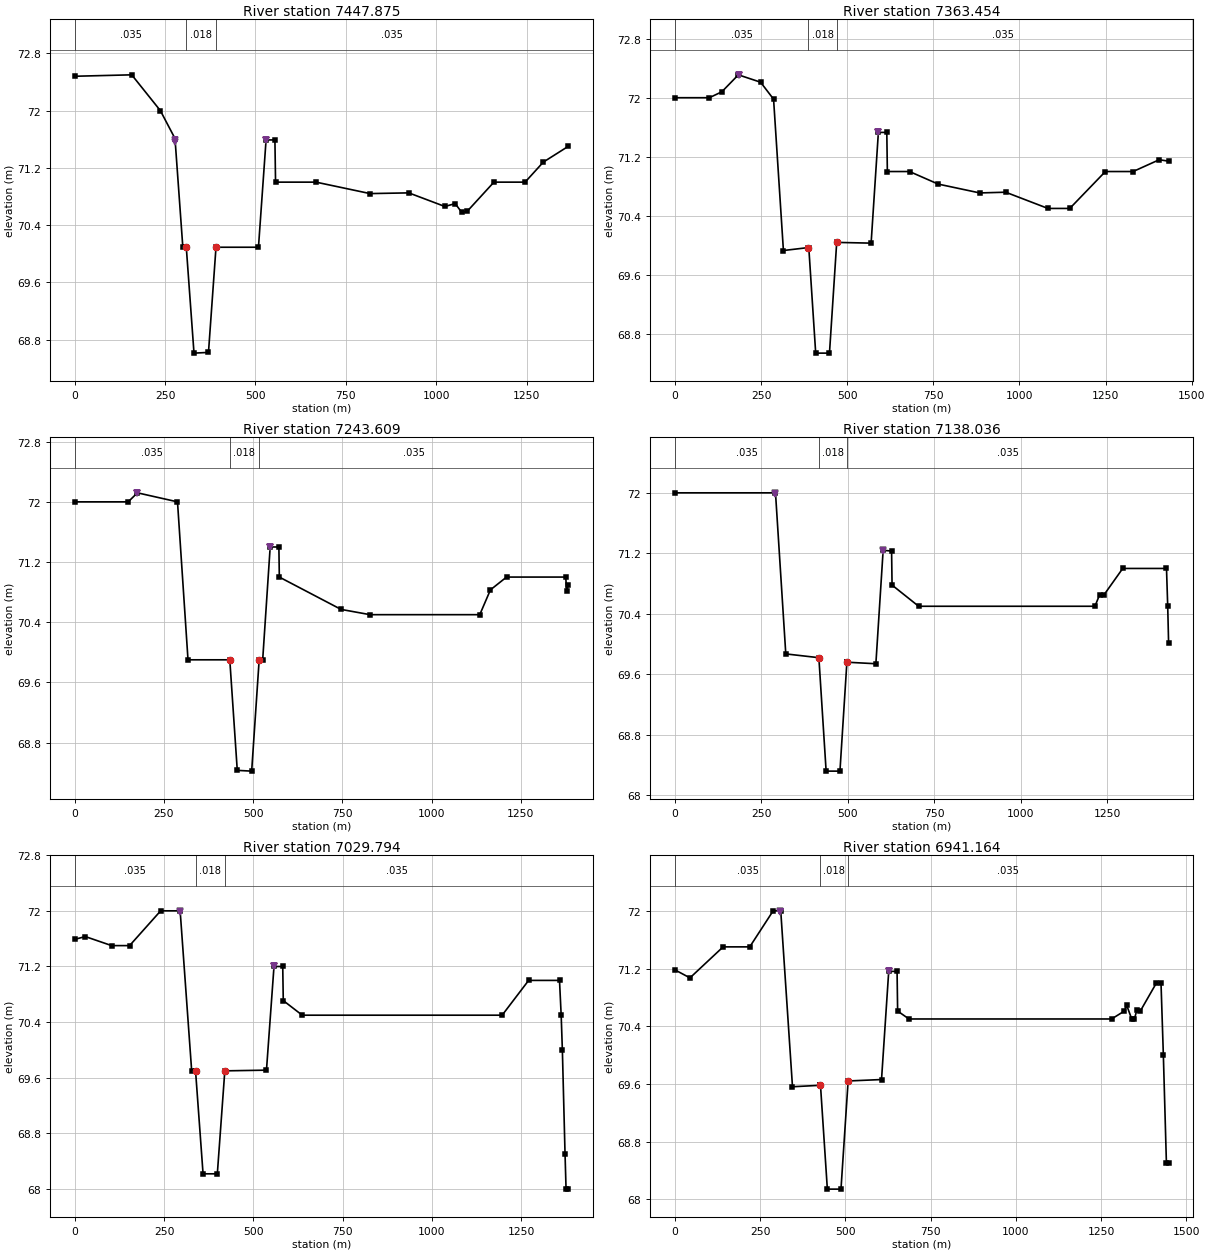
Type RM Length L Ch R = 1 ,7447.875,123.11,84.42,45.74
XS GIS Cut Line= 4
     1078660.612     1572303.449    1078611.3139    1572552.2751
    1078568.3847    1572803.1983    1078364.2781    1573635.2584
#Sta/Elev= 24
       0   72.48  157.71    72.5  236.85      72  277.37   71.61  299.04   70.09
  308.61   70.09  329.93   68.61  369.98   68.62  390.79   70.09  508.24   70.09
  529.28   71.59  553.73   71.59   555.5      71  667.43      71  816.89   70.84
  924.02   70.85 1023.66   70.66 1052.44    70.7 1070.11   70.58  1085.2   70.59
  1159.5      71 1245.72      71 1296.12   71.28 1364.96    71.5
#Mann= 3 ,0,0
       0    .035       0  308.61    .018       0  390.79    .035       0
Levee=-1,278.06,71.58557,-1,529.34,71.58852,	341,	340
Bank Sta=308.61,390.79
XS Rating Curve= 0 ,0
Exp/Cntr=0.3,0.1

Type RM Length L Ch R = 1 ,7363.454,84.95,119.85,154.72
XS GIS Cut Line= 5
     1078506.095     1572265.349    1078465.0065    1572577.1945
     1078464.185    1572614.5997    1078546.1793     1572698.458
    1078316.2297    1573634.4117
#Sta/Elev= 26
       0      72   99.46      72  135.64   72.08  183.66   72.31   248.2   72.21
  285.92   71.98  314.49   69.93  387.24   69.97  388.18   69.97  408.24   68.54
  448.24   68.54  469.24   70.04  569.16   70.03  590.24   71.53  614.73   71.53
  616.32      71  680.66      71  763.85   70.83   884.7   70.71   959.9   70.72
  1082.7    70.5 1146.02    70.5 1249.41      71 1329.96      71 1405.88   71.16
 1433.03   71.14
#Mann= 3 ,0,0
       0    .035       0  387.24    .018       0  469.24    .035       0
Levee=-1,184.79,72.31,-1,590.23,71.52976,	341,	340
Bank Sta=387.24,469.24
XS Rating Curve= 0 ,0
Exp/Cntr=0.3,0.1

Type RM Length L Ch R = 1 ,7243.609,70.34,105.57,140.83
XS GIS Cut Line= 4
     1078465.455    1572258.3639    1078431.9017    1572573.9409
    1078412.4907    1572827.8406    1078269.2396    1573625.5217
#Sta/Elev= 21
       0      72  149.71      72  175.69   72.12  287.93      72  317.36    69.9
  434.41    69.9  455.37   68.43   495.7   68.42  516.72    69.9  526.57    69.9
  547.57    71.4  571.97    71.4  573.18      71  746.15   70.57  827.44    70.5
 1134.69    70.5 1164.56   70.83  1209.7      71 1375.52      71 1378.08   70.81
 1382.44   70.89
#Mann= 3 ,0,0
       0    .035       0  434.41    .018       0  516.72    .035       0
Levee=-1,175.1,72.12,-1,547.59,71.4004,	341,	340
Bank Sta=434.41,516.72
XS Rating Curve= 0 ,0
Exp/Cntr=0.3,0.1

Type RM Length L Ch R = 1 ,7138.036,148.73,108.24,67.75
XS GIS Cut Line= 6
    1078440.6899    1572253.2839    1078410.0467     1572572.214
    1078402.5898    1572626.6647     1078303.739    1572699.4352
    1078288.2896    1572714.9299    1078224.1545    1573621.0767
#Sta/Elev= 20
       0      72  290.56      72  320.33   69.87  416.11   69.82  437.11   68.32
  477.11   68.32   497.2   69.76  498.11   69.76   581.1   69.74  602.14   71.24
  626.59   71.23  627.94   70.78  704.89    70.5 1215.23    70.5  1228.5   70.65
 1241.25   70.65 1295.63      71 1422.31      71 1425.83    70.5  1428.4   70.01
#Mann= 3 ,0,0
       0    .035       0  416.11    .018       0  498.11    .035       0
Levee=-1,290.25,71.99,-1,602.22,71.23524,	341,	340
Bank Sta=416.11,498.11
XS Rating Curve= 0 ,0
Exp/Cntr=0.3,0.1

Type RM Length L Ch R = 1 ,7029.794,125.27,88.63,51.99
XS GIS Cut Line= 4
    1078259.0796    1572239.3139    1078248.9277    1572576.7524
    1078259.1448    1572775.2182    1078191.1344    1573617.9017
#Sta/Elev= 24
       0   71.59   29.72   71.63  103.45    71.5  153.63    71.5  240.65      72
   295.2      72  327.46    69.7  338.32    69.7  359.36   68.22   399.3   68.22
  420.26    69.7   536.9   69.71  557.97    71.2  582.45    71.2  583.94   70.71
  637.02    70.5 1196.78    70.5 1270.95      71 1357.37      71 1362.04    70.5
 1365.39      70 1372.89    68.5 1375.74      68 1381.74      68
#Mann= 3 ,0,0
       0    .035       0  338.32    .018       0  420.26    .035       0
Levee=-1,294.2,71.99,-1,558.01,71.20392,	341,	340
Bank Sta=338.32,420.26
XS Rating Curve= 0 ,0
Exp/Cntr=0.3,0.1

Type RM Length L Ch R = 1 ,6941.164,78.58,113.31,148.04
XS GIS Cut Line= 6
    1078140.9693    1572227.8839    1078125.4875    1572526.2204
    1078118.7443    1572619.6797    1078212.2914    1572687.2832
    1078230.5045    1572701.5948    1078163.1944    1573616.6317
#Sta/Elev= 29
       0   71.18   43.56   71.07  140.93    71.5  219.06    71.5  287.77      72
  310.04      72  344.53   69.56  425.86   69.58  426.73   69.58  446.86   68.14
  486.86   68.14  507.86   69.64  605.87   69.66  626.97   71.16  651.49   71.16
  653.15   70.61  686.37    70.5 1281.23    70.5 1318.69   70.61 1325.47   70.69
 1340.26    70.5 1348.24    70.5 1355.67   70.63 1365.51   70.61 1412.81      71
 1426.23      71 1433.13      70 1442.11    68.5 1448.53    68.5
#Mann= 3 ,0,0
       0    .035       0  425.86    .018       0  507.86    .035       0
Levee=-1,309.18,71.99,-1,626.99,71.16149,	341,	340
Bank Sta=425.86,507.86
XS Rating Curve= 0 ,0
Exp/Cntr=0.3,0.1