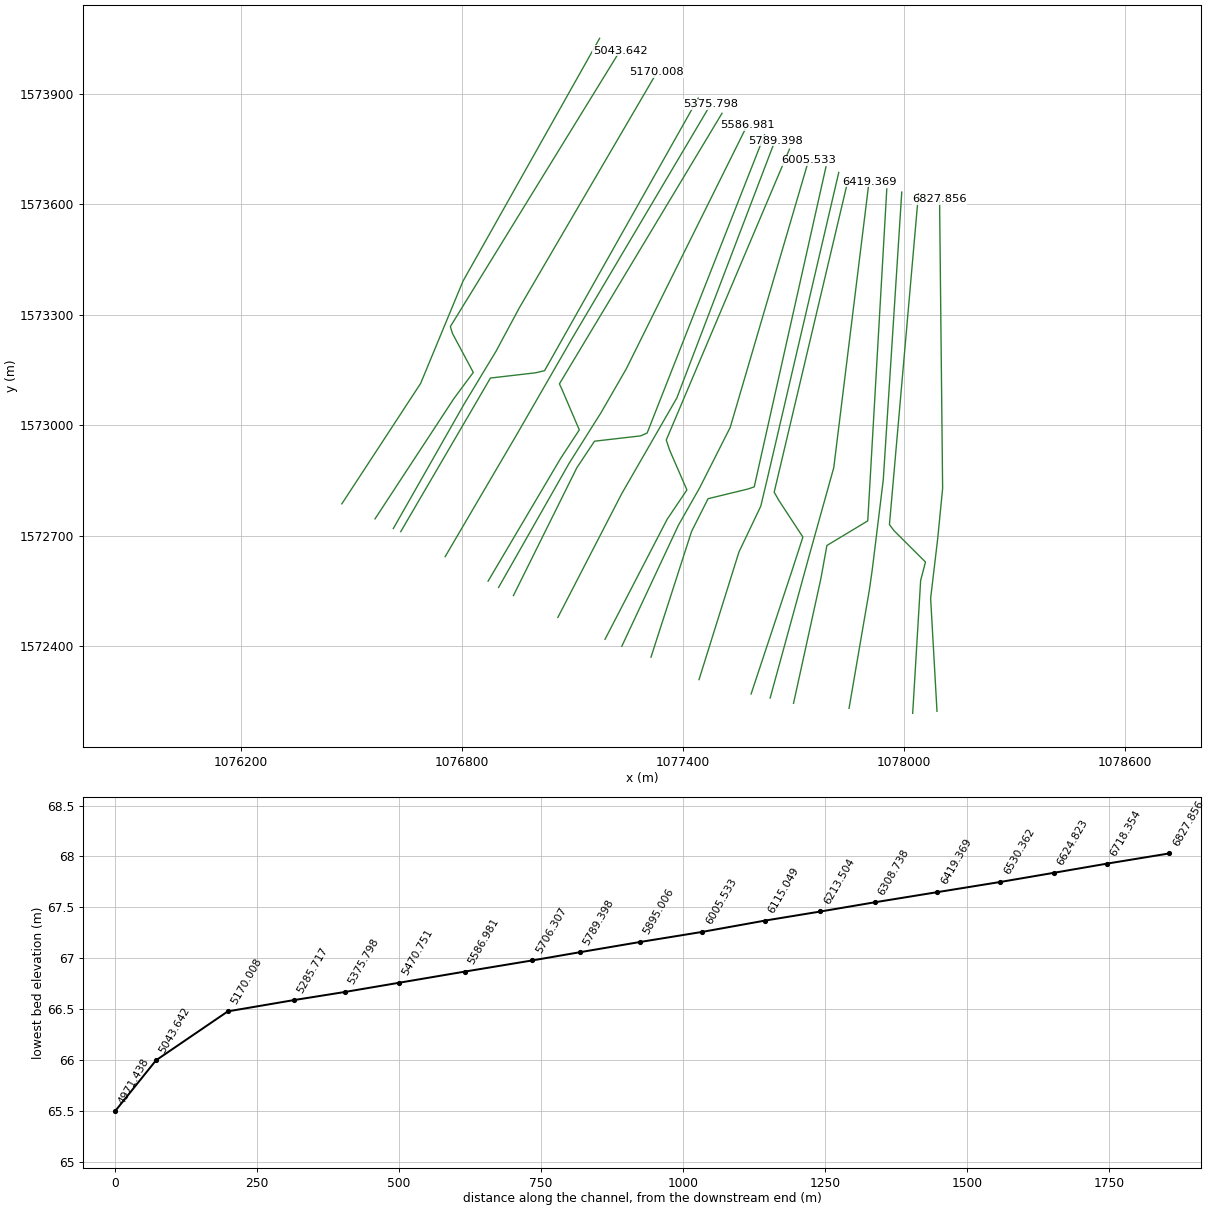
HEC-RAS study HECRAS_v1.prj: HECRAS_v1

--- HECRAS_v1.g01 (geometry) --- (continued)

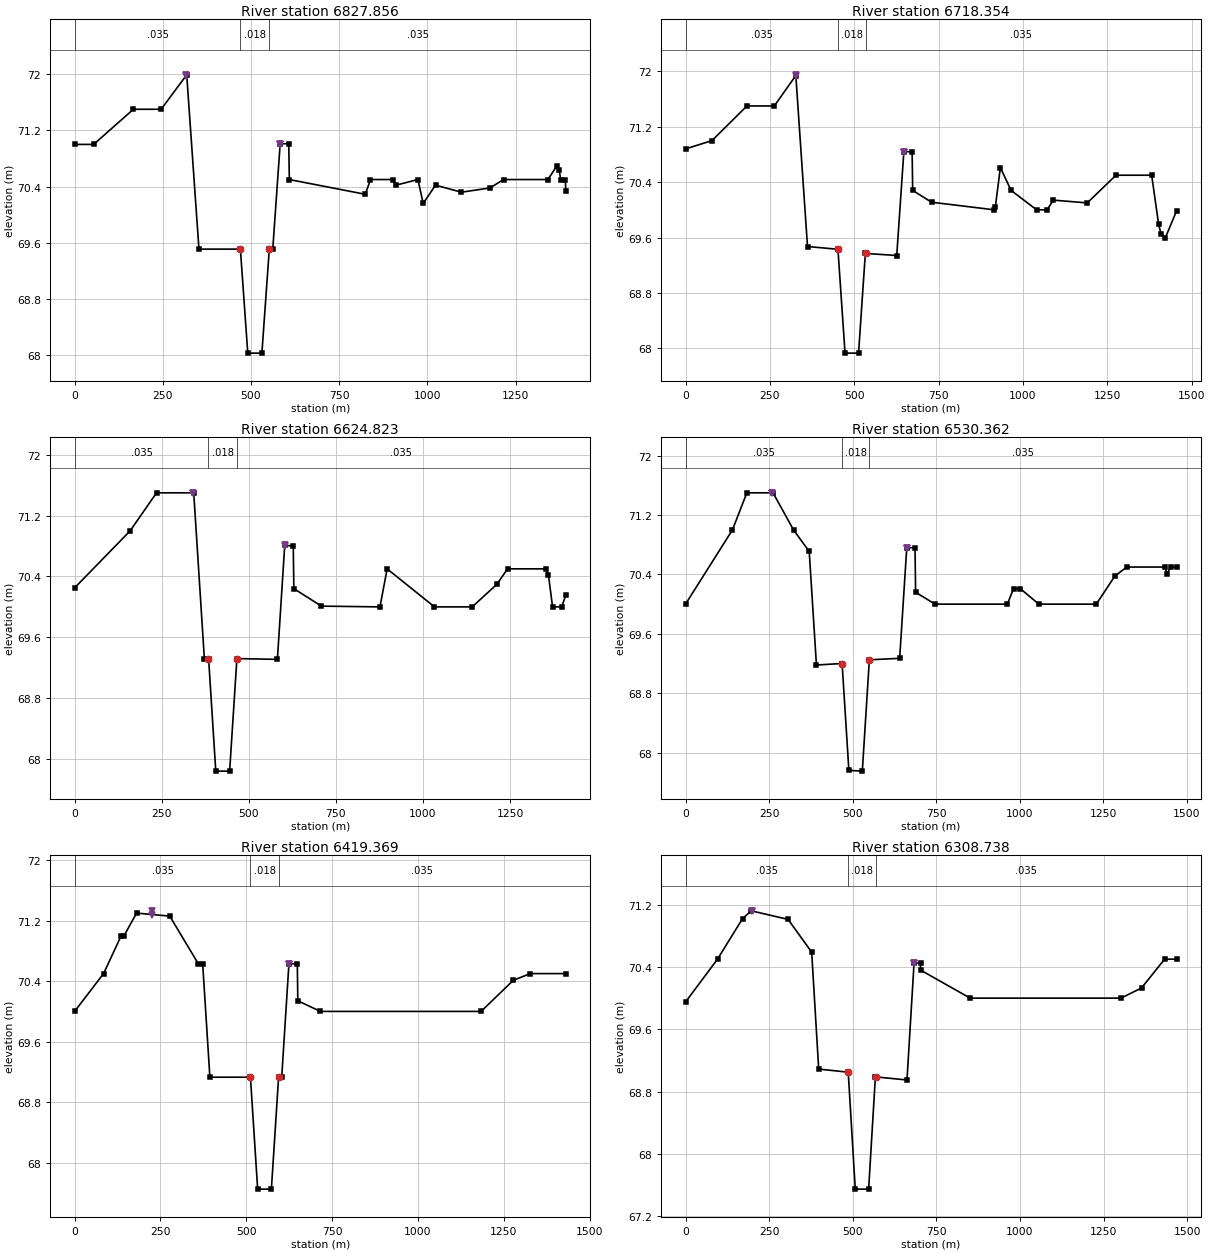
Type RM Length L Ch R = 1 ,6827.856,73.22,109.5,145.78
XS GIS Cut Line= 5
    1078089.5342    1572224.0739    1078072.2662    1572530.7353
    1078091.3989    1572692.3778    1078104.8158    1572829.0109
    1078096.5192    1573614.0916
#Sta/Elev= 30
       0      71   54.07      71  166.58    71.5  245.34    71.5  317.79   71.99
   352.5   69.51  469.92   69.51  490.89   68.03   530.9   68.03  551.91   69.51
  561.72   69.51  582.72   71.01  607.12   71.01  608.66    70.5  824.03   70.29
  838.62    70.5  903.45    70.5  911.13   70.42   973.2    70.5  988.04   70.16
 1023.09   70.42 1096.64   70.32 1177.09   70.38 1216.09    70.5 1341.61    70.5
 1366.45   70.69 1373.55   70.64 1377.74    70.5 1391.08    70.5 1392.33   70.34
#Mann= 3 ,0,0
       0    .035       0  469.92    .018       0  551.91    .035       0
Levee=-1,317.07,71.98,-1,582.81,71.0098,	341,	340
Bank Sta=469.92,551.91
XS Rating Curve= 0 ,0
Exp/Cntr=0.3,0.1

Type RM Length L Ch R = 1 ,6718.354,130.83,93.53,56.23
XS GIS Cut Line= 6
    1078023.5364    1572218.3589    1078045.1515    1572579.2561
    1078058.2498    1572629.2047    1077972.8051    1572714.3585
    1077960.4596    1572730.8049    1078039.1998    1573628.6967
#Sta/Elev= 30
       0   70.88   78.52      71  181.95    71.5  263.13    71.5   326.9   71.94
  361.54   69.47  451.75   69.43  472.77   67.93   512.8   67.93  532.96   69.37
  533.81   69.37     626   69.34  647.09   70.84  671.59   70.84  673.27   70.28
  729.28   70.11  914.95      70  918.16   70.04  933.12   70.61  964.93   70.28
 1040.61      70 1071.76      70 1089.87   70.14 1190.63    70.1 1275.72    70.5
  1381.5    70.5  1401.9    69.8 1409.14   69.65 1422.37    69.6 1455.71   69.99
#Mann= 3 ,0,0
       0    .035       0  451.75    .018       0  533.81    .035       0
Levee=-1,326.31,71.95,-1,647.12,70.84081,	341,	340
Bank Sta=451.75,533.81
XS Rating Curve= 0 ,0
Exp/Cntr=0.3,0.1

Type RM Length L Ch R = 1 ,6624.823,131.59,94.46,57.33
XS GIS Cut Line= 6
    1077850.8161    1572232.1172    1077906.1448    1572554.4187
    1077914.0826    1572610.7491     1077924.109    1572692.1077
    1077943.7248     1572852.662     1077993.903    1573633.3534
#Sta/Elev= 26
       0   70.25  159.41      71  235.22    71.5  341.95    71.5  372.44   69.32
   383.9   69.32  384.65   69.32  405.23   67.84  444.99   67.84  465.88   69.32
  582.12   69.31  603.17   70.81  627.63    70.8  629.35   70.24  708.45   70.01
  876.52      70  897.14    70.5 1032.99      70 1141.36      70 1212.72    70.3
 1242.65    70.5 1353.36    70.5 1360.11   70.42 1372.04      70 1397.87      70
 1409.93   70.15
#Mann= 3 ,0,0
       0    .035       0   383.9    .018       0  465.88    .035       0
Levee=-1,340.79,71.5,-1,603.18,70.80541,	341,	340
Bank Sta=383.9,465.88
XS Rating Curve= 0 ,0
Exp/Cntr=0.3,0.1

Type RM Length L Ch R = 1 ,6530.362,79.99,110.99,142
XS GIS Cut Line= 6
    1077700.1091    1572245.6639    1077774.2871    1572583.9064
    1077790.7026    1572674.0781    1077886.8148    1572731.9604
    1077901.6162    1572740.9649    1077953.2629      1573641.82
#Sta/Elev= 28
       0      70  140.37      71  183.49    71.5  261.92    71.5  323.27      71
  370.17   70.71  391.74   69.18  467.69    69.2  468.57    69.2  488.81   67.76
  529.02   67.75  550.13   69.25  640.79   69.27  662.05   70.76  686.75   70.76
  688.56   70.16  746.78      70  963.13      70  981.56   70.21 1001.39   70.21
 1057.27      70 1229.18      70 1285.03   70.38 1320.63    70.5 1434.49    70.5
 1441.04   70.41  1451.4    70.5 1469.79    70.5
#Mann= 3 ,0,0
       0    .035       0  467.69    .018       0  550.13    .035       0
Levee=-1,259.61,71.5,-1,662.07,70.76232,	341,	340
Bank Sta=467.69,550.13
XS Rating Curve= 0 ,0
Exp/Cntr=0.3,0.1

Type RM Length L Ch R = 1 ,6419.369,75.69,110.63,145.57
XS GIS Cut Line= 4
     1077636.609    1572260.0573    1077740.8731    1572639.9945
    1077809.3023    1572885.2722    1077905.0028    1573661.2934
#Sta/Elev= 22
       0      70   84.39    70.5  135.63      71  143.89      71  180.44    71.3
  277.11   71.26  360.29   70.63     373   70.63  393.98   69.13  512.11   69.13
  533.12   67.65  573.12   67.65  594.11   69.13   603.2   69.13   624.2   70.63
   648.6   70.63  650.08   70.14  715.95      70 1183.83      70 1277.46   70.41
 1326.95    70.5 1430.53    70.5
#Mann= 3 ,0,0
       0    .035       0  512.11    .018       0  594.11    .035       0
Levee=-1,225.35,71.33,-1,624.23,70.62785,	341,	340
Bank Sta=512.11,594.11
XS Rating Curve= 0 ,0
Exp/Cntr=0.3,0.1

Type RM Length L Ch R = 1 ,6308.738,137.26,95.23,53.18
XS GIS Cut Line= 6
    1077584.9622     1572271.064    1077696.0224    1572605.9842
    1077725.5092    1572696.9381    1077659.7331    1572797.3003
    1077647.6157    1572818.8584    1077849.1227    1573670.6068
#Sta/Elev= 21
       0   69.95   95.65    70.5  170.57   71.02  196.52   71.12  306.69   71.01
  377.18   70.59  398.18   69.09  486.46   69.05  507.46   67.55  547.46   67.55
  567.62   68.99  568.46   68.99   662.1   68.95  683.28   70.45  702.52   70.45
  702.74   70.36     851      70 1301.57      70 1363.22   70.13  1432.3    70.5
 1468.46    70.5
#Mann= 3 ,0,0
       0    .035       0  486.46    .018       0  568.46    .035       0
Levee=-1,197.41,71.12,-1,683.35,70.45068,	341,	340
Bank Sta=486.46,568.46
XS Rating Curve= 0 ,0
Exp/Cntr=0.3,0.1

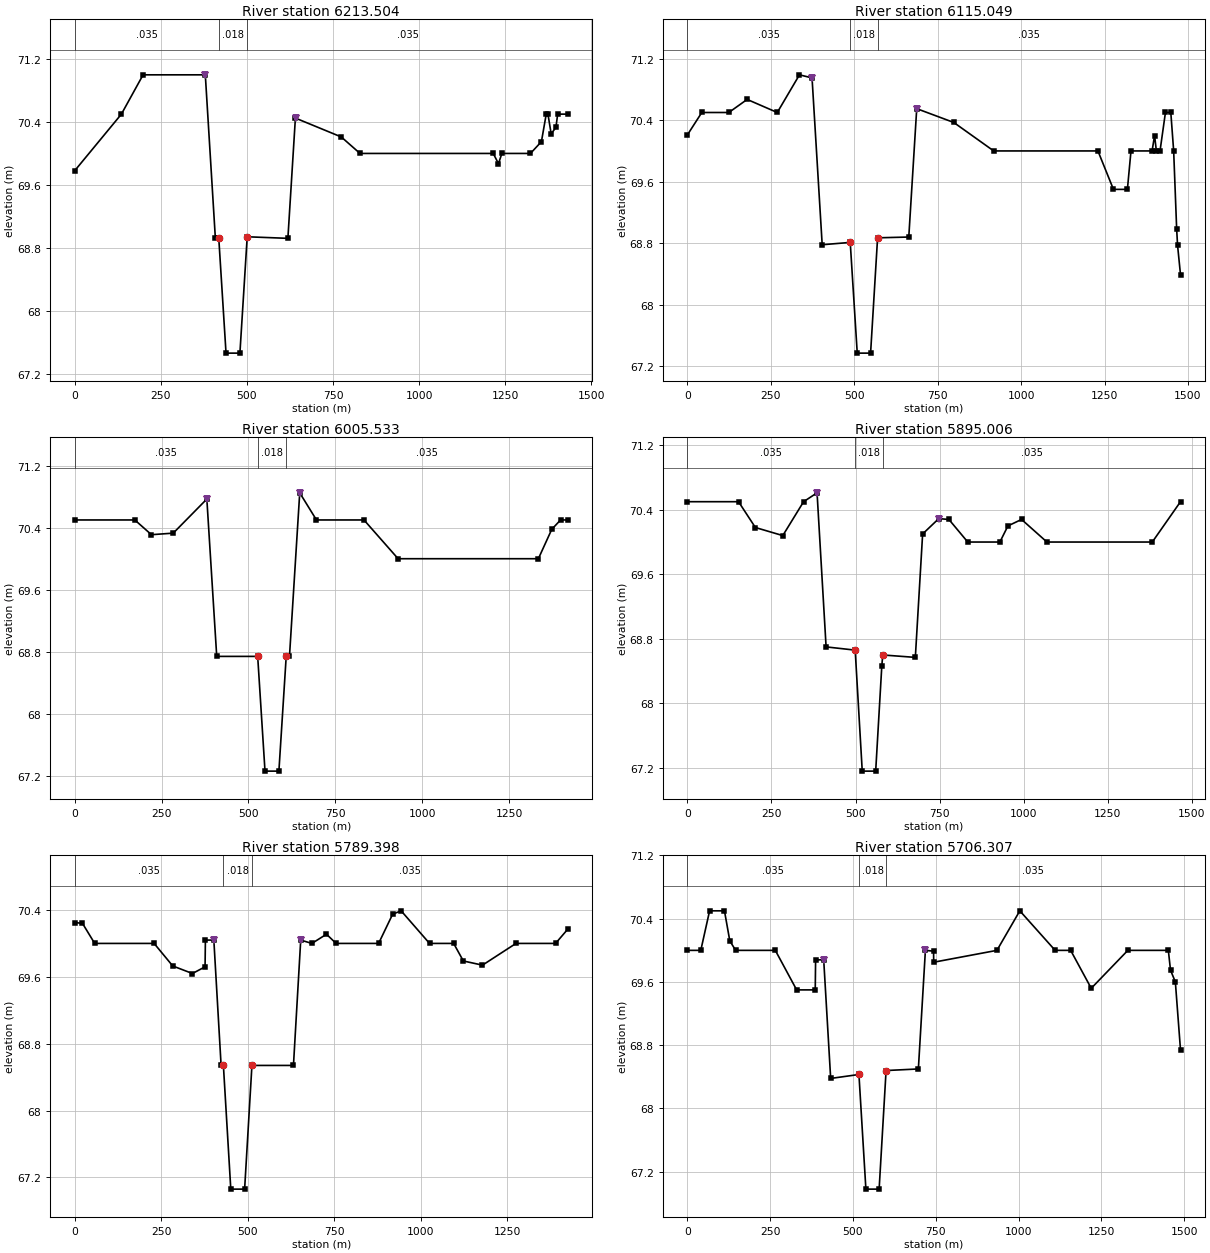
Type RM Length L Ch R = 1 ,6213.504,134.85,98.46,62.09
XS GIS Cut Line= 5
    1077443.5686    1572310.0107    1077551.8597    1572656.1842
     1077611.188    1572780.7703    1077628.1423    1572851.8785
     1077822.876    1573686.6935
#Sta/Elev= 24
       0   69.78  135.54    70.5  198.52      71   379.1      71  408.15   68.93
  418.07   68.93  439.24   67.46  479.53   67.46  500.71   68.94  618.79   68.92
  640.57   70.45  773.66   70.21  828.17      70 1214.78      70 1230.02   69.87
 1239.88      70 1322.84      70 1354.66   70.15 1368.61    70.5 1373.65    70.5
  1382.9   70.25  1396.7   70.33 1401.82    70.5 1431.04    70.5
#Mann= 3 ,0,0
       0    .035       0  418.07    .018       0  500.71    .035       0
Levee=-1,377.95,71,-1,640.9,70.45,	341,	340
Bank Sta=418.07,500.71
XS Rating Curve= 0 ,0
Exp/Cntr=0.3,0.1

Type RM Length L Ch R = 1 ,6115.049,74.08,109.52,144.96
XS GIS Cut Line= 6
    1077313.1817    1572370.9708    1077423.2416    1572712.0683
     1077468.122    1572801.0784    1077576.7283    1572827.4692
    1077593.4289    1572833.2518    1077788.1626    1573701.9335
#Sta/Elev= 30
       0   70.21   42.98    70.5  123.98    70.5  178.91   70.67  269.18    70.5
  335.65   70.99  373.42   70.95   403.8   68.78  487.87   68.81  508.87   67.37
  548.87   67.37  569.87   68.87  663.35   68.88  687.16   70.55  798.33   70.37
  917.92      70 1230.29      70 1276.75    69.5 1318.59    69.5 1329.36      70
 1392.59      70 1400.07    70.2 1405.43      70 1416.39      70 1432.61    70.5
 1448.72    70.5 1457.27      70 1466.29   68.98 1469.02   68.77 1477.78   68.39
#Mann= 3 ,0,0
       0    .035       0  487.87    .018       0  569.87    .035       0
Levee=-1,373.16,70.95,-1,687.14,70.55,	341,	340
Bank Sta=487.87,569.87
XS Rating Curve= 0 ,0
Exp/Cntr=0.3,0.1

Type RM Length L Ch R = 1 ,6005.533,74.56,110.53,146.5
XS GIS Cut Line= 5
    1077233.9476    1572400.4631    1077387.8418    1572729.4454
    1077445.6147    1572831.2056    1077528.2412    1572994.6647
    1077740.8903    1573719.1491
#Sta/Elev= 19
       0    70.5  172.95    70.5  220.77   70.31  283.52   70.33  380.17   70.77
  408.61   68.74  526.43   68.74  547.49   67.26  587.46   67.26   608.5   68.74
   617.9   68.74  647.39   70.85  695.53    70.5  832.23    70.5   930.4      70
 1333.93      70 1372.57   70.38 1397.81    70.5 1418.42    70.5
#Mann= 3 ,0,0
       0    .035       0  526.43    .018       0   608.5    .035       0
Levee=-1,379.8,70.77,-1,647.29,70.85,	341,	340
Bank Sta=526.43,608.5
XS Rating Curve= 0 ,0
Exp/Cntr=0.3,0.1

Type RM Length L Ch R = 1 ,5895.006,143.8,105.61,67.44
XS GIS Cut Line= 6
    1077188.4392    1572419.5131     1077357.076    1572745.2403
    1077410.6896    1572824.8556    1077363.6318    1572933.3258
    1077354.5979    1572960.3226    1077689.0319    1573749.8408
#Sta/Elev= 23
       0    70.5  151.99    70.5  202.07   70.18  283.61   70.08   345.5    70.5
  385.59   70.61  412.47    68.7  499.01   68.66  520.01   67.16  560.01   67.16
  578.16   68.46  581.01    68.6  677.97   68.57  699.67    70.1  747.63   70.29
  777.85   70.28  833.95      70  929.52      70  953.49    70.2  994.02   70.28
 1069.52      70 1382.95      70 1466.91    70.5
#Mann= 3 ,0,0
       0    .035       0  499.01    .018       0  581.01    .035       0
Levee=-1,385.13,70.61,-1,747.74,70.29,	341,	340
Bank Sta=499.01,581.01
XS Rating Curve= 0 ,0
Exp/Cntr=0.3,0.1

Type RM Length L Ch R = 1 ,5789.398,121.37,83.09,44.79
XS GIS Cut Line= 4
    1077060.3806    1572478.7799    1077233.6889    1572814.6025
    1077383.3932    1573074.5806    1077649.8734    1573773.1242
#Sta/Elev= 29
       0   70.25   22.52   70.24   57.81      70  229.63      70  283.56   69.73
  340.42   69.64  376.94   69.72  377.91   70.04  402.31   70.04  423.31   68.54
  429.95   68.54  451.32   67.06  491.32   67.06  512.44   68.54  632.51   68.54
  653.51   70.04  685.79      70  728.05   70.11  755.84      70  878.72      70
  919.34   70.35  943.87   70.39 1026.02      70 1095.71      70 1123.69   69.79
 1179.03   69.74 1275.93      70  1390.3      70 1425.55   70.17
#Mann= 3 ,0,0
       0    .035       0  429.95    .018       0  512.44    .035       0
Levee=-1,402.31,70.04148,-1,653.5,70.04148,	341,	340
Bank Sta=429.95,512.44
XS Rating Curve= 0 ,0
Exp/Cntr=0.3,0.1

Type RM Length L Ch R = 1 ,5706.307,81.06,119.33,157.59
XS GIS Cut Line= 6
    1076939.7304    1572538.0467    1077111.7443    1572884.8224
    1077159.8641    1572957.1476    1077285.0474    1572971.6098
    1077302.7394    1572979.3726    1077621.2984    1573788.9992
#Sta/Elev= 30
       0      70   40.27      70   66.86    70.5  111.76    70.5  127.91   70.12
  145.57      70   265.4      70  329.82    69.5  385.96    69.5  387.09   69.88
  411.55   69.88  432.59   68.38  517.98   68.43  538.98   66.98  578.98   66.98
  599.98   68.48  697.51    68.5  718.74      70   743.4   69.99  743.84   69.85
  934.84      70 1003.96    70.5 1110.66      70 1157.53      70 1219.69   69.52
 1330.28      70  1452.6      70 1459.15   69.75 1473.79    69.6 1489.35   68.74
#Mann= 3 ,0,0
       0    .035       0  517.98    .018       0  599.98    .035       0
Levee=-1,411.55,69.87965,-1,718.74,69.99842,	341,	340
Bank Sta=517.98,599.98
XS Rating Curve= 0 ,0
Exp/Cntr=0.3,0.1

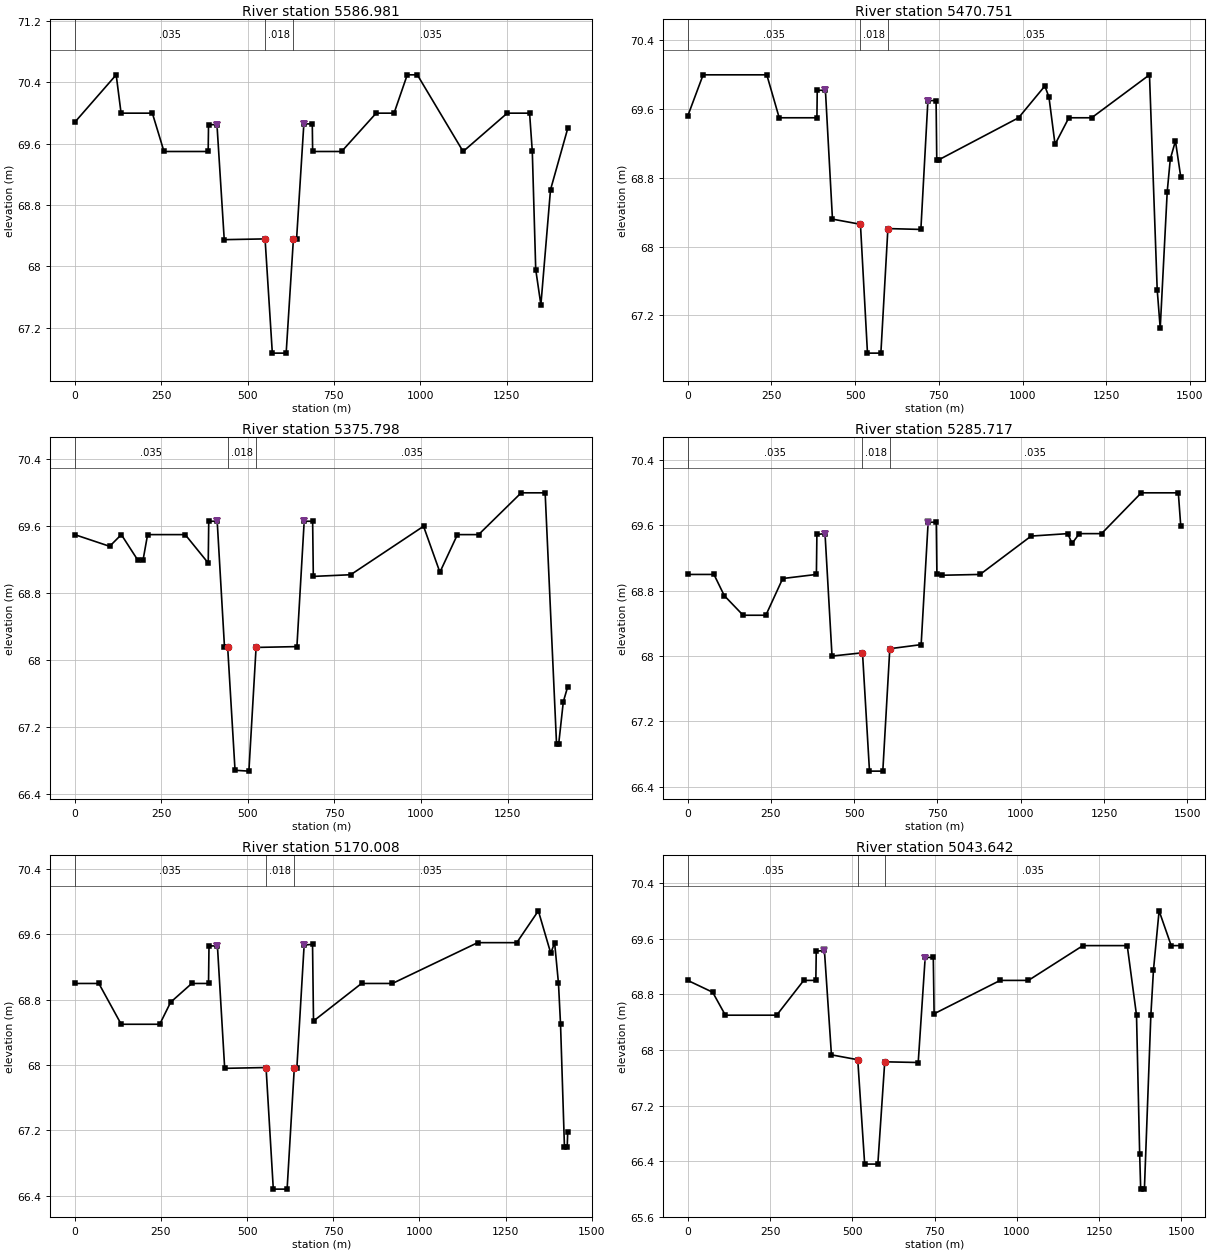
Type RM Length L Ch R = 1 ,5586.981,78.24,116.23,154.22
XS GIS Cut Line= 5
    1076899.5136    1572560.2718    1077090.7895    1572896.8889
    1077177.9757    1573035.2595     1077246.132    1573153.6204
    1077574.7316    1573815.4576
#Sta/Elev= 30
       0   69.88  120.01    70.5  134.18      70  224.66      70  258.32    69.5
  386.12    69.5  387.17   69.85  411.59   69.85   432.6   68.35  550.71   68.36
  571.73   66.87  611.73   66.87  632.72   68.36   641.9   68.36   662.9   69.86
   687.3   69.86  688.37    69.5  772.12    69.5   872.1      70  923.89      70
  962.03    70.5  991.19    70.5 1123.64    69.5 1251.27      70 1315.92      70
 1323.77    69.5 1333.68   67.96  1348.6    67.5 1376.42      69 1426.22    69.8
#Mann= 3 ,0,0
       0    .035       0  550.71    .018       0  632.72    .035       0
Levee=-1,411.59,69.85081,-1,662.9,69.85725,	341,	340
Bank Sta=550.71,632.72
XS Rating Curve= 0 ,0
Exp/Cntr=0.3,0.1

Type RM Length L Ch R = 1 ,5470.751,132.94,94.95,56.97
XS GIS Cut Line= 6
    1076870.9386    1572577.2051     1077067.716    1572910.1754
    1077118.5891    1572987.8393     1077072.109    1573096.5388
    1077064.6139    1573112.7229    1077505.9398    1573847.2077
#Sta/Elev= 30
       0   69.52   45.93      70  236.11      70   273.2    69.5  385.81    69.5
  386.77   69.82  411.21   69.82  432.24   68.32  515.83   68.26  536.83   66.76
  576.83   66.76  597.83   68.21   696.3    68.2  717.31    69.7  741.71    69.7
  743.77   69.01  749.47   69.01  988.08    69.5  1066.6   69.87 1078.89   69.74
 1097.03   69.19 1138.25    69.5 1206.37    69.5 1379.11      70 1402.13    67.5
 1411.17   67.05 1432.07   68.64  1441.3   69.02 1456.65   69.23 1472.54   68.81
#Mann= 3 ,0,0
       0    .035       0  515.83    .018       0  597.83    .035       0
Levee=-1,411.21,69.82031,-1,717.31,69.70021,	341,	340
Bank Sta=515.83,597.83
XS Rating Curve= 0 ,0
Exp/Cntr=0.3,0.1

Type RM Length L Ch R = 1 ,5375.798,128.33,90.08,51.83
XS GIS Cut Line= 4
    1076754.5217    1572643.8803    1076950.2991    1572977.7881
    1077100.0034    1573237.7662    1077475.2481    1573871.5494
#Sta/Elev= 30
       0    69.5  100.91   69.36  134.67    69.5  181.38    69.2  197.57    69.2
   210.5    69.5  319.08    69.5  385.58   69.16  387.07   69.66  411.47   69.66
  432.47   68.16  441.62   68.16  462.99   66.68     503   66.67  523.77   68.15
  641.67   68.16  662.67   69.66  687.07   69.66  689.05      69  796.94   69.02
 1007.31    69.6 1054.55   69.05 1105.13    69.5 1166.26    69.5 1289.24      70
 1358.44      70 1391.28      67  1397.7      67 1410.88    67.5 1423.61   67.68
#Mann= 3 ,0,0
       0    .035       0  441.62    .018       0  523.77    .035       0
Levee=-1,411.47,69.66111,-1,662.67,69.66111,	341,	340
Bank Sta=441.62,523.77
XS Rating Curve= 0 ,0
Exp/Cntr=0.3,0.1

Type RM Length L Ch R = 1 ,5285.717,76.24,115.71,155.18
XS GIS Cut Line= 6
    1076633.8714    1572711.6137    1076829.4693    1573046.4807
    1076877.2886    1573128.5979    1077000.4639    1573142.8945
    1077024.3972    1573148.7063    1077441.3814    1573888.4828
#Sta/Elev= 28
       0      69   78.73      69  109.78   68.74  166.28    68.5  234.63    68.5
  285.26   68.95  386.39      69  387.88   69.49  412.29    69.5  433.31      68
  524.84   68.04  545.84   66.59  585.84   66.59  606.84   68.09  700.97   68.14
  721.98   69.64  746.38   69.64   748.3      69  762.22   68.99  877.91      69
 1031.25   69.47 1141.26    69.5 1154.27   69.38 1175.95    69.5 1242.76    69.5
 1362.07      70 1473.37      70 1480.67   69.59
#Mann= 3 ,0,0
       0    .035       0  524.84    .018       0  606.84    .035       0
Levee=-1,412.22,69.49541,-1,721.98,69.6356,	341,	340
Bank Sta=524.84,606.84
XS Rating Curve= 0 ,0
Exp/Cntr=0.3,0.1

Type RM Length L Ch R = 1 ,5170.008,86.03,126.37,166.7
XS GIS Cut Line= 5
     1076613.763    1572720.0804    1076806.3819    1573058.7514
    1076892.0198    1573200.3694    1076955.7618    1573319.1616
    1077329.1978    1573958.3329
#Sta/Elev= 30
       0      69   70.07      69  134.95    68.5  246.67    68.5  278.32   68.77
  339.58      69  388.22      69   389.6   69.46  414.06   69.46   435.1   67.96
  555.11   67.97  576.15   66.48  616.17   66.48  637.12   67.97  644.56   67.97
  665.56   69.47  689.96   69.48  692.77   68.54  832.05      69  921.62      69
 1168.96    69.5 1282.43    69.5    1345   69.89 1381.04   69.37 1392.19    69.5
  1403.4      69 1409.36    68.5 1420.71      67 1428.75      67 1430.19   67.18
#Mann= 3 ,0,0
       0    .035       0  555.11    .018       0  637.12    .035       0
Levee=-1,414.06,69.46284,-1,665.53,69.47281,	341,	340
Bank Sta=555.11,637.12
XS Rating Curve= 0 ,0
Exp/Cntr=0.3,0.1

Type RM Length L Ch R = 1 ,5043.642,108.46,72.2,35.89
XS GIS Cut Line= 6
     1076564.143    1572746.4171    1076778.2474    1573072.9603
    1076830.8435    1573143.9279     1076774.338    1573249.5473
    1076768.6134    1573268.3881    1077229.6243    1574017.6896
#Sta/Elev= 30
       0      69   75.71   68.83  114.33    68.5  270.22    68.5  352.44      69
  389.21      69  390.48   69.42  415.29   69.43  436.62   67.93  516.59   67.86
  537.59   66.36  577.59   66.36  598.59   67.83  700.27   67.82  721.48   69.33
  746.11   69.33  748.58   68.52  949.27      69 1035.06      69 1200.76    69.5
  1335.4    69.5 1363.58    68.5 1373.19    66.5 1376.29      66 1387.57      66
 1407.17    68.5 1415.13   69.15 1432.21      70 1468.98    69.5 1498.05    69.5
#Mann= 3 ,0,0
       0    .035       0  516.59    .018       0  598.59    .035       0
Levee=-1,415.26,69.4268,-1,721.41,69.32333,	341,	340
Bank Sta=516.59,598.59
XS Rating Curve= 0 ,0
Exp/Cntr=0.3,0.1

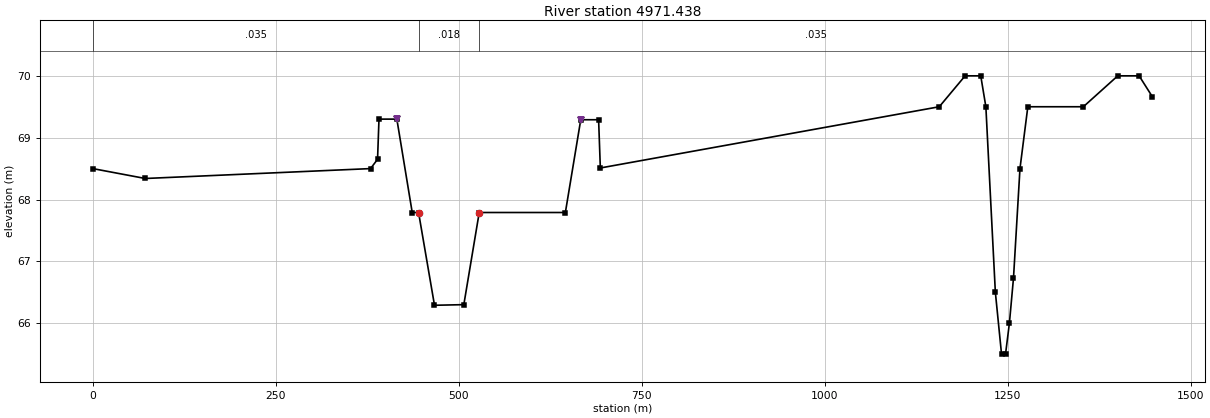
Type RM Length L Ch R = 1 ,4971.438,129.85,93.89,58
XS GIS Cut Line= 4
    1076473.9728    1572787.0572     1076687.982     1573114.152
    1076802.7586    1573391.3524    1077173.7442    1574050.7097
#Sta/Elev= 30
       0    68.5   71.73   68.34  379.43    68.5     389   68.65  390.96    69.3
  415.36    69.3  436.36   67.79  445.03   67.79  466.78   66.29  506.85    66.3
  527.88   67.79  645.56   67.79  666.56   69.29  690.96   69.29  693.32   68.51
  1156.3    69.5 1191.62      70 1212.95      70 1219.94    69.5 1232.91    66.5
 1241.35    65.5 1246.81    65.5 1252.08      66 1257.68   66.73 1266.53    68.5
 1277.26    69.5 1353.11    69.5 1400.12      70 1429.29      70 1447.47   69.66
#Mann= 3 ,0,0
       0    .035       0  445.03    .018       0  527.88    .035       0
Levee=-1,415.32,69.29515,-1,666.51,69.28973,	341,	340
Bank Sta=445.03,527.88
XS Rating Curve= 0 ,0
Exp/Cntr=0.3,0.1