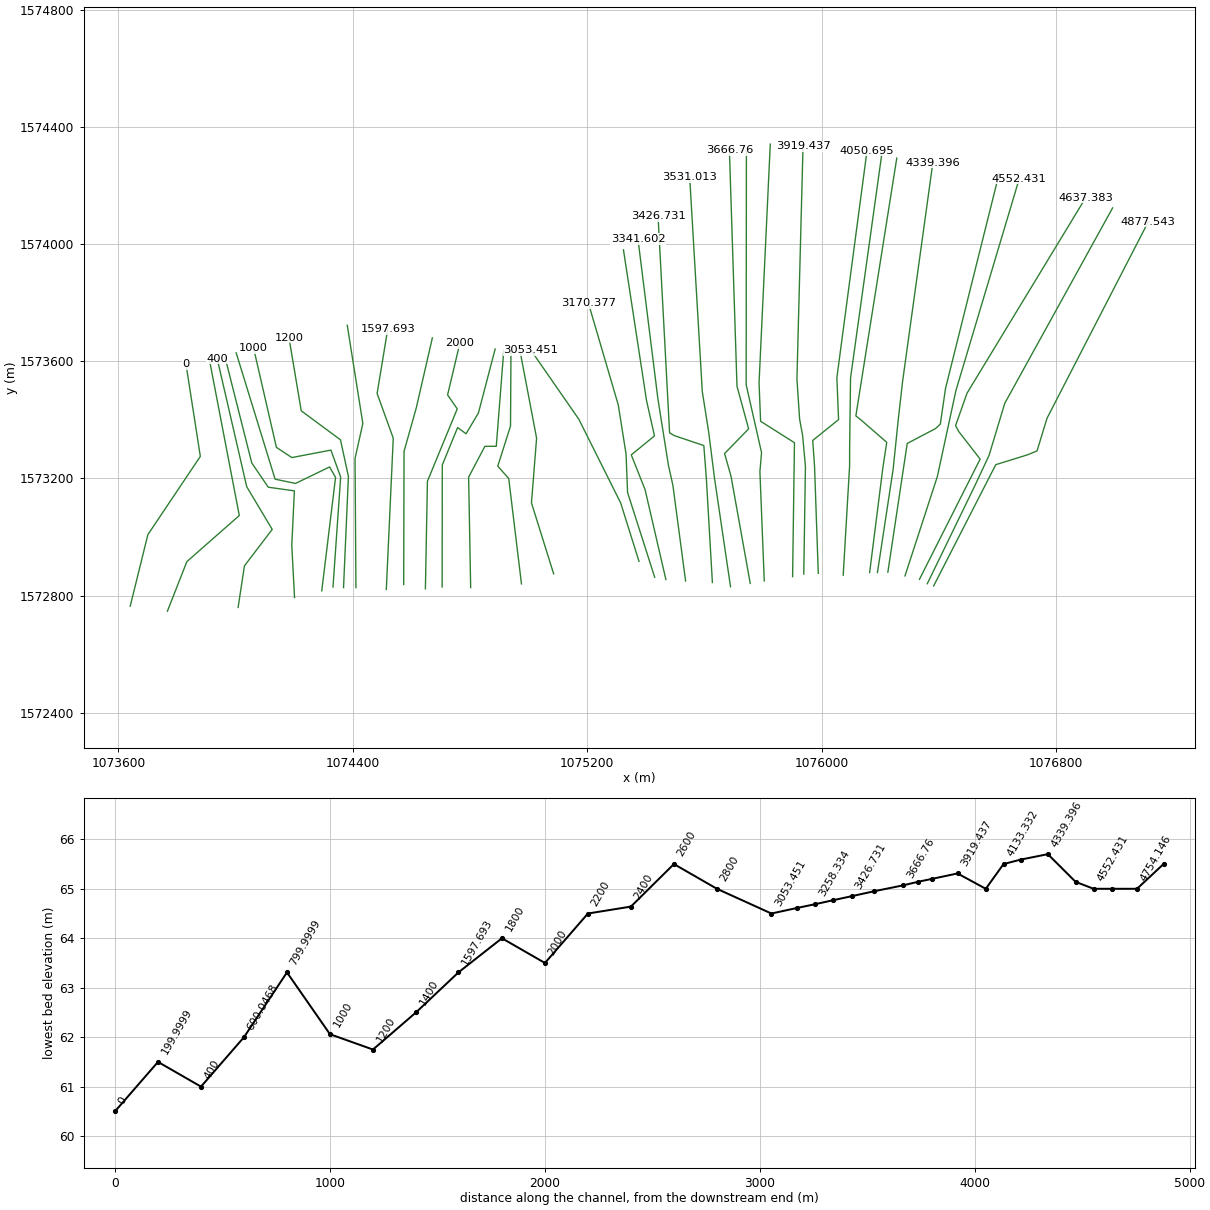
HEC-RAS study HECRAS_v1.prj: HECRAS_v1

--- HECRAS_v1.g01 (geometry) --- (continued)

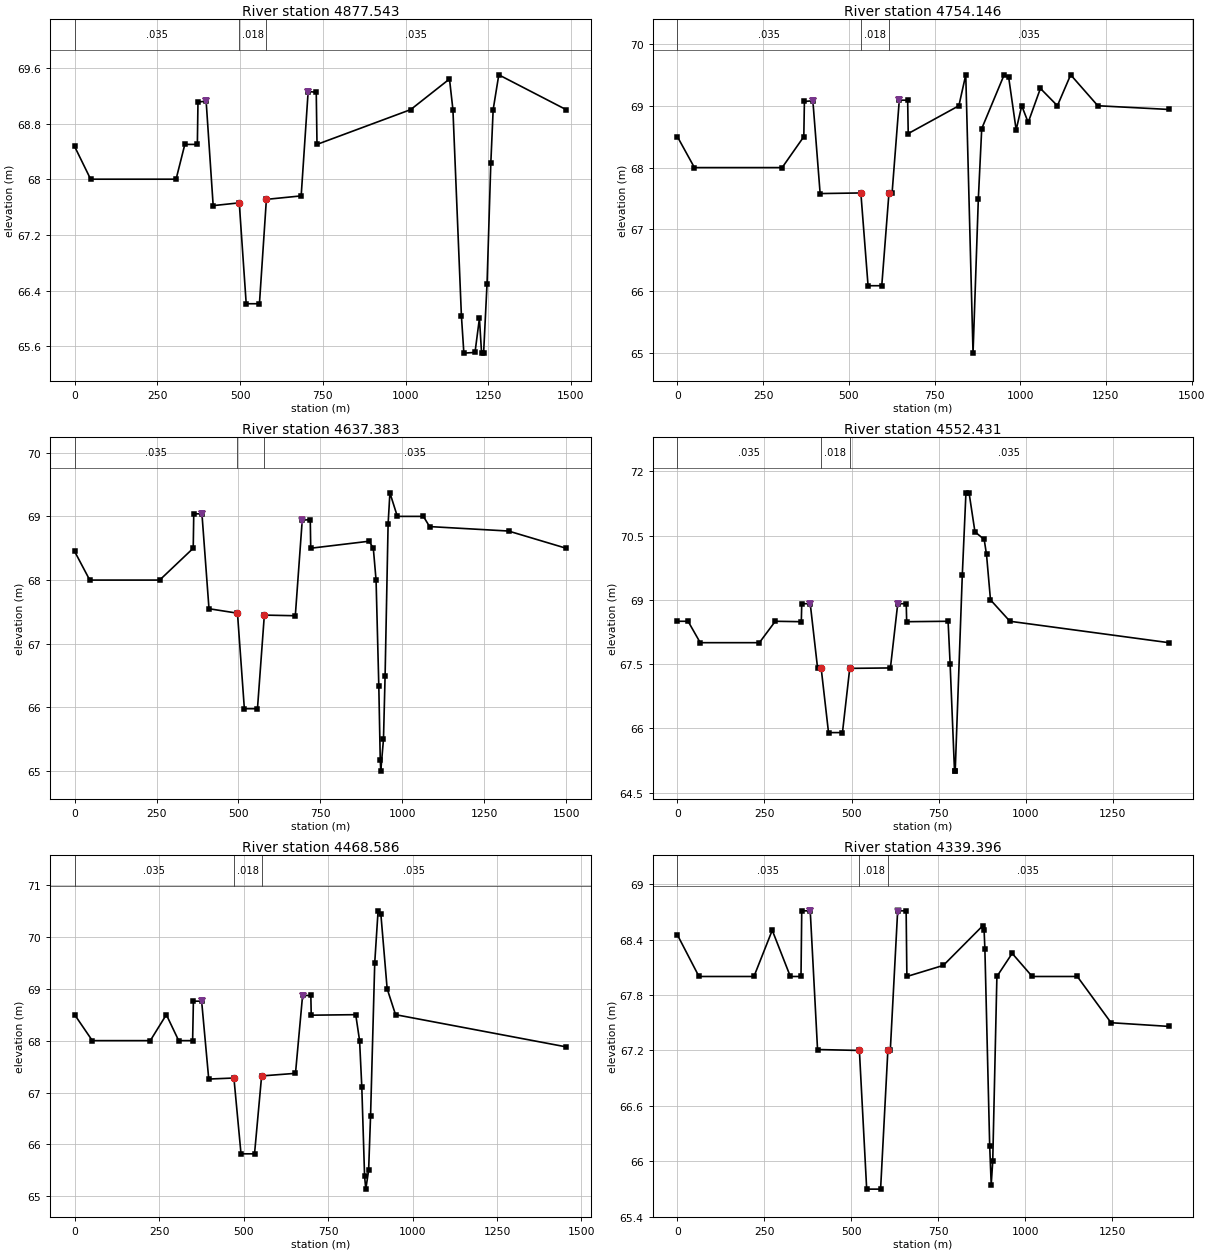
Type RM Length L Ch R = 1 ,4877.543,83.32,123.4,163.47
XS GIS Cut Line= 6
    1076382.5326    1572832.7773     1076594.623    1573246.7981
       1076703.8    1573280.6628    1076735.5933    1573293.7882
    1076769.4509    1573405.0022    1077115.3241    1574076.1098
#Sta/Elev= 30
       0   68.47   48.38      68  306.61      68  333.04    68.5  370.91    68.5
  372.77   69.11  397.46   69.12   418.7   67.62   497.5   67.66   518.5   66.21
   558.5   66.21   579.5   67.71  684.61   67.76  705.68   69.26  730.17   69.25
  732.43    68.5 1015.48      69 1132.79   69.44 1143.16      69 1168.77   66.04
 1176.23    65.5 1209.88   65.51 1223.25      66 1229.74    65.5 1235.88    65.5
 1246.28    66.5 1257.66   68.23 1264.76      69 1281.78    69.5 1485.14      69
#Mann= 3 ,0,0
       0    .035       0   497.5    .018       0   579.5    .035       0
Levee=-1,397.43,69.1175,-1,705.67,69.25621,	341,	340
Bank Sta=497.5,579.5
XS Rating Curve= 0 ,0
Exp/Cntr=0.3,0.1

Type RM Length L Ch R = 1 ,4754.146,77.69,116.76,155.84
XS GIS Cut Line= 5
    1076360.9426    1572840.3973    1076522.6273    1573173.6284
     1076571.763    1573278.5482     1076625.239    1573456.0351
    1076993.4038    1574123.0998
#Sta/Elev= 30
       0    68.5   49.67      68  305.51      68  368.72    68.5  370.46   69.07
  395.13   69.08  416.36   67.58  535.11   67.59  556.13   66.09   596.1   66.09
  617.11   67.59  626.21   67.59  647.21   69.09  671.61   69.09  673.27   68.55
  821.02      69  841.11    69.5  862.31      65  877.82    67.5  887.65   68.63
  953.05    69.5  966.27   69.46  988.07   68.61 1004.36      69  1023.2   68.73
 1058.81   69.28 1108.36      69  1147.1    69.5 1226.28      69 1433.53   68.94
#Mann= 3 ,0,0
       0    .035       0  535.11    .018       0  617.11    .035       0
Levee=-1,395.07,69.0767,-1,647.21,69.09055,	341,	340
Bank Sta=535.11,617.11
XS Rating Curve= 0 ,0
Exp/Cntr=0.3,0.1

Type RM Length L Ch R = 1 ,4637.383,120.75,84.95,49.15
XS GIS Cut Line= 6
    1076334.2725    1572855.6373    1076541.2829    1573265.8481
    1076467.9322    1573360.2821    1076457.4628    1573380.1484
    1076496.7003    1573491.0702    1076901.9637    1574158.6599
#Sta/Elev= 30
       0   68.45   46.23      68  259.58      68  362.04    68.5  363.67   69.04
  388.67   69.04  410.18   67.55  497.12   67.48  518.12   65.98  558.12   65.98
  579.12   67.45  673.65   67.44  694.77   68.94  719.31   68.95  720.72    68.5
  898.87   68.61  911.77    68.5  920.16      68  928.52   66.34  932.91   65.18
  934.48      65  942.79    65.5  947.72    66.5  956.91   68.88  962.43   69.37
  985.08      69 1064.59      69 1083.55   68.84 1324.44   68.77  1500.2    68.5
#Mann= 3 ,0,0
       0    .035       0  497.12    .018       0  579.12    .035       0
Levee=-1,388.6,69.0432,-1,694.69,68.93906,	341,	340
Bank Sta=497.12,579.12
XS Rating Curve= 0 ,0
Exp/Cntr=0.3,0.1

Type RM Length L Ch R = 1 ,4552.431,119.7,83.84,48
XS GIS Cut Line= 4
    1076284.7424    1572867.0673    1076395.3011    1573206.4879
    1076458.6237    1573499.6809    1076674.6332      1574222.16
#Sta/Elev= 30
       0    68.5   30.64    68.5   65.59      68  235.36      68  281.05    68.5
  355.73   68.49     357   68.91   381.4   68.91   402.4   67.41  412.68   67.41
  433.88    65.9  473.88    65.9   494.8    67.4  611.59   67.41  632.59   68.91
  656.99   68.91  658.24   68.49  777.15    68.5  783.01    67.5  795.58      65
  797.57      65  817.95   69.58   828.4    71.5  837.36    71.5  854.22   70.59
   880.8   70.41  887.44   70.06  898.88      69  954.63    68.5 1411.01      68
#Mann= 3 ,0,0
       0    .035       0  412.68    .018       0   494.8    .035       0
Levee=-1,381.33,68.90532,-1,632.53,68.90072,	341,	340
Bank Sta=412.68,494.8
XS Rating Curve= 0 ,0
Exp/Cntr=0.3,0.1

Type RM Length L Ch R = 1 ,4468.586,89.24,129.19,169.14
XS GIS Cut Line= 6
    1076226.3223    1572879.7674    1076292.3624    1573319.1882
    1076388.8975    1573369.8806    1076405.3927    1573385.2284
    1076423.1416    1573506.9892    1076606.0531    1574239.9401
#Sta/Elev= 30
       0    68.5   52.38      68  223.95      68  271.43    68.5  307.99      68
  349.22      68  351.49   68.76  375.89   68.76   396.9   67.26  471.41   67.28
  492.41   65.82  532.41   65.82  553.41   67.32  653.62   67.37  674.64   68.87
  699.07   68.87   700.2   68.49   831.9    68.5  843.31      68  849.85   67.11
  858.08   65.39  861.66   65.14  870.03    65.5  875.78   66.55  888.15    69.5
  898.03    70.5  906.37   70.43  924.85      69   949.7    68.5 1454.42   67.88
#Mann= 3 ,0,0
       0    .035       0  471.41    .018       0  553.41    .035       0
Levee=-1,375.89,68.75673,-1,674.56,68.86215,	341,	340
Bank Sta=471.41,553.41
XS Rating Curve= 0 ,0
Exp/Cntr=0.3,0.1

Type RM Length L Ch R = 1 ,4339.396,86.71,126.39,166.08
XS GIS Cut Line= 5
    1076190.7622    1572878.4974    1076244.4195    1573231.7166
    1076261.3718    1573396.5976    1076276.4864    1573530.0372
    1076379.9926    1574278.0402
#Sta/Elev= 30
       0   68.45   62.01      68  220.03      68  272.59    68.5   324.6      68
  355.22      68  357.35   68.71  381.76   68.71  402.76   67.21  523.02    67.2
  543.99    65.7  583.97    65.7  604.98   67.21  611.99   67.21  632.99   68.71
  657.38   68.71  659.51      68   764.3   68.12   877.9   68.55  881.45    68.5
  883.68    68.3  897.48   66.17  901.88   65.75  906.23      66   918.2      68
  962.09   68.25 1019.72      68  1149.3      68 1246.25    67.5 1412.45   67.46
#Mann= 3 ,0,0
       0    .035       0  523.02    .018       0  604.98    .035       0
Levee=-1,381.76,68.71024,-1,632.92,68.70232,	341,	340
Bank Sta=523.02,604.98
XS Rating Curve= 0 ,0
Exp/Cntr=0.3,0.1

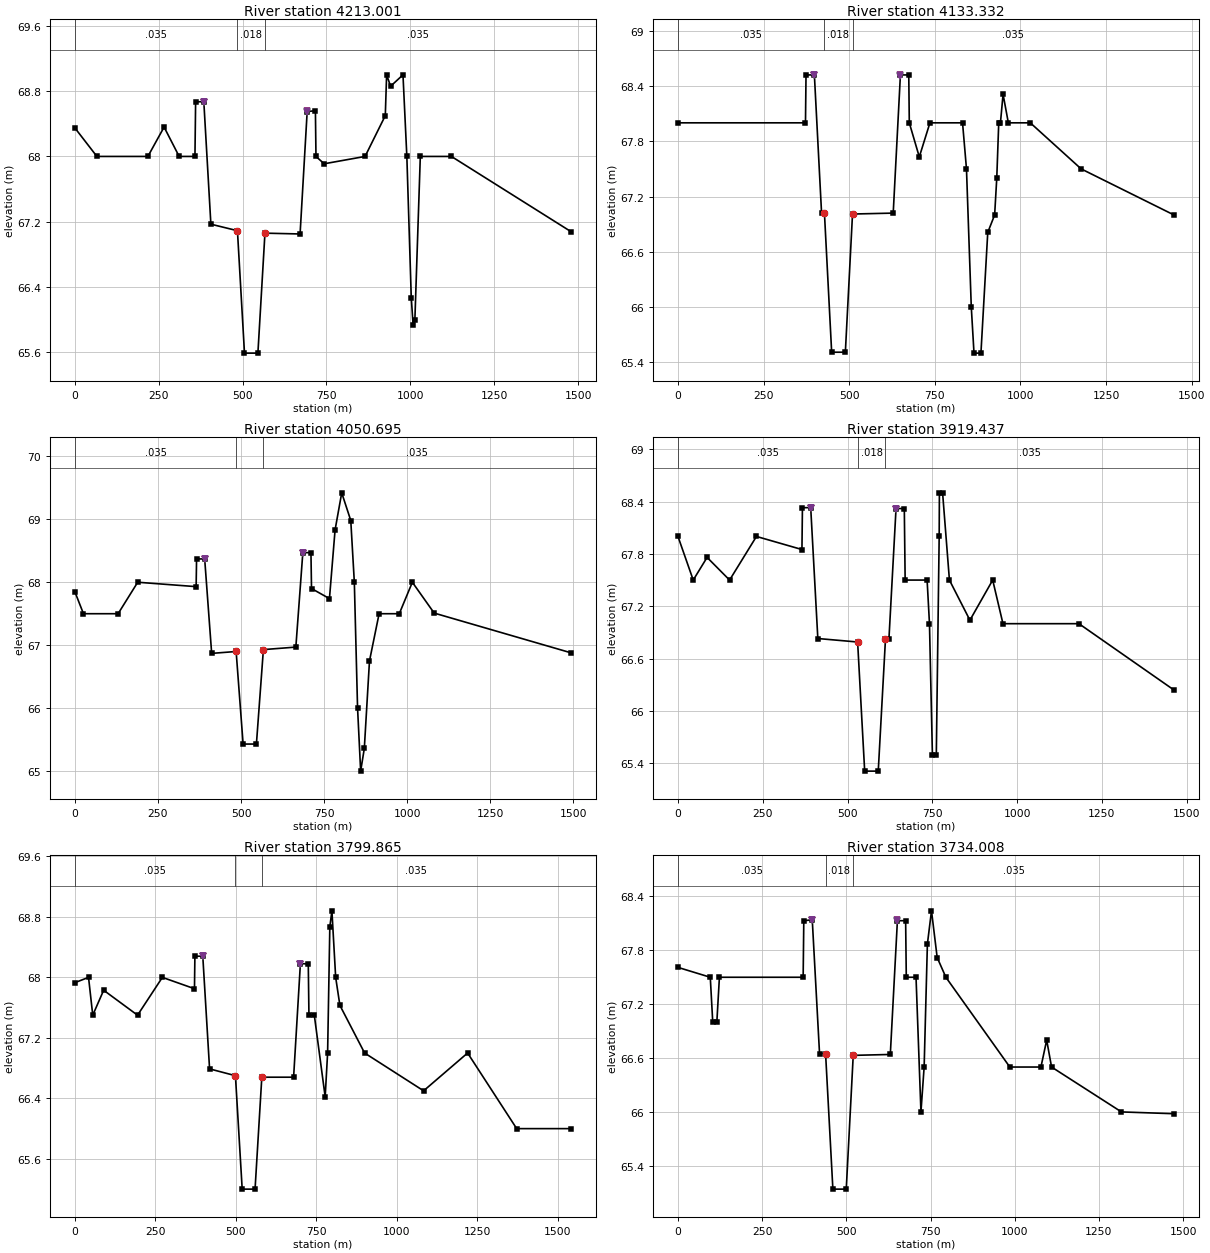
Type RM Length L Ch R = 1 ,4213.001,115.26,79.67,44.08
XS GIS Cut Line= 6
    1076164.0922    1572878.4974    1076209.2256     1573235.565
    1076222.5123    1573322.9982    1076133.2626    1573400.5867
    1076117.1021    1573413.1684    1076256.8024    1574293.2802
#Sta/Elev= 30
       0   68.35   65.75      68   217.7      68     266   68.36  310.94      68
  357.98      68  359.98   68.67  384.41   68.67  405.44   67.17  484.61   67.09
  505.61   65.59  545.61   65.59  566.61   67.06  671.33   67.05  692.46   68.55
  717.02   68.56   718.7      68  743.11   67.91  865.02      68  925.31    68.5
  929.23      69  941.06   68.86     978      69  989.52      68 1002.71   66.27
 1008.28   65.93 1013.48      66 1029.66      68  1122.4      68 1478.22   67.08
#Mann= 3 ,0,0
       0    .035       0  484.61    .018       0  566.61    .035       0
Levee=-1,384.42,68.66766,-1,692.46,68.55412,	341,	340
Bank Sta=484.61,566.61
XS Rating Curve= 0 ,0
Exp/Cntr=0.3,0.1

Type RM Length L Ch R = 1 ,4133.332,118.69,82.64,46.58
XS GIS Cut Line= 5
     1076073.922    1572869.6073    1076095.7669    1573242.7902
    1076095.8113    1573296.6783    1076098.9794    1573542.8593
    1076206.0023    1574309.7902
#Sta/Elev= 30
       0      68  372.36      68  373.92   68.52  398.33   68.52  419.33   67.02
  427.71   67.02  448.79   65.51  488.77   65.51   509.7   67.01  628.54   67.02
  649.54   68.52  673.95   68.52   675.5      68   704.7   67.63  735.73      68
  830.98      68  842.46    67.5   856.5      66  864.43    65.5  884.68    65.5
   904.6   66.81   924.7      67  930.92    67.4  936.67      68  941.65      68
  949.31   68.31  964.73      68 1028.81      68 1177.27    67.5 1448.27      67
#Mann= 3 ,0,0
       0    .035       0  427.71    .018       0   509.7    .035       0
Levee=-1,398.26,68.52109,-1,649.51,68.51376,	341,	340
Bank Sta=427.71,509.7
XS Rating Curve= 0 ,0
Exp/Cntr=0.3,0.1

Type RM Length L Ch R = 1 ,4050.695,91.93,131.26,170.59
XS GIS Cut Line= 6
    1075988.8318    1572875.9574    1075976.0759    1573241.9826
    1075969.7818    1573329.3483    1076058.1338    1573400.5828
    1076052.2987    1573543.5784    1076155.2022    1574318.6802
#Sta/Elev= 30
       0   67.85   25.95    67.5  130.16    67.5  189.18      68  364.95   67.93
  366.28   68.37  390.69   68.37   411.7   66.87  485.33    66.9  506.33   65.43
  546.33   65.43  567.33   66.93  664.99   66.97     686   68.47  710.43   68.47
  712.14    67.9  766.12   67.74  783.01   68.83  803.04   69.42  830.27   68.98
  840.97      68  850.71      66  859.99      65  871.02   65.36  886.55   66.75
   915.5    67.5  976.22    67.5 1015.52      68 1081.23   67.51 1492.35   66.88
#Mann= 3 ,0,0
       0    .035       0  485.33    .018       0  567.33    .035       0
Levee=-1,390.63,68.36914,-1,686.03,68.46698,	341,	340
Bank Sta=485.33,567.33
XS Rating Curve= 0 ,0
Exp/Cntr=0.3,0.1

Type RM Length L Ch R = 1 ,3919.437,81.06,119.57,158.08
XS GIS Cut Line= 6
    1075939.3017    1572873.4173    1075944.9918     1573240.313
    1075935.4917    1573345.8583     1075925.201     1573401.759
    1075915.9794    1573539.0491    1075936.7617    1574333.9203
#Sta/Elev= 30
       0      68   44.98    67.5   85.85   67.76   152.2    67.5  231.42      68
  365.57   67.85  367.01   68.33  391.42   68.33  412.42   66.83  529.75   66.79
  550.55   65.31  590.57   65.31  611.84   66.82  622.02   66.82  643.02   68.32
  667.42   68.32  669.89    67.5  734.65    67.5  741.62      67  750.32   65.49
  761.78    65.5  770.24      68  770.91    68.5  780.32    68.5  800.45    67.5
  860.88   67.04  928.06    67.5  958.33      67 1182.36      67 1462.49   66.24
#Mann= 3 ,0,0
       0    .035       0  529.75    .018       0  611.84    .035       0
Levee=-1,391.34,68.32965,-1,642.95,68.31428,	341,	340
Bank Sta=529.75,611.84
XS Rating Curve= 0 ,0
Exp/Cntr=0.3,0.1

Type RM Length L Ch R = 1 ,3799.865,97.98,65.86,33.74
XS GIS Cut Line= 6
    1075901.2017    1572864.5273    1075907.5517    1573321.7282
    1075803.0057    1573387.9396    1075791.9814    1573394.7534
     1075786.682    1573526.0121    1075825.0015    1574340.9053
#Sta/Elev= 30
       0   67.93   42.55      68   55.67    67.5   89.53   67.83  194.85    67.5
  271.96      68  371.73   67.85  373.03   68.28  397.55   68.28  418.66   66.79
  498.99    66.7  519.99    65.2  559.99    65.2  580.99   66.68  679.75   66.68
  700.84   68.18  725.34   68.18  727.42    67.5  744.08    67.5  777.85   66.42
  785.42      67  792.32   68.67   798.8   68.88  810.47      68  823.59   67.63
  900.37      67 1083.71    66.5 1220.45      67 1372.93      66 1541.11      66
#Mann= 3 ,0,0
       0    .035       0  498.99    .018       0  580.99    .035       0
Levee=-1,397.48,68.28445,-1,700.83,68.17663,	341,	340
Bank Sta=498.99,580.99
XS Rating Curve= 0 ,0
Exp/Cntr=0.3,0.1

Type RM Length L Ch R = 1 ,3734.008,108.06,67.25,26.76
XS GIS Cut Line= 5
    1075804.4698    1572849.9223    1075789.6089    1573223.3002
    1075795.2326    1573287.7291    1075742.7034    1573519.6107
    1075743.5097    1574316.3519
#Sta/Elev= 30
       0   67.61   95.96    67.5  103.26      67  115.44      67  123.08    67.5
  371.76    67.5  373.67   68.13  398.79   68.14  420.41   66.65  438.35   66.65
  460.03   65.14  499.76   65.14  520.46   66.63  630.59   66.64  651.64   68.13
   676.1   68.13  678.02    67.5  706.95    67.5  721.56      66  731.03    66.5
   740.7   67.87  752.87   68.24  769.74   67.72   795.6    67.5   985.5    66.5
 1077.86    66.5 1094.95    66.8 1109.44    66.5 1316.99      66 1472.85   65.98
#Mann= 3 ,0,0
       0    .035       0  438.35    .018       0  520.46    .035       0
Levee=-1,398.75,68.13969,-1,651.64,68.13318,	341,	340
Bank Sta=438.35,520.46
XS Rating Curve= 0 ,0
Exp/Cntr=0.3,0.1

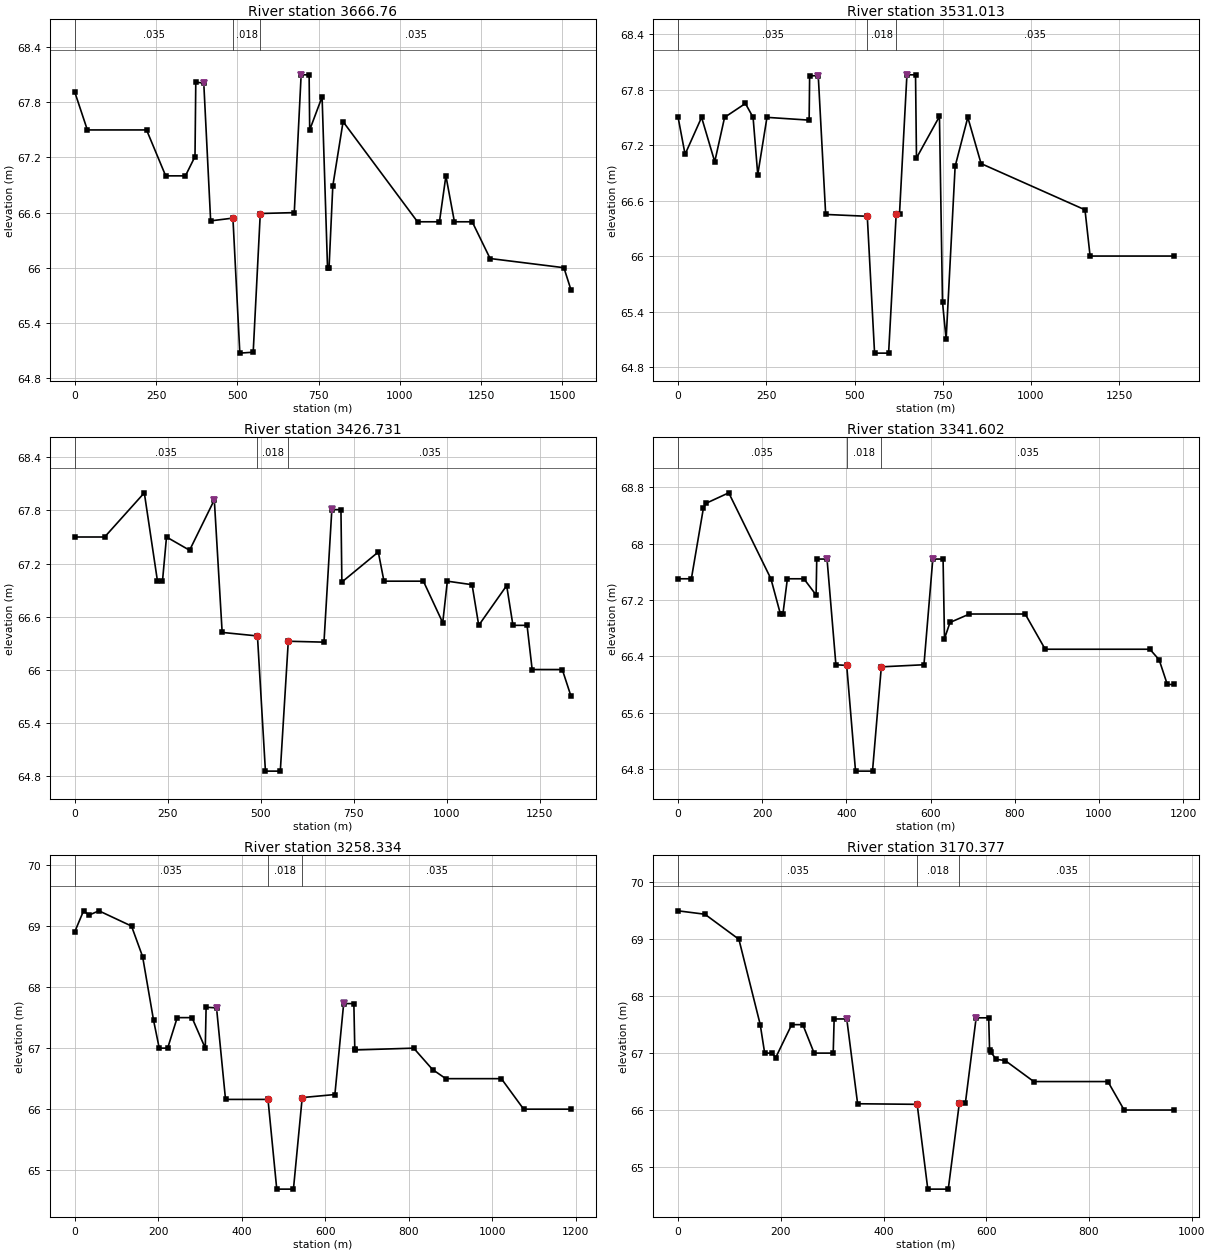
Type RM Length L Ch R = 1 ,3666.76 ,97.63,135.75,173.54
XS GIS Cut Line= 6
     1075756.633    1572841.4556    1075690.9219    1573207.6782
    1075669.0029    1573284.6865     1075751.079    1573369.0688
    1075711.3641    1573514.6497    1075685.5129    1574319.7386
#Sta/Elev= 30
       0   67.91   38.47    67.5  220.65    67.5  279.46      67   340.2      67
  369.66   67.21  372.07   68.02  396.65   68.01   417.8   66.51  486.35   66.54
  507.57   65.07  548.72   65.08  570.49   66.59  675.08    66.6  696.21    68.1
  720.75    68.1  722.55    67.5  760.66   67.86  777.38      66  782.08      66
  793.63   66.89  825.25   67.59 1054.23    66.5 1121.74    66.5 1141.59      67
 1167.79    66.5  1222.5    66.5 1277.57    66.1 1504.65      66 1526.26   65.76
#Mann= 3 ,0,0
       0    .035       0  486.35    .018       0  570.49    .035       0
Levee=-1,396.65,68.01248,-1,696.21,68.0983,	341,	340
Bank Sta=486.35,570.49
XS Rating Curve= 0 ,0
Exp/Cntr=0.3,0.1

Type RM Length L Ch R = 1 ,3531.013,59.63,104.28,148.99
XS GIS Cut Line= 5
    1075689.3229    1572830.0256     1075634.901    1573198.8102
    1075614.3722    1573360.8447    1075592.9913    1573495.9114
    1075549.9401    1574227.6634
#Sta/Elev= 30
       0    67.5   19.76    67.1   66.56    67.5  103.84   67.02  131.76    67.5
   190.7   67.65   212.5    67.5  225.73   66.88  251.83    67.5  371.32   67.47
  372.78   67.95  397.19   67.95   418.2   66.45  536.11   66.43  556.78   64.95
  596.55   64.95  618.12   66.46  627.46   66.46  648.46   67.96  672.86   67.96
  675.55   67.06  740.63   67.51  749.32    65.5  759.58    65.1  785.09   66.97
  821.01    67.5  858.59      67 1153.07    66.5 1167.56      66 1405.87      66
#Mann= 3 ,0,0
       0    .035       0  536.11    .018       0  618.12    .035       0
Levee=-1,397.19,67.95079,-1,648.45,67.95578,	341,	340
Bank Sta=536.11,618.12
XS Rating Curve= 0 ,0
Exp/Cntr=0.3,0.1

Type RM Length L Ch R = 1 ,3426.731,129.79,85.13,40.45
XS GIS Cut Line= 6
    1075627.4103    1572844.6306    1075607.1429    1573194.4161
    1075598.2002    1573311.9916    1075498.3482    1573345.6608
      1075481.36    1573355.1716    1075441.9899    1574094.3131
#Sta/Elev= 30
       0    67.5   80.12    67.5   186.7      68  222.09      67  235.53      67
  246.34    67.5  308.41   67.35  374.85   67.92  395.92   66.42  490.78   66.38
  512.21   64.85  552.21   64.85  573.66   66.32   669.6   66.31  690.69   67.81
  715.19   67.81  717.68   66.99  815.59   67.33  830.81      67  936.77      67
  988.77   66.53 1001.15      67 1067.64   66.96 1085.51    66.5 1160.61   66.95
 1177.49    66.5 1215.41    66.5 1229.11      66 1310.09      66 1333.33    65.7
#Mann= 3 ,0,0
       0    .035       0  490.78    .018       0  573.66    .035       0
Levee=-1,374.85,67.91953,-1,690.69,67.81227,	341,	340
Bank Sta=490.78,573.66
XS Rating Curve= 0 ,0
Exp/Cntr=0.3,0.1

Type RM Length L Ch R = 1 ,3341.602,126.01,83.27,40.5
XS GIS Cut Line= 5
    1075535.9701    1572849.7106    1075492.6232    1573176.2878
    1075477.1842    1573245.7481    1075441.3828     1573471.912
    1075373.4098     1574016.843
#Sta/Elev= 30
       0    67.5   31.53    67.5   60.02    68.5   65.89   68.57  120.34   68.72
  220.52    67.5  243.08      67  249.02      67  259.66    67.5  298.88    67.5
  327.91   67.27  329.44   67.78  353.89   67.78  374.93   66.28   400.6   66.27
  421.58   64.77  461.92   64.77  482.88   66.25  584.18   66.28  605.18   67.78
  629.58   67.78  632.97   66.65  646.01   66.88   692.3      67  824.68      67
  872.25    66.5 1120.97    66.5 1143.02   66.35 1162.39      66 1178.73      66
#Mann= 3 ,0,0
       0    .035       0   400.6    .018       0  482.88    .035       0
Levee=-1,353.89,67.78058,-1,605.18,67.77722,	341,	340
Bank Sta=400.6,482.88
XS Rating Curve= 0 ,0
Exp/Cntr=0.3,0.1

Type RM Length L Ch R = 1 ,3258.334,45.21,87.96,130.7
XS GIS Cut Line= 6
      1075468.66    1572854.7906    1075397.7402     1573161.268
    1075350.5497    1573280.2415    1075429.7808    1573344.9978
    1075402.6022    1573465.7731    1075323.8797    1573980.0129
#Sta/Elev= 30
       0   68.91   20.91   69.25   34.05   69.18   57.75   69.25  135.83      69
   162.4    68.5  188.54   67.46  202.25      67  222.42      67  245.32    67.5
  280.79    67.5  312.56      67  314.58   67.67  339.58   67.66   361.1   66.16
  462.89   66.16  483.89   64.69  523.89   64.69  544.89   66.19   623.2   66.24
  644.24   67.73  668.69   67.73  670.95   66.98  671.58   66.97  812.08      67
  857.18   66.65  889.04    66.5 1022.19    66.5 1075.62      66 1188.92      66
#Mann= 3 ,0,0
       0    .035       0  462.89    .018       0  544.89    .035       0
Levee=-1,339.58,67.66425,-1,644.24,67.73341,	341,	340
Bank Sta=462.89,544.89
XS Rating Curve= 0 ,0
Exp/Cntr=0.3,0.1

Type RM Length L Ch R = 1 ,3170.377,105.01,116.93,129.01
XS GIS Cut Line= 5
    1075430.5599    1572862.4107    1075337.9403    1573151.8017
    1075332.7697    1573282.7815    1075306.2176    1573450.5156
    1075204.4994    1573797.1325
#Sta/Elev= 29
       0    69.5   52.22   69.44  118.38      69  159.94    67.5  168.56      67
  183.23      67  190.02   66.92  221.16    67.5  242.88    67.5  264.87      67
  302.03      67  303.85    67.6  328.42    67.6  349.57   66.11  465.52    66.1
  486.21   64.61  526.05   64.61  547.63   66.12  559.36   66.12  580.36   67.62
  604.76   67.62  606.53   67.06  608.65   67.02  619.57   66.89   636.8   66.87
  692.59    66.5  836.87    66.5  868.55      66  965.99      66
#Mann= 3 ,0,0
       0    .035       0  465.52    .018       0  547.63    .035       0
Levee=-1,328.42,67.60355,-1,580.36,67.6181,	341,	340
Bank Sta=465.52,547.63
XS Rating Curve= 0 ,0
Exp/Cntr=0.3,0.1

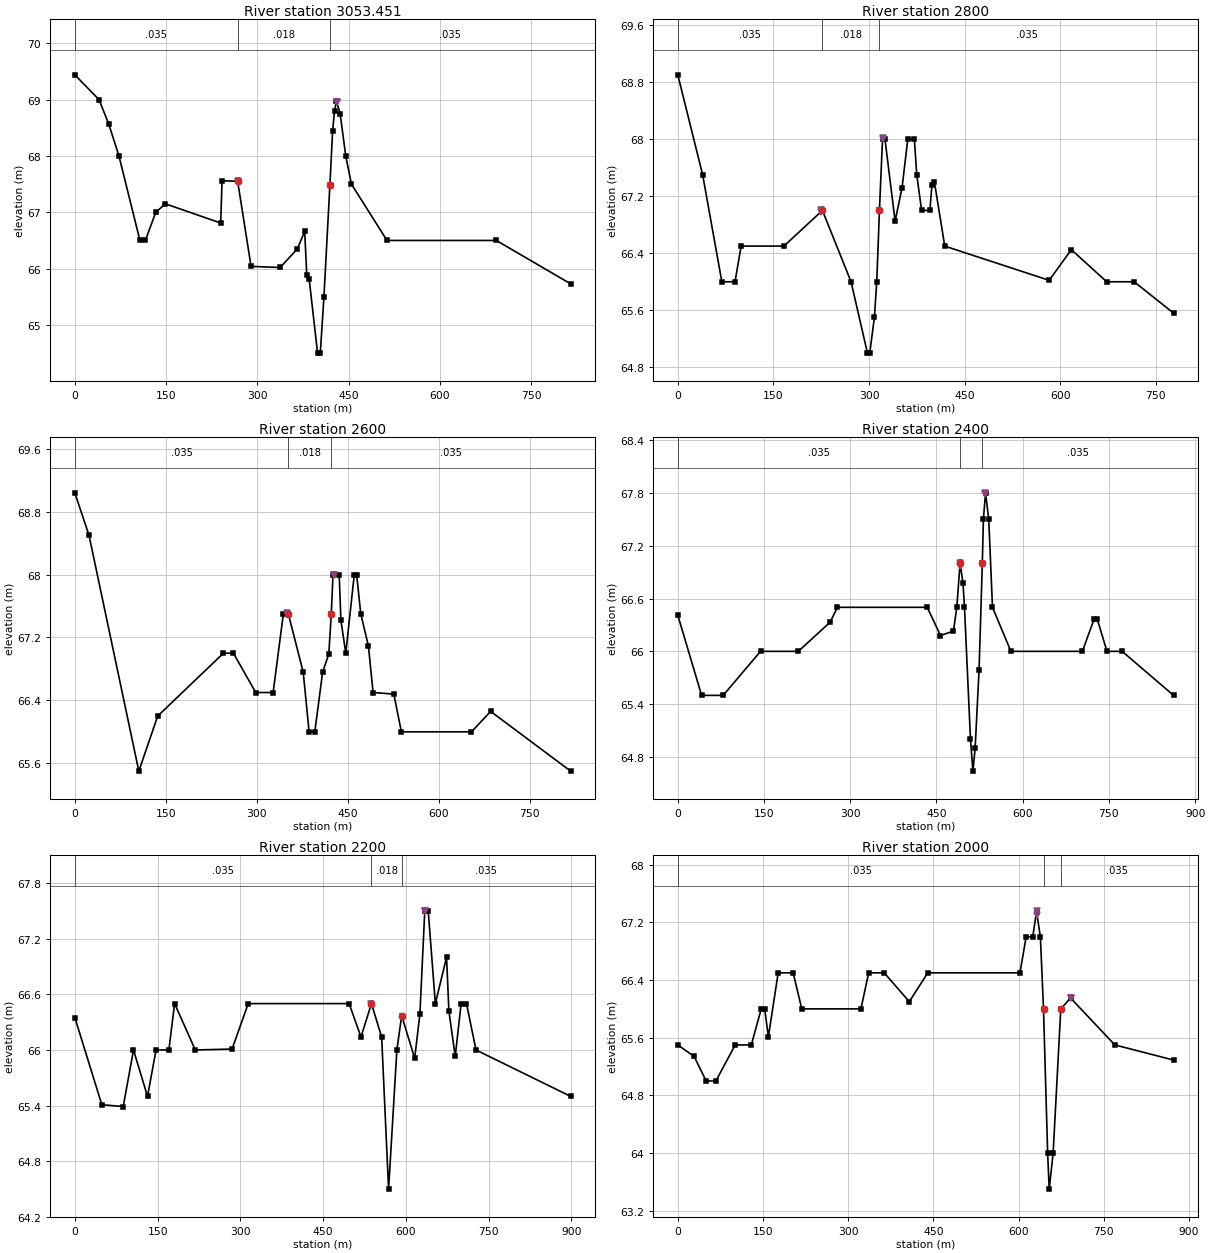
Type RM Length L Ch R = 1 ,3053.451,270.63,253.45,287.83
XS GIS Cut Line= 4
    1075376.9439    1572916.6924    1075314.3958    1573116.1355
    1075171.5789    1573401.7692    1075008.1404    1573637.4453
#Sta/Elev= 30
       0   69.44   39.74      69   55.61   68.57   72.54      68  107.01    66.5
  115.95    66.5  133.06      67   148.9   67.15  239.77   66.81  242.11   67.56
  267.71   67.55  289.73   66.04  337.54   66.02   365.8   66.35  377.88   66.66
  381.37   65.88   385.3   65.81  399.12    64.5  403.57    64.5  409.55    65.5
  419.34   67.48  423.79   68.44  426.94    68.8   430.1   68.97  436.21   68.75
  445.38      68  454.75    67.5   513.2    66.5  692.88    66.5  815.17   65.73
#Mann= 3 ,0,0
       0    .035       0  267.71    .018       0  419.34    .035       0
Levee=-1,267.7,67.54606,-1,430.42,68.96,	341,
Bank Sta=267.71,419.34
XS Rating Curve= 0 ,0
Exp/Cntr=0.3,0.1

Type RM Length L Ch R = 1 ,2800    ,173.16,200,161.41
XS GIS Cut Line= 4
    1075085.5796    1572874.2425    1075009.8838    1573116.4647
    1075027.4083    1573337.2613    1074970.9089    1573634.4449
#Sta/Elev= 30
       0    68.9   38.96    67.5   69.12      66   89.75      66   99.35    66.5
  166.51    66.5  226.86      67  271.77      66  297.53      65   301.1      65
  308.41    65.5  312.09      66  316.31      67  321.15      68  324.95      68
  340.91   66.85  351.83   67.32  360.81      68   371.1      68  374.83    67.5
  382.45      67  395.47      67  398.59   67.35  402.53    67.4  418.76    66.5
  582.56   66.02  617.34   66.45  672.77      66  715.87      66  777.77   65.56
#Mann= 3 ,0,0
       0    .035       0  226.86    .018       0  316.31    .035       0
Levee=-1,224.9,67.01,-1,321.35,68.01,,
Bank Sta=226.86,316.31
XS Rating Curve= 0 ,0
Exp/Cntr=0.3,0.1

Type RM Length L Ch R = 1 ,2600    ,229.25,200,147.14
XS GIS Cut Line= 5
    1074975.7773    1572839.8466     1074932.279    1573199.6772
    1074894.8615    1573241.6759     1074938.394    1573378.7808
    1074939.9526    1573633.6511
#Sta/Elev= 30
       0   69.04   23.35    68.5   105.5    65.5  136.59    66.2  244.93      67
  261.49      67   298.2    66.5  326.92    66.5  343.78    67.5  351.98    67.5
  376.49   66.76  386.23      66  395.64      66  408.54   66.76   418.7   66.99
  422.83    67.5  425.62      68  435.84      68  438.62   67.42  446.68      67
  460.71      68  464.56      68  471.42    67.5  484.04   67.09  491.71    66.5
  525.94   66.48  538.33      66  653.93      66  685.49   66.26  817.42    65.5
#Mann= 3 ,0,0
       0    .035       0  351.98    .018       0  422.83    .035       0
Levee=-1,349.3,67.51,-1,427.04,68,,
Bank Sta=351.98,422.83
XS Rating Curve= 0 ,0
Exp/Cntr=0.3,0.1

Type RM Length L Ch R = 1 ,2400    ,152.29,200,272.51
XS GIS Cut Line= 5
     1074802.369    1572827.1995     1074795.417    1573204.1704
    1074850.8937    1573309.4669    1074889.7875    1573309.4669
    1074915.3463    1573636.0324
#Sta/Elev= 30
       0   66.41   41.48    65.5   78.92    65.5  143.92      66  209.61      66
  264.77   66.33  277.81    66.5  433.93    66.5  456.96   66.18  479.54   66.23
  485.32    66.5  491.07      67  496.05   66.78  498.73    66.5  509.15      65
  513.38   64.64  517.26    64.9  524.09   65.79  529.76      67  531.63    67.5
  535.31    67.8  540.91    67.5  547.43    66.5  579.46      66  703.84      66
  724.39   66.37  729.48   66.37   746.6      66  773.03      66  862.51    65.5
#Mann= 3 ,0,0
       0    .035       0  491.07    .018       0  529.76    .035       0
Levee=-1,490.7,67,-1,535.08,67.8,,
Bank Sta=491.07,529.76
XS Rating Curve= 0 ,0
Exp/Cntr=0.3,0.1

Type RM Length L Ch R = 1 ,2200    ,201.37,200,132.8
XS GIS Cut Line= 6
    1074705.0021    1572829.3162    1074705.5453     1573245.692
    1074757.8285    1573373.6044    1074786.6337    1573352.2546
     1074828.845    1573423.1331    1074885.9775    1573641.5886
#Sta/Elev= 30
       0   66.35   48.93   65.41   87.71   65.39  106.33      66  131.74    65.5
  147.23      66  170.45      66  180.84    66.5  218.35      66  285.03   66.01
  314.27    66.5  497.17    66.5  518.69   66.14  537.61    66.5  556.12   66.14
  568.71    64.5  583.73      66  592.44   66.37  615.99   65.91  625.49   66.39
  634.28    67.5  640.51    67.5  653.48    66.5  673.79      67  678.01   66.42
  689.52   65.93  700.16    66.5  709.92    66.5  727.14      66  898.71    65.5
#Mann= 3 ,0,0
       0    .035       0  537.61    .018       0  592.44    .035       0
Levee=-1,536.63,66.5,-1,634.6,67.5,,
Bank Sta=537.61,592.44
XS Rating Curve= 0 ,0
Exp/Cntr=0.3,0.1

Type RM Length L Ch R = 1 ,2000    ,210.95,200,171.25
XS GIS Cut Line= 5
     1074647.852    1572822.9662    1074654.8093    1573190.1452
    1074756.5623    1573437.2428    1074723.6121    1573484.9154
    1074765.3273    1573660.6387
#Sta/Elev= 30
       0    65.5   28.84   65.34   49.86      65   67.08      65  101.06    65.5
  129.45    65.5  146.89      66  153.06      66  159.45   65.61  176.74    66.5
  203.04    66.5  218.36      66  322.49      66  336.06    66.5  363.46    66.5
  407.64    66.1  440.13    66.5   602.5    66.5  613.36      67  625.02      67
  631.61   67.35  638.46      67  643.93      66  651.23      64  653.95    63.5
  660.89      64  674.39      66  691.66   66.15  769.56    65.5  873.03   65.29
#Mann= 3 ,0,0
       0    .035       0  643.93    .018       0  674.39    .035       0
Levee=-1,632.48,67.36,-1,691.71,66.15,,
Bank Sta=643.93,674.39
XS Rating Curve= 0 ,0
Exp/Cntr=0.3,0.1

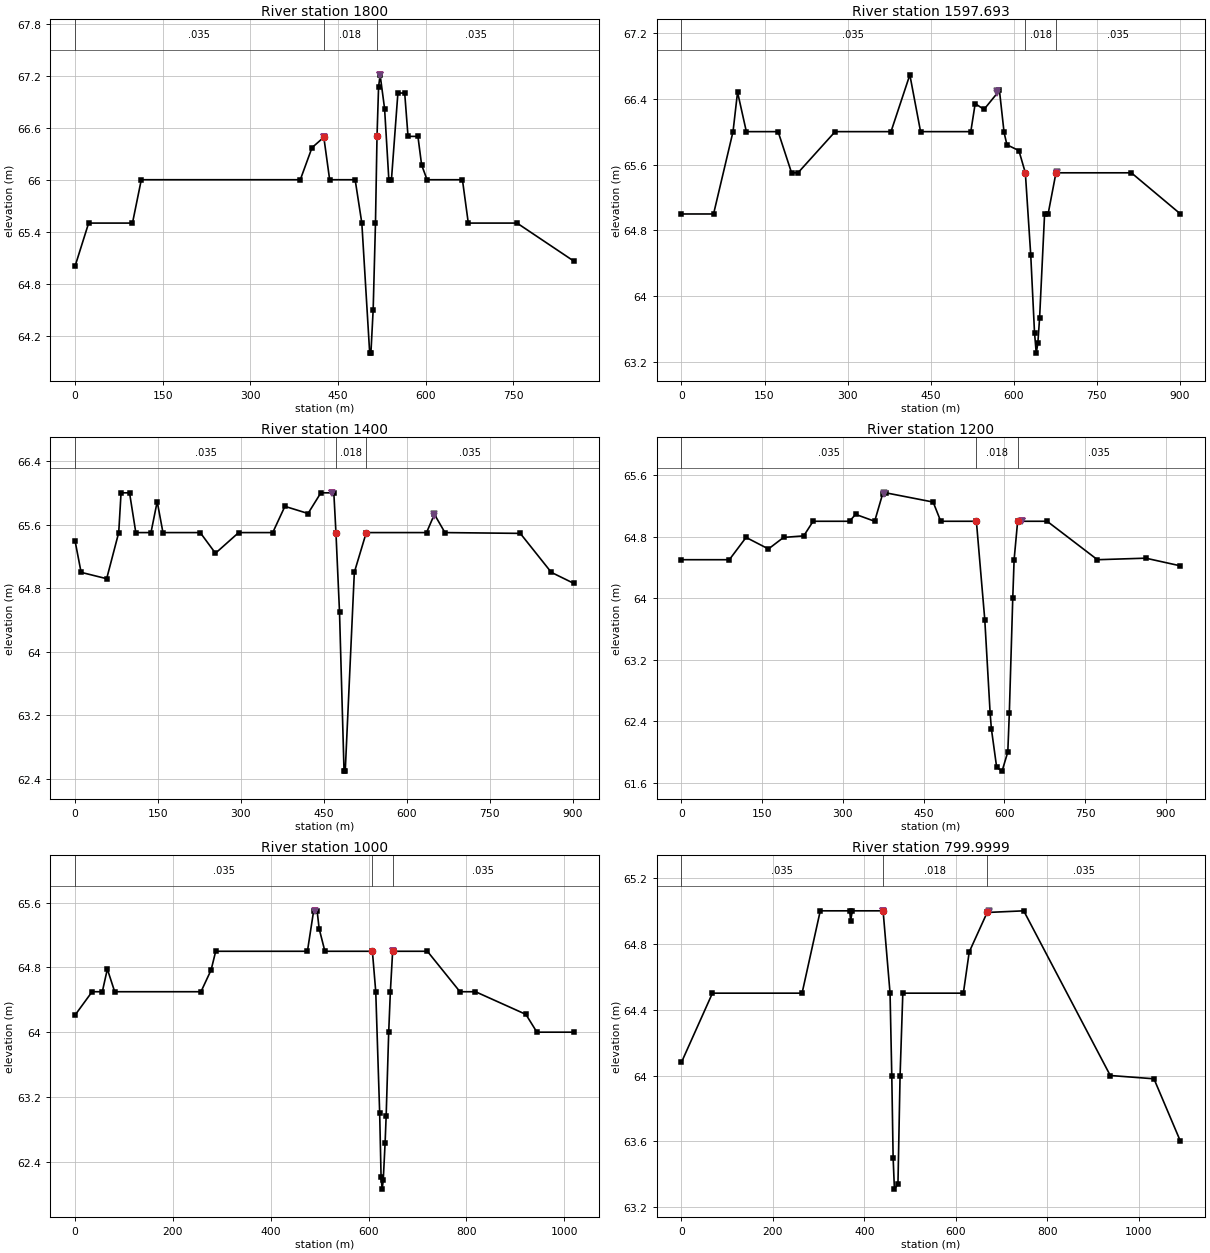
Type RM Length L Ch R = 1 ,1800    ,178.48,202.31,216.87
XS GIS Cut Line= 4
    1074573.7685    1572837.7829    1074574.9818    1573292.1952
    1074616.7788    1573440.8024    1074671.6646    1573679.6887
#Sta/Elev= 30
       0      65   23.35    65.5   98.36    65.5  113.46      66  385.56      66
  405.57   66.37  425.81   66.49  435.77      66   479.4      66  490.84    65.5
  504.29      64  506.36      64  510.23    64.5  514.19    65.5  516.82    66.5
  519.49   67.07  522.13   67.21  529.78   66.82  537.07      66  541.51      66
  552.55      67  564.19      67  569.89    66.5  586.83    66.5  593.16   66.17
  602.47      66  662.98      66  673.03    65.5  756.43    65.5   853.9   65.06
#Mann= 3 ,0,0
       0    .035       0  425.81    .018       0  516.82    .035       0
Levee=-1,425.4,66.49,-1,522.26,67.21,,
Bank Sta=425.81,516.82
XS Rating Curve= 0 ,0
Exp/Cntr=0.3,0.1

Type RM Length L Ch R = 1 ,1597.693,214.45,197.69,185.65
XS GIS Cut Line= 4
    1074514.5018    1572820.8495    1074538.1554    1573337.1533
    1074483.0853    1573489.6785    1074519.2643    1573709.0575
#Sta/Elev= 30
       0      65   57.98      65   93.14      66  101.31   66.48  117.22      66
   174.6      66  198.88    65.5   210.5    65.5  277.59      66  378.51      66
  412.53   66.69   431.9      66  522.64      66  530.54   66.34   546.5   66.27
  574.38    66.5  582.74   65.99  587.92   65.84  609.49   65.77  621.15    65.5
  630.92    64.5  637.71   63.56  640.84   63.31  643.73   63.43  646.92   63.74
  655.91      65  662.28      65  676.48    65.5  812.64    65.5  901.35      65
#Mann= 3 ,0,0
       0    .035       0  621.15    .018       0  676.48    .035       0
Levee=-1,570.7,66.49,-1,678.31,65.51,,
Bank Sta=621.15,676.48
XS Rating Curve= 0 ,0
Exp/Cntr=0.3,0.1

Type RM Length L Ch R = 1 ,1400    ,134.48,200,216.46
XS GIS Cut Line= 4
    1074410.7849    1572827.1995    1074407.7038    1573267.6814
     1074434.311    1573387.4131    1074381.1515    1573722.5513
#Sta/Elev= 30
       0    65.4   11.05      65   57.27   64.92   79.08    65.5   83.31      66
   98.66      66  109.99    65.5  137.43    65.5  148.67   65.89  159.11    65.5
  226.48    65.5  254.02   65.24  296.01    65.5  357.63    65.5  379.63   65.83
  421.45   65.74  444.65      66  468.11      66  471.94    65.5   478.4    64.5
  486.58    62.5  488.75    62.5   505.2      65  526.76    65.5  635.79    65.5
  649.99   65.73  669.06    65.5  805.29   65.49  861.41      65  902.47   64.86
#Mann= 3 ,0,0
       0    .035       0  471.94    .018       0  526.76    .035       0
Levee=-1,465.35,66,-1,649.01,65.73,,
Bank Sta=471.94,526.76
XS Rating Curve= 0 ,0
Exp/Cntr=0.3,0.1

Type RM Length L Ch R = 1 ,1200    ,66.77,200,200.75
XS GIS Cut Line= 5
    1074368.4515    1572827.1995    1074385.1202    1573206.6128
    1074357.9785    1573331.6301    1074224.0756    1573430.5995
    1074182.1844    1573680.2179
#Sta/Elev= 29
       0    64.5   88.97    64.5  120.09   64.79  161.64   64.64  189.73   64.79
  227.26   64.81  244.67      65  312.31      65  323.63   65.09  359.04      65
  374.04   65.36  379.78   65.37   467.7   65.25  481.84      65  548.07      65
  563.68   63.72  573.67    62.5  575.96    62.3  585.76    61.8  595.77   61.75
  606.47      62  609.26    62.5  615.68      64  618.19    64.5  624.74      65
  679.54      65  773.02    64.5  862.85   64.52  927.33   64.42
#Mann= 3 ,0,0
       0    .035       0  548.07    .018       0  624.74    .035       0
Levee=-1,376.34,65.36,-1,633.24,65,,
Bank Sta=548.07,624.74
XS Rating Curve= 0 ,0
Exp/Cntr=0.3,0.1

Type RM Length L Ch R = 1 ,1000    ,254.92,200,253.54
XS GIS Cut Line= 6
    1074332.4681    1572829.3162    1074358.6619    1573204.4961
    1074325.3532    1573296.4952    1074191.9693    1573271.0397
    1074139.3303     1573305.863    1074061.5342    1573644.2345
#Sta/Elev= 30
       0   64.21   34.97    64.5   55.86    64.5   66.14   64.78   81.16    64.5
  257.52    64.5  278.28   64.77  287.63      65  475.11      65  487.84    65.5
  494.94    65.5  499.07   65.28  510.83      65  607.92      65   614.8    64.5
  622.81      63  625.67   62.21  627.91   62.06  630.11   62.17  633.89   62.63
  636.05   62.96  641.27      64  644.66    64.5  649.32      65  720.32      65
  786.94    64.5  818.68    64.5  921.71   64.22  944.22      64 1020.04      64
#Mann= 3 ,0,0
       0    .035       0  607.92    .018       0  649.32    .035       0
Levee=-1,490.49,65.5,-1,651.02,65,,
Bank Sta=607.92,649.32
XS Rating Curve= 0 ,0
Exp/Cntr=0.3,0.1

Type RM Length L Ch R = 1 ,799.9999,294.09,199.95,86.36
XS GIS Cut Line= 6
    1074294.1034     1572816.087    1074341.2283    1573203.2294
    1074321.0168    1573239.0549    1074204.6368    1573182.7241
    1074134.8528    1573197.2763    1074002.0028     1573628.624
#Sta/Elev= 22
       0   64.08   67.69    64.5  263.62    64.5  303.38      65  367.67      65
  369.78   64.94  373.48      65  440.71      65  455.92    64.5   459.7      64
  462.65    63.5  465.46   63.31  473.18   63.34  477.84      64  483.82    64.5
  616.16    64.5  628.94   64.75  668.17   64.99  748.08      65  937.24      64
 1032.72   63.98 1090.67    63.6
#Mann= 3 ,0,0
       0    .035       0  440.71    .018       0  668.17    .035       0
Levee=-1,439.98,65,-1,671.53,65,,
Bank Sta=440.71,668.17
XS Rating Curve= 0 ,0
Exp/Cntr=0.3,0.1

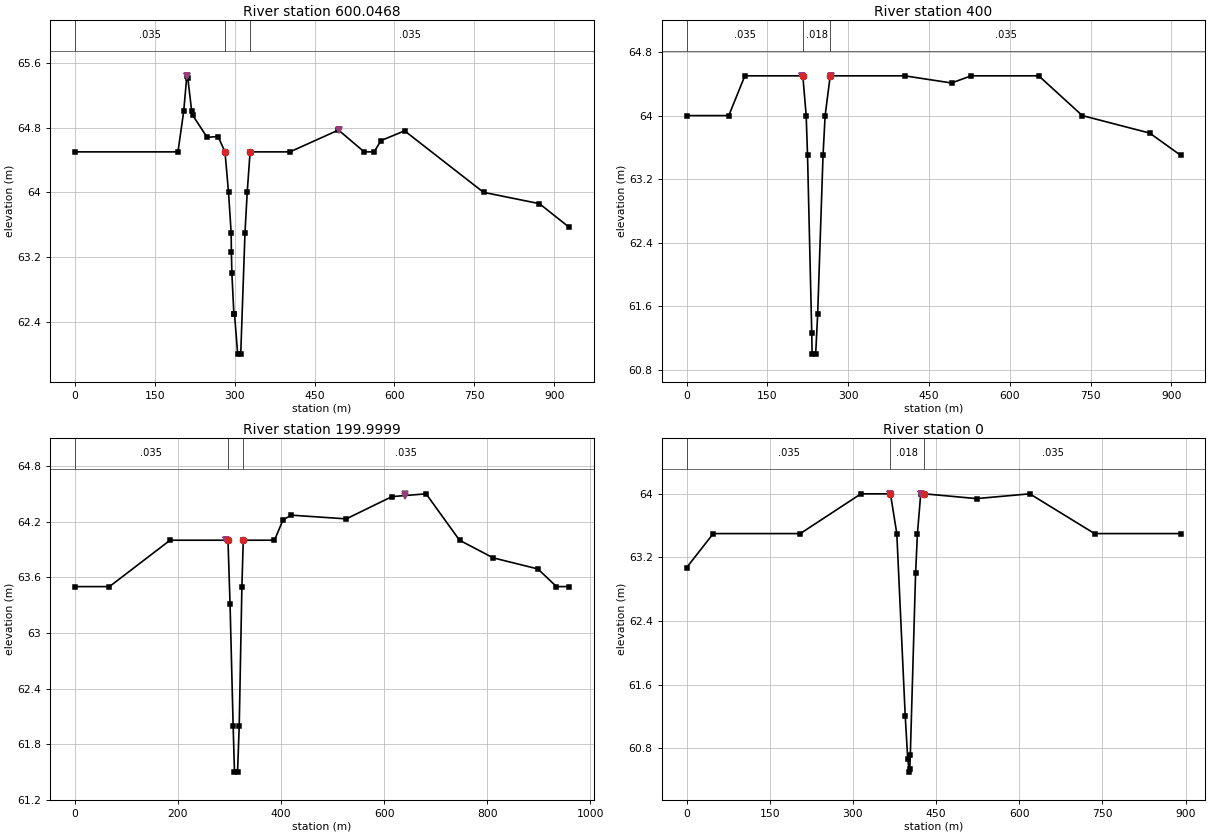
Type RM Length L Ch R = 1 ,600.0468,171.38,200.05,152.94
XS GIS Cut Line= 6
    1074201.2345    1572793.3328    1074191.8097    1572971.5487
    1074200.7204    1573157.4253    1074111.5405    1573169.8356
    1074055.1842    1573252.6504    1073963.9027    1573614.0719
#Sta/Elev= 30
       0    64.5  193.71    64.5  204.47      65  210.37   65.44  212.23   65.41
  219.55      65  221.68   64.95  248.33   64.68  268.99   64.69  281.96    64.5
   288.6      64  293.57    63.5  293.96   63.26  294.89      63  298.62    62.5
  299.76    62.5  305.81      62  311.51      62  319.51    63.5  323.67      64
  329.11    64.5   403.9    64.5  494.96   64.77  543.24    64.5  561.83    64.5
  574.89   64.64  619.07   64.76  767.17      64  872.08   63.86  927.54   63.57
#Mann= 3 ,0,0
       0    .035       0  281.96    .018       0  329.11    .035       0
Levee=-1,210.54,65.44,-1,495.8,64.77,,
Bank Sta=281.96,329.11
XS Rating Curve= 0 ,0
Exp/Cntr=0.3,0.1

Type RM Length L Ch R = 1 ,400     ,201.9,200,218.01
XS GIS Cut Line= 5
    1074008.6174     1572759.466    1074030.2323    1572901.4454
    1074124.9951    1573025.8185    1074037.9862    1573171.6877
    1073937.4443    1573607.7219
#Sta/Elev= 20
       0      64   78.46      64  108.31    64.5  215.89    64.5  222.13      64
  224.65    63.5  232.46   61.27  233.18      61  239.72      61  243.46    61.5
  253.42    63.5   257.3      64  266.76    64.5  404.91    64.5  491.96   64.41
  528.45    64.5  653.76    64.5  734.64      64  859.78   63.78   917.3    63.5
#Mann= 3 ,0,0
       0    .035       0  215.89    .018       0  266.76    .035       0
Levee=-1,215.01,64.5,-1,267.31,64.5,,
Bank Sta=215.89,266.76
XS Rating Curve= 0 ,0
Exp/Cntr=0.3,0.1

Type RM Length L Ch R = 1 ,199.9999,192.3,200,207.7
XS GIS Cut Line= 4
    1073767.3169     1572746.766    1073833.6822     1572915.828
    1074012.6483    1573073.2531    1073911.2505    1573601.9011
#Sta/Elev= 22
       0    63.5   67.28    63.5  184.83      64   297.1      64  301.12   63.31
  307.11      62  309.74    61.5  315.67    61.5  318.91      62  324.11    63.5
  326.74      64   387.3      64   403.9   64.22  419.97   64.27  526.46   64.23
  615.02   64.47  681.27    64.5  746.05      64  811.16   63.81   898.1   63.69
  934.08    63.5  958.26    63.5
#Mann= 3 ,0,0
       0    .035       0   297.1    .018       0  326.74    .035       0
Levee=-1,293.08,64,-1,641.27,64.5,,
Bank Sta=297.1,326.74
XS Rating Curve= 0 ,0
Exp/Cntr=0.3,0.1

Type RM Length L Ch R = 1 ,0       ,0,0,0
XS GIS Cut Line= 4
    1073640.3167    1572763.6994    1073700.5868    1573007.8409
    1073879.6812    1573275.1143    1073830.8171     1573589.201
#Sta/Elev= 19
       0   63.07   48.22    63.5  205.12    63.5  314.52      64  367.72      64
  379.18    63.5  394.34   61.21  398.95   60.66  401.86    60.5  402.68   60.54
  403.56   60.72  413.06      63  416.37    63.5  422.34      64  428.89      64
  523.01   63.94  618.92      64  735.75    63.5  891.07    63.5
#Mann= 3 ,0,0
       0    .035       0  367.72    .018       0  428.89    .035       0
Levee=-1,367.42,64,-1,422.72,64,,
Bank Sta=367.72,428.89
XS Rating Curve= 0 ,0
Exp/Cntr=0.3,0.1
LCMann Table=0